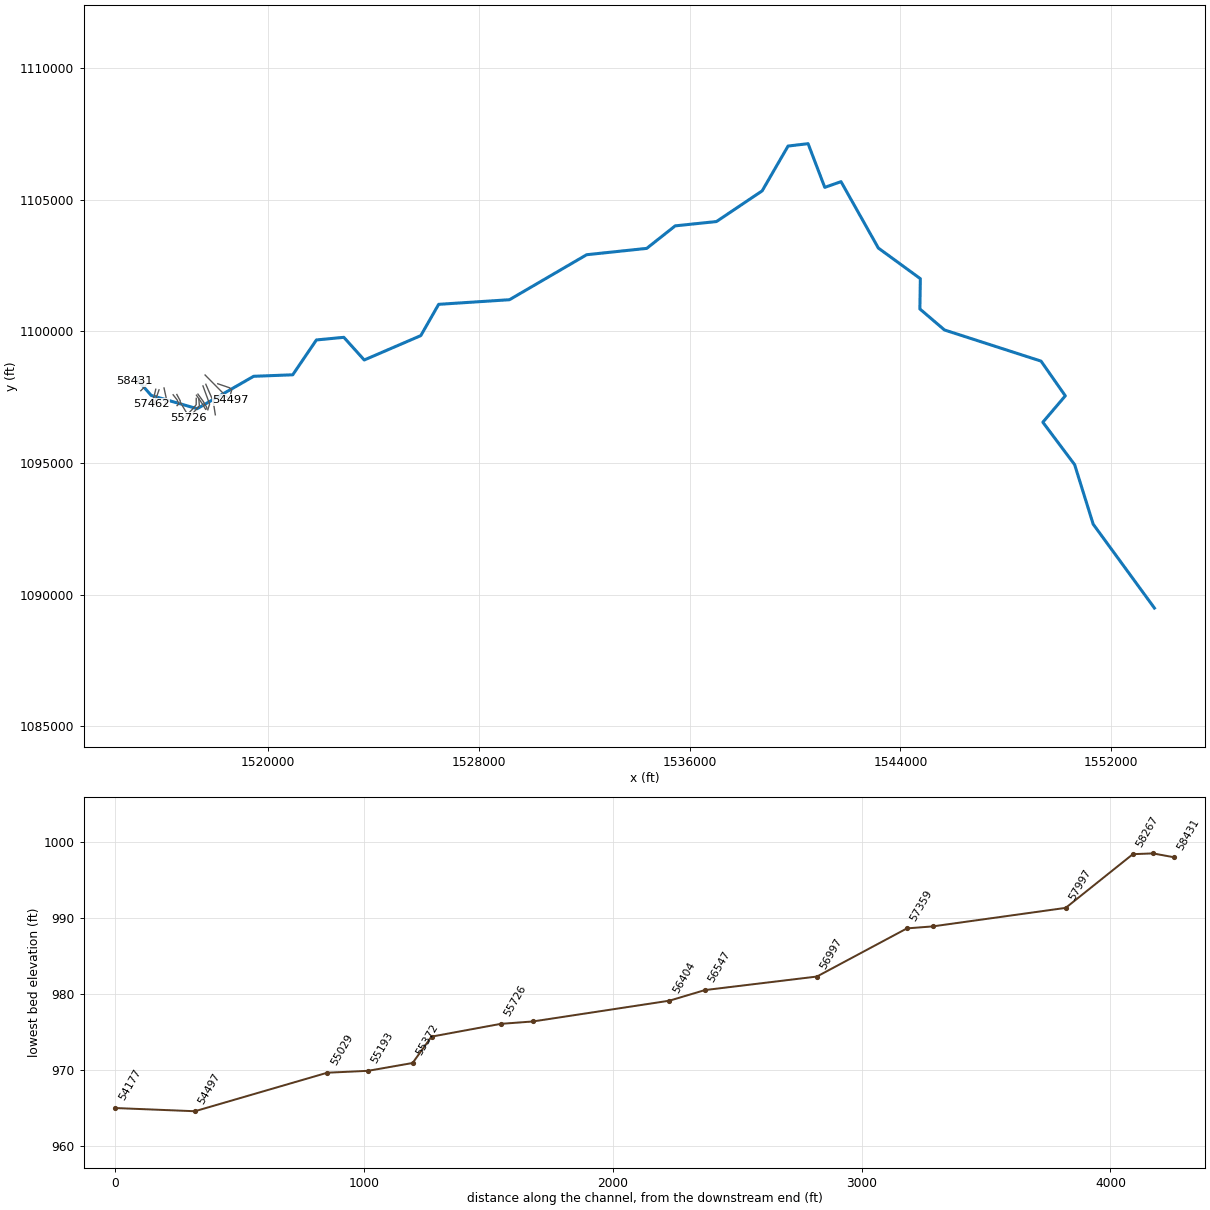
--- GeorgesCreek.prj (project) ---

Proj Title=Georges Creek Limited Detail Study
Current Plan=p13
Default Exp/Contr=0.3,0.1
English Units
Geom File=g01
Geom File=g02
Geom File=g03
Geom File=g06
Geom File=g09
Flow File=f01
Flow File=f02
Plan File=p01
Plan File=p08
Plan File=p02
Plan File=p03
Plan File=p04
Plan File=p05
Plan File=p06
Plan File=p13
Y Axis Title=Elevation
X Axis Title(PF)=Main Channel Distance
X Axis Title(XS)=Station
BEGIN DESCRIPTION:
Georges Creek
END DESCRIPTION:
DSS Export Rating Curves= 0
DSS Export Rating Curve Sorted= 0
DSS Export Volume Flow Curves= 0
DXF Filename=..\..\OneDrive - HDR, Inc\Desktop Items\SCDOT DB On-Call\Package 16\(P16) Georges Creek US 123 & SC 124\Georges Creek.
DXF OffsetX= 0
DXF OffsetY= 0
DXF ScaleX= 1
DXF ScaleY= 10

--- GeorgesCreek.p13 (plan) ---

Plan Title=Proposed
Program Version=6.10
Short Identifier=Proposed
Geom File=g06
Flow File=f02
Subcritical Flow
K Sum by GR= 0
Std Step Tol= 0.01
Critical Tol= 0.01
Num of Std Step Trials= 20
Max Error Tol= 0.3
Flow Tol Ratio= 0.001
Split Flow NTrial= 30
Split Flow Tol= 0.02
Split Flow Ratio= 0.02
Log Output Level= 0
Friction Slope Method= 1
Unsteady Friction Slope Method= 2
Unsteady Bridges Friction Slope Method= 1
Parabolic Critical Depth
Global Vel Dist= 0 , 0 , 0
Global Log Level= 0
CheckData=True
Encroach Param=-1 ,0,0, 0
BEGIN DESCRIPTION:
100-yr Georges Cr.
END DESCRIPTION:
Computation Interval=1MIN
Output Interval=1HOUR
Instantaneous Interval=1HOUR
Mapping Interval=1HOUR
Computation Time Step Use Courant=        0
Computation Time Step Use Time Series=    0
Computation Time Step Count To Double=0
Computation Time Step Max Doubling=0
Computation Time Step Max Halving=0
Computation Time Step Residence Courant=0
Run HTab= 0
Run UNet= 0
Run Sediment= 0
Run PostProcess= 0
Run WQNet= 0
Run RASMapper= 0
UNET Theta= 1
UNET Theta Warmup= 1
UNET ZTol= 0.02
UNET ZSATol= 0.02
UNET MxIter= 20
UNET Max Iter WO Improvement= 0
UNET MaxInSteps= 0
UNET DtIC= 0
UNET DtMin= 0
UNET MaxCRTS= 20
UNET WFStab= 2
UNET SFStab= 1
UNET WFX= 1
UNET SFX= 1
UNET Gravity=32.174
UNET 1D Methodology=Finite Difference
UNET DSS MLevel= 4
UNET Pardiso=0
UNET DZMax Abort= 100
UNET Use Existing IB Tables=-1
UNET Froude Reduction=False
UNET Froude Limit= 0.8
UNET Froude Power= 4
UNET D1 Cores= 0
UNET WindReference=Eulerian
UNET WindDragFormulation=Hsu (1988)
UNET D2 Coriolis=0
UNET D2 Cores= 0
UNET D2 Theta= 1
UNET D2 Theta Warmup= 1
UNET D2 Z Tol= 0.01
UNET D2 Volume Tol= 0.01
UNET D2 Max Iterations= 20
UNET D2 Equation= 0
UNET D2 RampUpFraction=0.1
UNET D2 TimeSlices= 1
UNET D2 Turbulence Formulation=Non-Conservative (original)
UNET D2 Eddy Viscosity=0.3
UNET D2 Transverse Eddy Viscosity=0.1
UNET D2 Smagorinsky Mixing=0
UNET D2 BCVolumeCheck=0
UNET D2 Cores=0
UNET D2 SolverType=PARDISO (Direct)
UNET D2 Minimum Iterations= 2147483647
UNET D2 Maximum Iterations= 2147483647
UNET D2 Restart Number= 10
UNET D2 Relaxation Coeff=1.3
UNET D2 SOR Precondition Iterations= 10
UNET D2 ILUT Maximum Fill= 8
UNET D2 ILUT Tolerance=1E-08
UNET D1D2 MaxIter= 0
UNET D1D2 ZTol=0.01
UNET D1D2 QTol=0.1
UNET D1D2 MinQTol=1
Write IC File= 0
Write IC File at Fixed DateTime=0
Write IC File at Sim End=0
Echo Input=False
Echo Parameters=False
Echo Output=False
Write Detailed= 0
HDF Write Warmup=0
HDF Write Time Slices=0
HDF Flush=0
HDF Compression= 1
HDF Chunk Size= 1
HDF Spatial Parts= 1
HDF Use Max Rows=0
HDF Fixed Rows= 1
Calibration Method= 0
Calibration Iterations= 20
Calibration Max Change=0.05
Calibration Tolerance=0.2
Calibration Maximum=1.5
Calibration Minimum=0.5
Calibration Optimization Method= 1
WQ AD Non Conservative
WQ ULTIMATE=-1
WQ Max Comp Step=1HOUR
WQ Output Interval=15MIN
WQ Output Selected Increments= 0
WQ Output face flow=0
WQ Output face velocity=0
WQ Output face area=0
WQ Output face dispersion=0
WQ Output cell volume=0
WQ Output cell surface area=0
WQ Output cell continuity=0
WQ Output cumulative cell continuity=0
WQ Output face conc=0
WQ Output face dconc_dx=0
WQ Output face courant=0
WQ Output face peclet=0
WQ Output face adv mass=0
WQ Output face disp mass=0
WQ Output cell mass=0
WQ Output cell source sink temp=0
WQ Output nsm pathways=0
WQ Output nsm derived pathways=0
WQ Create Restart=0
WQ Fixed Restart=0
WQ System Summary=0
WQ Write To DSS=0
Sorting and Armoring Iterations= 10
XS Update Threshold= 0.02
Bed Roughness Predictor= 0
Hydraulics Update Threshold= 0.02
Energy Slope Method= 1
Volume Change Method= 1
Sediment Retention Method= 0
Sediment TS Multiplier= 1
Warm Up Method= 0
XS Weighting Method= 0
Number of US Weighted Cross Sections= 1
Number of DS Weighted Cross Sections= 1
Upstream XS Weight=0
Main XS Weight=1
Downstream XS Weight=0
Number of DS XS's Weighted with US Boundary= 1
Upstream Boundary Weight= 1
Weight of XSs Associated with US Boundary= 0
Number of US XS's Weighted with DS Boundary= 1
Downstream Boundary Weight= 0.5
Weight of XSs Associated with DS Boundary= 0.5
Percentile Method= 0
Sediment Output Level= 3
Mass or Volume Output= 0
Output Increment Type= 1
Profile and TS Output Increment= 1
Transport Output Increment 1
XS Output Flag= 0
XS Output Increment= 10
Read HDF5 Sediment Hotstart= 0
Sediment Hotstart Type= 0
Write Gradation File= 0
Read Gradation Hotstart= 0
Write HDF5 File= 1
Write Binary Output= 1
Write DSS Sediment File= 0
DSS Sediment Output Type= 1
SV Curve= 0
Specific Gage Flag= 0
Subcell Erosion Methods= 0
Subcell Deposition Methods= 0
Advection Scheme= 1
Matrix Solver= 0
Implicit Weighting Factor= 1
Maximum Outer Loop Convergence Iterations= 5
Convergence Maximum Absolute= 0.001
Convergence RMSE= 0.0001
Grain Fractions Max Abs Error= 0.001
Max Subgrid Regions= 1
Max Subgrid Length Scale= 3.402823E+38
Initial Layer Thickness= 3.402823E+38
Min Layer Thickness= 3.402823E+38
Max Layer Thickness= 3.402823E+38
Number of Layers= 5

--- GeorgesCreek.p01 (plan) ---

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Plan Title=01_100-yr Single_Effective
Short Identifier=100-yr
Geom File=g01
Flow File=f01

--- GeorgesCreek.p02 (plan) ---

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Plan Title=Corrected Effective
Short Identifier=Cor
Geom File=g02
Flow File=f02

--- GeorgesCreek.p03 (plan) ---

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Plan Title=Corrected Effective_FEMA
Short Identifier=Cor_FEMA
Geom File=g02
Flow File=f01

--- GeorgesCreek.p04 (plan) ---

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Plan Title=Temporary
Short Identifier=Temp
Geom File=g03
Flow File=f02
UNET D2 Turbulence Formulation=None
UNET D2 Smagorinsky Mixing=0.05

--- GeorgesCreek.p05 (plan) ---

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Plan Title=Temporary_FEMA
Short Identifier=Temp_FEMA
Geom File=g03
Flow File=f01
UNET D2 Turbulence Formulation=None
UNET D2 Smagorinsky Mixing=0.05

--- GeorgesCreek.p06 (plan) ---

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Plan Title=Proposed_FEMA
Short Identifier=Prop_FEMA
Geom File=g06
Flow File=f01
UNET D2 Turbulence Formulation=None
UNET D2 Smagorinsky Mixing=0.05

--- GeorgesCreek.p08 (plan) ---

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Plan Title=Unrestricted
Short Identifier=Unrestr
Geom File=g09
Flow File=f02

--- GeorgesCreek.f02 (steady flow) ---

Flow Title=USGS
Program Version=6.10
Number of Profiles= 3
Profile Names=2% AEP,1% AEP,0.2% AEP
River Rch & RM=Georges Creek,Reach-1         ,58431
     213     245     326
River Rch & RM=Georges Creek,Reach-1         ,53869
     700     821    1130
River Rch & RM=Georges Creek,Reach-1         ,49997
     869    1020    1400
River Rch & RM=Georges Creek,Reach-1         ,43497
    1520    1780    2410
River Rch & RM=Georges Creek,Reach-1         ,38685
    1770    2060    2800
River Rch & RM=Georges Creek,Reach-1         ,27500
    2090    2420    3280
River Rch & RM=Georges Creek,Reach-1         ,17500
    3640    4210    5630
River Rch & RM=Georges Creek,Reach-1         ,17000
    4140    4780    6370
River Rch & RM=Georges Creek,Reach-1         ,11396
    4810    5530    7370
River Rch & RM=Georges Creek,Reach-1         ,3914
    5310    6100    8110
Boundary for River Rch & Prof#=Georges Creek,Reach-1         , 1
Up Type= 0
Dn Type= 3
Dn Slope=0.002
DSS Import GetInterval= 0
DSS Import GetPeak= 0
DSS Import FillOption= 0

--- GeorgesCreek.f01 (steady flow) ---

Flow Title=100-yr Single
Number of Profiles=1
Profile Names=100-year
River Rch & RM= Georges Creek,Reach-1,58431
     528
River Rch & RM= Georges Creek,Reach-1,53869
     680
River Rch & RM= Georges Creek,Reach-1,49997
    1190
River Rch & RM= Georges Creek,Reach-1,43497
    1395
River Rch & RM= Georges Creek,Reach-1,38685
    1675
River Rch & RM= Georges Creek,Reach-1,27500
    2989
River Rch & RM= Georges Creek,Reach-1,17500
    2989
River Rch & RM= Georges Creek,Reach-1,17000
    3518
River Rch & RM= Georges Creek,Reach-1,11396
    4073
River Rch & RM= Georges Creek,Reach-1,3914
    4483
Boundary for River Rch & Prof#=Georges Creek,Reach-1,1
Up Type=0
Dn Type=3
Dn Slope=0.002

--- GeorgesCreek.g06 (geometry) ---

Geom Title=Proposed
Program Version=6.10

River Reach=Georges Creek   ,Reach-1
Reach XY= 30
       1514998.4      1098222.95      1515571.43      1097567.69
      1517315.76      1097063.51      1519458.89      1098293.68
      1520942.22      1098350.91      1521840.13      1099673.85
      1522881.14       1099773.3      1523654.64      1098913.07
      1525800.86      1099838.37      1526477.78      1101026.11
      1529164.82      1101201.24       1532092.9      1102909.58
      1534372.43      1103150.37      1535452.02      1104005.28
      1537019.35      1104169.68      1538751.05      1105333.85
      1539734.54      1107035.57      1540493.94      1107126.19
       1541126.9      1105466.94      1541743.79      1105683.98
      1543159.33      1103162.95       1544753.2      1101999.73
       1544735.5      1100850.39      1545668.38      1100053.05
      1549331.26      1098870.35      1550252.76      1097551.86
       1549400.3      1096550.28      1550607.36      1094937.81
      1551310.47      1092679.14      1553633.71      1089494.87

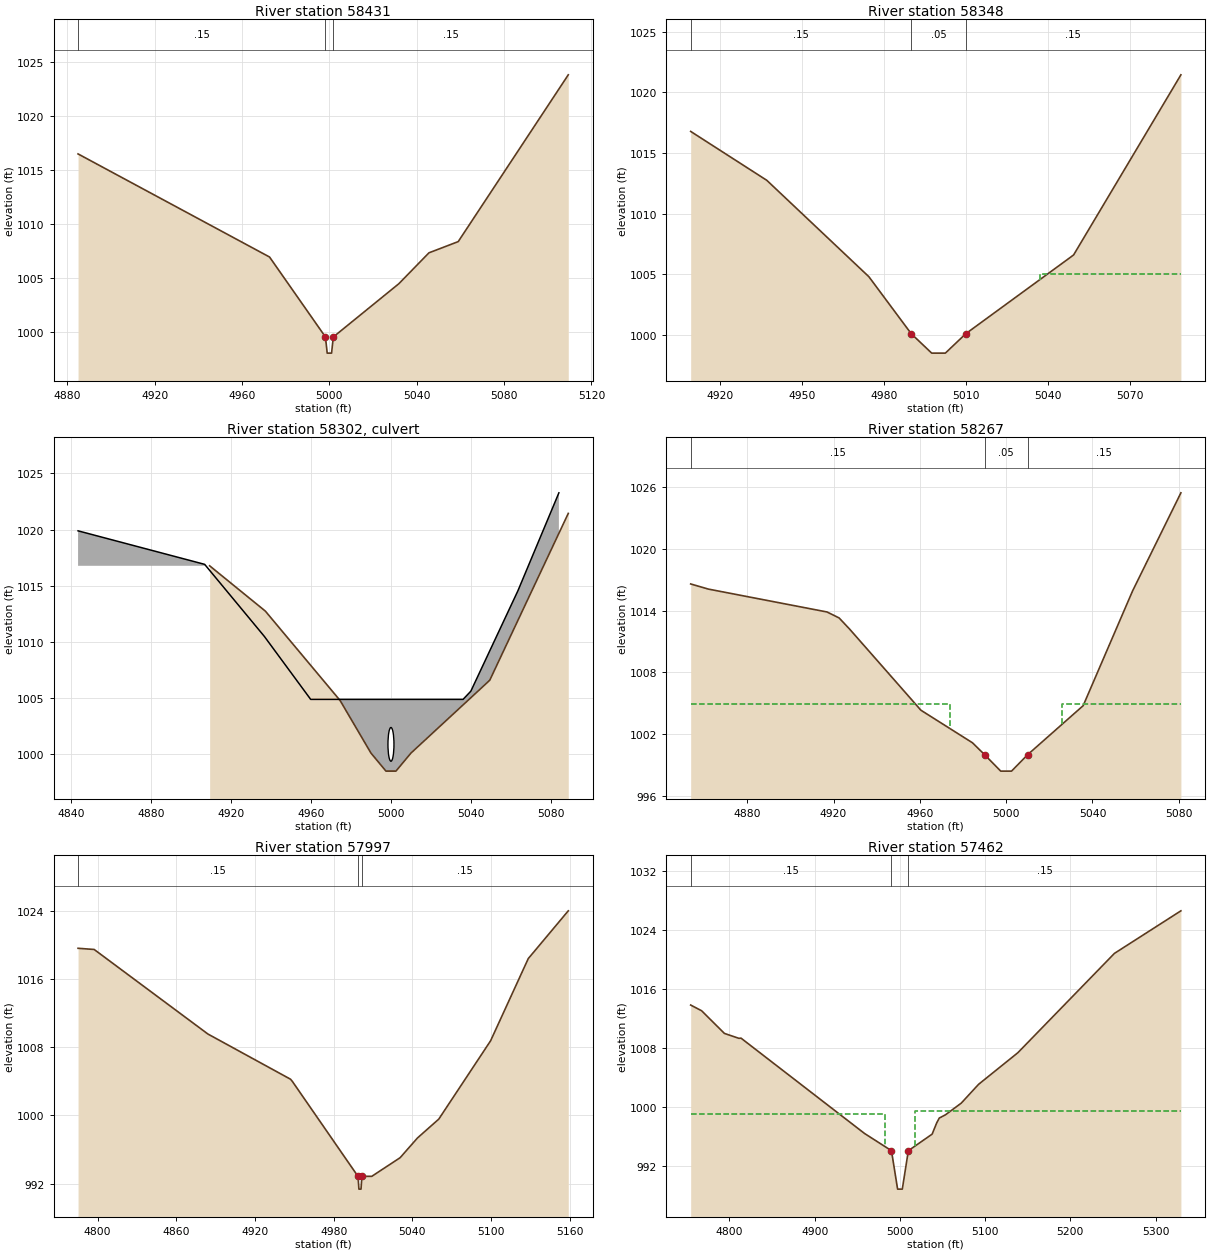
Type RM Length L Ch R = 1 ,58431   ,83,83,83
BEGIN DESCRIPTION:
Georges Creek 117.5
END DESCRIPTION:
XS GIS Cut Line= 3
      1515124.85      1098241.73      1515027.31      1098179.35
      1514939.98      1098114.71
#Sta/Elev= 10
  4884.9 1016.51  4972.6 1006.94  4998.2  999.52    4999  998.02    5001  998.02
  5001.8  999.52  5031.8 1004.46  5045.6 1007.33    5059 1008.37  5109.4 1023.85
#Mann= 3 ,-1,0
  4884.9     .15       0  4998.2     .05       0  5001.8     .15       0
Bank Sta=4998.2,5001.8
XS Rating Curve= 0 ,0
Exp/Cntr=0.5,0.3

Type RM Length L Ch R = 1 ,58348   ,81,81,81
BEGIN DESCRIPTION:
Georges Creek 117
END DESCRIPTION:
XS GIS Cut Line= 3
       1515149.8      1098152.13      1515064.74      1098105.63
      1514991.02      1098068.21
#Sta/Elev= 10
  4909.2 1016.78  4937.1 1012.75  4974.5 1004.81    4990 1000.12  4997.5  998.52
  5002.5  998.52    5010 1000.12  5048.5 1006.44  5049.5 1006.61  5088.8 1021.44
#Mann= 3 ,-1,0
  4909.2     .15       0    4990     .05       0    5010     .15       0
#XS Ineff= 2 , 0
            4963  1004.9    5037         1005.07
Permanent Ineff=
       F       F
Bank Sta=4990,5010
XS Rating Curve= 0 ,0
Exp/Cntr=0.5,0.3

Type RM Length L Ch R = 2 ,58302   ,,,
BEGIN DESCRIPTION:
Private Rd. (Georges Cr.) - TOR
Structure ID: LDS_GC_19
Approximate Survey Structure
END DESCRIPTION:
Bridge Culvert--1,0,-1,-1, 0
Deck Dist Width WeirC Skew NumUp NumDn MinLoCord MaxHiCord MaxSubmerge Is_Ogee
35.5,21,3,0, 8, 8, , , , 0, 1,1,,
  4843.3  4906.7  4936.6  4959.8  5036.1    5040  5063.6  5084.1
 1019.89 1016.91  1010.5  1004.9  1004.9 1005.63 1014.57 1023.27
  978.52  978.52  978.52  978.52  978.52  978.52  978.52  978.52
  4843.3  4906.7  4936.6  4959.8  5036.1    5040  5063.6  5084.1
 1019.89 1016.91  1010.5  1004.9  1004.9 1005.63 1014.57 1023.27
  978.42  978.42  978.42  978.42  978.42  978.42  978.42  978.42
Culvert=1,3,3,21,0.015,0.2,1,1,3,999.4,5000,999.3,5000,Culvert #1  , 0 ,35.5
    5000    5000
BC Culvert Barrel=1,,0
Culvert Bottom n=0.015
BC Design=,, 0 ,, 0 ,,,,,,
BC HTab HWMax=1021.44
BC Use User HTab Curves=0
BC User HTab FreeFlow(D)= 0

Type RM Length L Ch R = 1 ,58267   ,270,270,270
BEGIN DESCRIPTION:
Georges Creek 116.5
END DESCRIPTION:
XS GIS Cut Line= 3
      1515221.26      1098102.23      1515107.84      1098037.58
      1515018.24      1098001.29
#Sta/Elev= 14
  4853.8 1016.58    4862 1016.08    4917 1013.86  4922.6 1013.28  4927.5 1012.19
  4960.5 1004.33  4984.4 1001.17    4990 1000.02  4997.5  998.42  5002.5  998.42
    5010 1000.02  5035.7 1004.77  5058.6  1015.9    5081 1025.42
#Mann= 3 ,-1,0
  4853.8     .15       0    4990     .05       0    5010     .15       0
#XS Ineff= 2 , 0
            4974  1004.9    5026          1004.9
Permanent Ineff=
       F       F
Bank Sta=4990,5010
XS Rating Curve= 0 ,0
Exp/Cntr=0.5,0.3

Type RM Length L Ch R = 1 ,57997   ,535,535,535
BEGIN DESCRIPTION:
Georges Creek 116.0
END DESCRIPTION:
XS GIS Cut Line= 3
        1515425.        1098025.      1515288.85      1097858.76
      1515176.88      1097746.14
#Sta/Elev= 16
  4785.1 1019.58  4797.4 1019.44  4884.1 1009.53  4947.1 1004.23  4948.5 1003.97
  4998.5  992.85  4999.2  991.35  5000.8  991.35  5001.5  992.85    5009  992.85
  5030.6  995.03  5043.8  997.34  5060.1  999.56  5099.6 1008.74  5128.3 1018.37
  5158.8 1023.97
#Mann= 3 ,-1,0
  4785.1     .15       0  4998.5     .05       0  5001.5     .15       0
Bank Sta=4998.5,5001.5
XS Rating Curve= 0 ,0
Exp/Cntr=0.5,0.3

Type RM Length L Ch R = 1 ,57462   ,103,103,103
BEGIN DESCRIPTION:
Georges Creek 115.0
END DESCRIPTION:
XS GIS Cut Line= 3
      1515744.85      1097801.92       1515691.6      1097571.18
      1515580.04       1097251.7
#Sta/Elev= 19
  4754.5 1013.82  4767.3 1013.05  4794.1 1009.98    4811 1009.32  4813.6 1009.34
  4958.5  996.44  4990.1  994.11  4997.3  988.91  5002.8  988.91  5009.9  994.11
  5037.8  996.35  5043.2  997.88  5046.2  998.53  5053.5  998.97    5072 1000.55
  5092.3 1003.09  5138.4 1007.37  5251.7 1020.81  5329.7 1026.57
#Mann= 3 ,-1,0
  4754.5     .15       0  4990.1     .05       0  5009.9     .15       0
#XS Ineff= 2 , 0
            4982  999.05    5018          999.55
Permanent Ineff=
       F       F
Bank Sta=4990.1,5009.9
XS Rating Curve= 0 ,0
Exp/Cntr=0.5,0.3

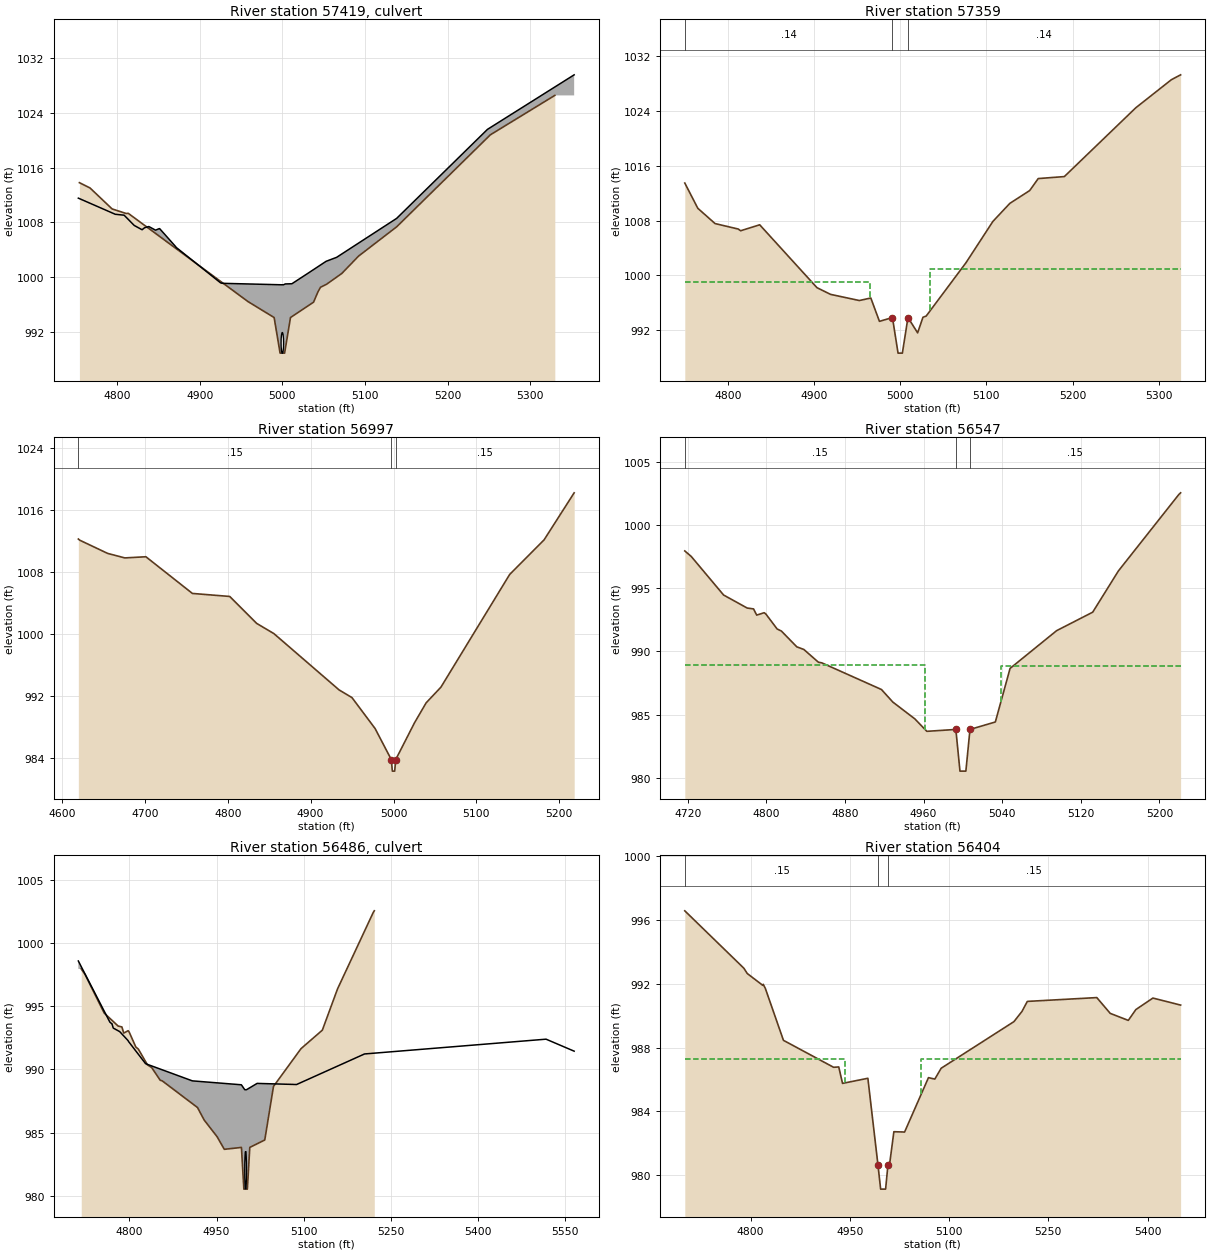
Type RM Length L Ch R = 2 ,57419   ,,,
BEGIN DESCRIPTION:
Hamilton St. (Georges Cr.) - TOR
Structure ID: LDS_GC_18
Approximate Survey Structure
END DESCRIPTION:
Bridge Culvert--1,0,-1,-1, 0
Deck Dist Width WeirC Skew NumUp NumDn MinLoCord MaxHiCord MaxSubmerge Is_Ogee
16.5,53,3,0, 25, 25, , , , 0, 1,1,,
  4753.2  4797.9  4808.6  4820.8  4830.3  4833.3  4838.5  4846.6    4851  4851.6
  4870.7  4871.6  4925.1  4926.1  4928.2  4998.5  5001.5  5003.5  5011.6  5031.4
    5053  5065.7  5138.3  5248.2  5353.1
 1011.56  1009.2 1009.07 1007.57 1006.94 1007.23 1007.41 1006.88  1007.1  1007.1
 1004.51 1004.36   999.2  999.14  999.11   998.9   998.9  999.02  999.05 1000.61
 1002.33 1002.91  1008.6 1021.61 1029.58
  968.91  968.91  968.91  968.91  968.91  968.91  968.91  968.91  968.91  968.91
  968.91  968.91  968.91  968.91  968.91  968.91  968.91  968.91  968.91  968.91
  968.91  968.91  968.91  968.91  968.91
  4753.2  4797.9  4808.6  4820.8  4830.3  4833.3  4838.5  4846.6    4851  4851.6
  4870.7  4871.6  4925.1  4926.1  4928.2  4998.5  5001.5  5003.5  5011.6  5031.4
    5053  5065.7  5138.3  5248.2  5353.1
 1011.56  1009.2 1009.07 1007.57 1006.94 1007.23 1007.41 1006.88  1007.1  1007.1
 1004.51 1004.36   999.2  999.14  999.11   998.9   998.9  999.02  999.05 1000.61
 1002.33 1002.91  1008.6 1021.61 1029.58
  968.65  968.65  968.65  968.65  968.65  968.65  968.65  968.65  968.65  968.65
  968.65  968.65  968.65  968.65  968.65  968.65  968.65  968.65  968.65  968.65
  968.65  968.65  968.65  968.65  968.65
Culvert=1,3,3,53,0.015,0.2,1,1,3,988.91,5000,988.65,5000,Culvert #1  , 0 ,16.5
    5000    5000
BC Culvert Barrel=1,,0
Culvert Bottom n=0.015
BC Design=,, 0 ,, 0 ,,,,,,
BC HTab HWMax=1026.57
BC Use User HTab Curves=0
BC User HTab FreeFlow(D)= 0

Type RM Length L Ch R = 1 ,57359   ,362,362,362
BEGIN DESCRIPTION:
Georges Creek 114.5
END DESCRIPTION:
XS GIS Cut Line= 3
      1515869.09       1097779.1      1515787.95      1097545.83
      1515671.32      1097239.02
#Sta/Elev= 27
  4750.1 1013.49  4765.2  1009.8  4785.2 1007.57  4812.1 1006.77  4814.9 1006.52
    4837 1007.39  4903.4  998.21  4919.2  997.23  4952.6  996.33  4965.9   996.7
  4975.9  993.29    4991  993.85  4997.5  988.65  5002.5  988.65    5009  993.85
  5020.2  991.61  5026.4  993.89  5030.1  994.06  5076.3 1001.85  5107.5 1007.88
  5127.2 1010.52  5150.2 1012.39  5160.1 1014.14  5190.4 1014.43  5273.4 1024.49
  5314.6 1028.58  5325.3 1029.29
#Mann= 3 ,-1,0
  4750.1     .14       0    4991     .05       0    5009     .14       0
#XS Ineff= 2 , 0
            4965  999.07    5035          1000.9
Permanent Ineff=
       F       F
Bank Sta=4991,5009
XS Rating Curve= 0 ,0
Exp/Cntr=0.5,0.3

Type RM Length L Ch R = 1 ,56997   ,450,450,450
BEGIN DESCRIPTION:
Georges Creek 114.0
END DESCRIPTION:
XS GIS Cut Line= 3
      1516059.26       1097850.1      1516138.96       1097478.3
      1516097.29      1097264.38
#Sta/Elev= 22
  4619.8  1012.3  4621.7 1012.14  4655.2 1010.44  4675.9 1009.86  4701.3 1010.01
  4757.4 1005.27  4802.4 1004.88  4834.9  1001.4  4855.7 1000.08  4934.4   992.8
  4949.9  991.81  4977.8  987.81  4997.3  983.81  4998.6  982.31  5001.4  982.31
  5002.7  983.81  5025.3  988.55  5039.4  991.14  5057.2  993.16  5140.1 1007.72
  5181.6 1012.19  5217.9 1018.27
#Mann= 3 ,-1,0
  4619.8     .15       0  4997.3     .05       0  5002.7     .15       0
Bank Sta=4997.3,5002.7
XS Rating Curve= 0 ,0
Exp/Cntr=0.5,0.3

Type RM Length L Ch R = 1 ,56547   ,143,143,143
BEGIN DESCRIPTION:
Georges Creek 113.0
END DESCRIPTION:
XS GIS Cut Line= 4
       1516404.1      1097591.47      1516556.52      1097397.78
      1516619.62      1097241.56       1516553.7      1097180.71
#Sta/Elev= 30
  4716.9  997.96  4723.5  997.52  4756.4  994.47  4780.4  993.44  4786.9  993.37
  4790.1  992.88  4797.7  993.07  4799.4  992.97  4810.9  991.78  4815.2  991.62
  4830.9  990.37  4838.1  990.16  4852.9  989.15  4856.4   989.1  4917.1  986.99
  4928.6     986    4951  984.67  4963.3  983.68  4992.8  983.83    4997  980.53
    5003  980.53  5007.2  983.83    5033  984.42    5048  988.66  5095.4  991.65
  5131.8   993.1  5132.1  993.11  5158.3  996.38  5219.8 1002.43  5221.6 1002.56
#Mann= 3 ,-1,0
  4716.9     .15       0  4992.8     .05       0  5007.2     .15       0
#XS Ineff= 2 , 0
          4961.5   988.9  5038.5          988.88
Permanent Ineff=
       F       F
Bank Sta=4992.8,5007.2
XS Rating Curve= 0 ,0
Exp/Cntr=0.5,0.3

Type RM Length L Ch R = 2 ,56486   ,,,
BEGIN DESCRIPTION:
Hillcrest Dr. (Georges Cr.) - TOR
Structure ID: LDS_GC_17
Approximate Survey Structure
END DESCRIPTION:
Bridge Culvert--1,0,-1,-1, 0
Deck Dist Width WeirC Skew NumUp NumDn MinLoCord MaxHiCord MaxSubmerge Is_Ogee
37,48,3,0, 19, 19, , , , 0, 1,1,,
  4711.9  4766.2    4769  4769.8    4772  4783.1  4797.3    4798  4798.3  4827.7
  4908.3  4992.7  4998.5  5001.5  5019.8  5087.7  5204.8  5517.4  5565.8
  998.59  993.75  993.64  993.63  993.28     993   992.3  992.25  992.22  990.46
   989.1  988.79   988.4   988.4   988.9  988.81  991.23   992.4  991.45
  960.53  960.53  960.53  960.53  960.53  960.53  960.53  960.53  960.53  960.53
  960.53  960.53  960.53  960.53  960.53  960.53  960.53  960.53  960.53
  4711.9  4766.2    4769  4769.8    4772  4783.1  4797.3    4798  4798.3  4827.7
  4908.3  4992.7  4998.5  5001.5  5019.8  5087.7  5204.8  5517.4  5565.8
  998.59  993.75  993.64  993.63  993.28     993   992.3  992.25  992.22  990.46
   989.1  988.79   988.4   988.4   988.9  988.81  991.23   992.4  991.45
  960.29  960.29  960.29  960.29  960.29  960.29  960.29  960.29  960.29  960.29
  960.29  960.29  960.29  960.29  960.29  960.29  960.29  960.29  960.29
Culvert=1,3,3,48,0.015,0.2,1,1,3,980.53,5000,979.13,5000,Culvert #1  , 0 ,37
    5000    5000
BC Culvert Barrel=1,,0
Culvert Bottom n=0.015
BC Design=,, 0 ,, 0 ,,,,,,
BC HTab HWMax=1002.56
BC Use User HTab Curves=0
BC User HTab FreeFlow(D)= 0

Type RM Length L Ch R = 1 ,56404   ,548,548,548
BEGIN DESCRIPTION:
Georges Creek 112.5
END DESCRIPTION:
XS GIS Cut Line= 4
      1516544.98      1097602.71      1516675.84      1097358.83
      1516669.38      1097320.07      1516891.25      1096947.79
#Sta/Elev= 30
  4700.5  996.58  4789.8  992.98  4794.9  992.65  4818.3  991.91  4819.1  991.97
  4822.2  991.72  4849.6  988.46  4925.4  986.77  4933.2  986.79  4938.9  985.76
  4977.2  986.08  4992.5  980.63  4996.5  979.13    5004  979.13  5007.5  980.63
  5010.6  980.87  5016.5  982.73  5032.7  982.71  5068.8  986.12  5078.4  986.03
    5088  986.71  5197.9  989.63  5210.1  990.27  5218.2   990.9  5323.2  991.14
  5343.5  990.15  5370.8  989.71  5382.3  990.39    5408  991.11  5449.9  990.67
#Mann= 3 ,-1,0
  4700.5     .15       0  4992.5     .05       0  5007.5     .15       0
#XS Ineff= 2 , 0
            4942   987.3    5058           987.3
Permanent Ineff=
       F       F
Bank Sta=4992.5,5007.5
XS Rating Curve= 0 ,0
Exp/Cntr=0.3,0.1

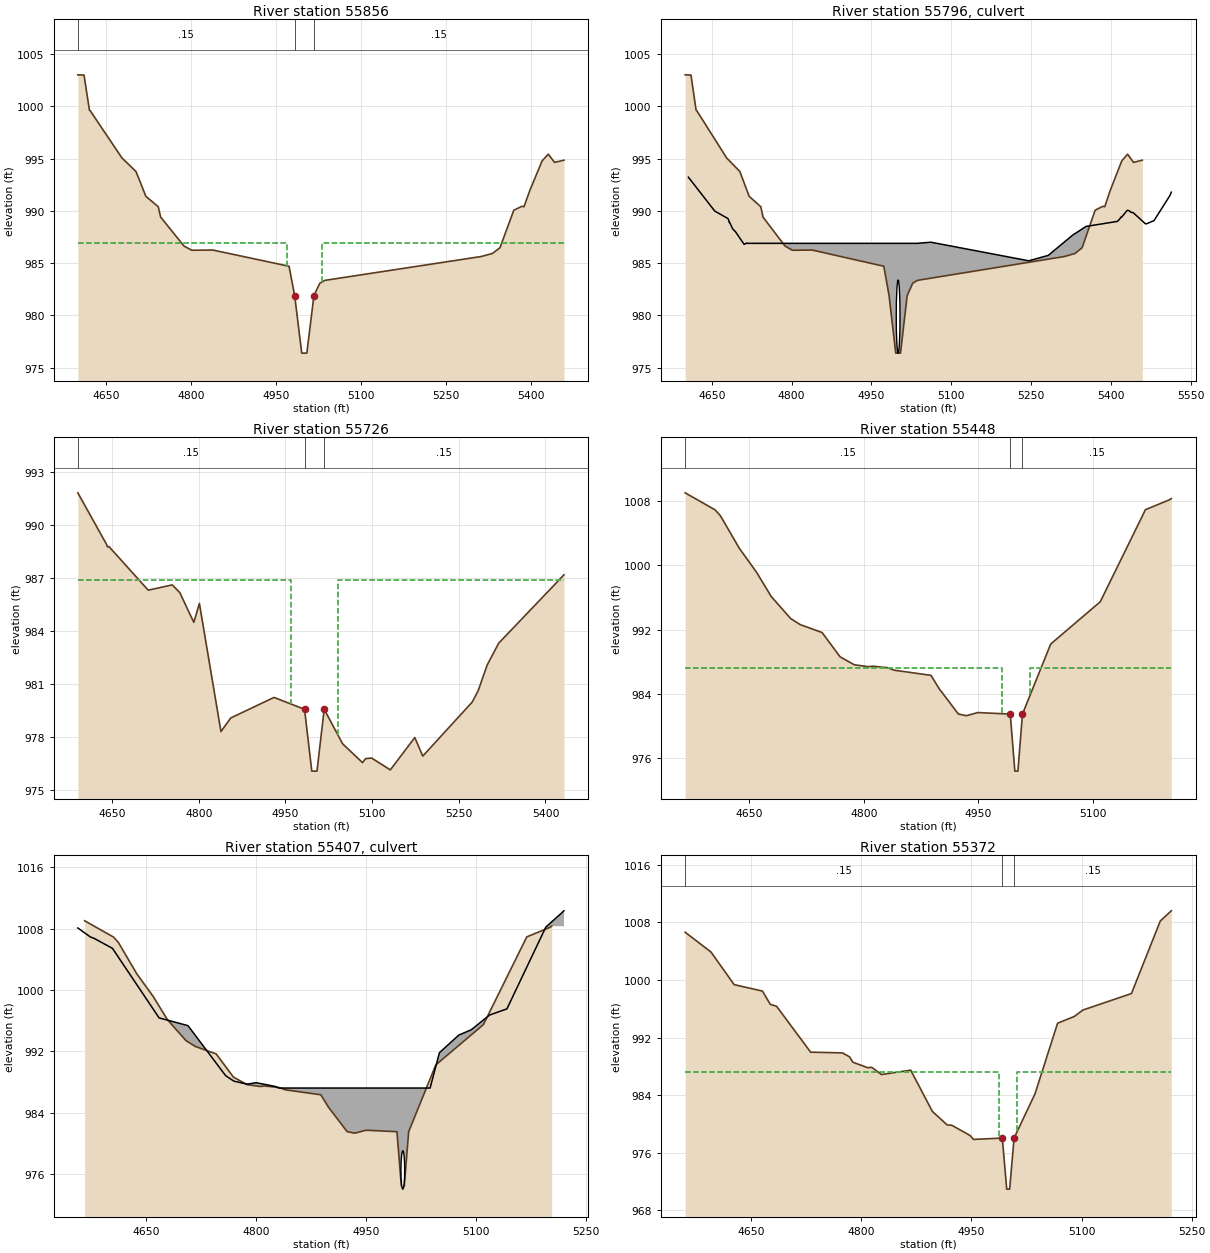
Type RM Length L Ch R = 1 ,55856   ,130,130,130
BEGIN DESCRIPTION:
Georges Creek 112.0
END DESCRIPTION:
XS GIS Cut Line= 4
      1517281.41      1097454.55      1517278.87       1097216.2
      1517177.45      1097086.89      1516863.04      1096757.26
#Sta/Elev= 30
  4600.2 1003.02  4611.1    1003  4620.7  999.63    4622  999.59  4678.2  995.06
  4702.9  993.77  4720.3   991.4  4742.2   990.4  4746.4  989.41  4787.7  986.64
  4801.4  986.24  4838.6  986.26  4973.1  984.71    4983   981.9  4995.5   976.4
  5004.5   976.4    5017   981.9  5027.3  983.08  5036.4  983.36  5312.2  985.64
  5332.1  985.93  5345.5  986.48  5369.9  990.07  5384.5  990.45  5387.9   990.4
    5398  991.93  5419.9  994.79  5430.8  995.43  5441.9  994.64  5458.5  994.86
#Mann= 3 ,-1,0
  4600.2     .15       0    4983     .05       0    5017     .15       0
#XS Ineff= 2 , 0
            4969   986.9    5031           986.9
Permanent Ineff=
       F       F
Bank Sta=4983,5017
XS Rating Curve= 0 ,0
Exp/Cntr=0.5,0.3

Type RM Length L Ch R = 2 ,55796   ,,,
BEGIN DESCRIPTION:
Fleetwood Dr. (Georges Cr.) - TOR
Structure ID: LDS_GC_16
Approximate Survey Structure
END DESCRIPTION:
Bridge Culvert--1,0,-1,-1, 0
Deck Dist Width WeirC Skew NumUp NumDn MinLoCord MaxHiCord MaxSubmerge Is_Ogee
27.5,65,3,0, 31, 31, , , , 0, 1,1,,
  4606.2  4655.7  4679.9  4680.7  4681.7  4682.9  4683.7  4689.3  4694.5  4710.9
  4715.3  4715.8  5035.3  5061.6  5245.4  5281.9  5327.5  5352.8  5411.7  5416.5
  5418.6  5419.3  5430.2  5432.9    5438    5441  5464.3  5466.4  5480.5  5510.1
  5512.9
  993.23  989.99  989.29  989.25  989.15   988.9   988.9  988.29  988.02   986.8
  986.93   986.9   986.9  987.01  985.23  985.75  987.68  988.52     989  989.26
  989.42  989.39  990.06  990.04  989.85  989.85  988.77  988.77  989.08  991.46
  991.79
   956.4   956.4   956.4   956.4   956.4   956.4   956.4   956.4   956.4   956.4
   956.4   956.4   956.4   956.4   956.4   956.4   956.4   956.4   956.4   956.4
   956.4   956.4   956.4   956.4   956.4   956.4   956.4   956.4   956.4   956.4
   956.4
  4606.2  4655.7  4679.9  4680.7  4681.7  4682.9  4683.7  4689.3  4694.5  4710.9
  4715.3  4715.8  5035.3  5061.6  5245.4  5281.9  5327.5  5352.8  5411.7  5416.5
  5418.6  5419.3  5430.2  5432.9    5438    5441  5464.3  5466.4  5480.5  5510.1
  5512.9
  993.23  989.99  989.29  989.25  989.15   988.9   988.9  988.29  988.02   986.8
  986.93   986.9   986.9  987.01  985.23  985.75  987.68  988.52     989  989.26
  989.42  989.39  990.06  990.04  989.85  989.85  988.77  988.77  989.08  991.46
  991.79
  956.08  956.08  956.08  956.08  956.08  956.08  956.08  956.08  956.08  956.08
  956.08  956.08  956.08  956.08  956.08  956.08  956.08  956.08  956.08  956.08
  956.08  956.08  956.08  956.08  956.08  956.08  956.08  956.08  956.08  956.08
  956.08
Culvert=1,7,7,65,0.015,0.4,1,1,3,976.4,5000,976.08,5000,Culvert #1  , 0 ,27.5
    5000    5000
BC Culvert Barrel=1,,0
Culvert Bottom n=0.015
BC Design=,, 0 ,, 0 ,,,,,,
BC HTab HWMax=1003.02
BC Use User HTab Curves=0
BC User HTab FreeFlow(D)= 0

Type RM Length L Ch R = 1 ,55726   ,278,278,278
BEGIN DESCRIPTION:
Georges Creek 111.5
END DESCRIPTION:
XS GIS Cut Line= 3
      1517377.76       1097436.8      1517400.58       1097173.1
      1516999.96       1096716.7
#Sta/Elev= 28
  4590.6  991.83  4640.5   988.9  4641.8  988.77  4644.4  988.79  4712.4  986.32
    4754  986.62  4767.1  986.18  4791.3   984.5    4801  985.57  4838.3  978.32
  4855.3  979.09  4930.1  980.25    4983  979.58  4995.5  976.08  5004.5  976.08
    5017  979.58  5048.8  977.63  5083.3  976.56  5088.7  976.79  5099.1  976.82
  5131.4  976.15  5173.8  977.98  5187.6  976.93  5273.2  979.99  5283.6  980.64
    5299  982.08    5319  983.32    5432  987.19
#Mann= 3 ,-1,0
  4590.6     .15       0    4983     .05       0    5017     .15       0
#XS Ineff= 2 , 0
            4959   986.9    5041          986.92
Permanent Ineff=
       F       F
Bank Sta=4983,5017
XS Rating Curve= 0 ,0
Exp/Cntr=0.5,0.3

Type RM Length L Ch R = 1 ,55448   ,76,76,76
BEGIN DESCRIPTION:
Georges Creek 111.0
END DESCRIPTION:
XS GIS Cut Line= 3
      1517289.01      1097576.26      1517534.97      1097213.67
      1517633.85      1097041.25
#Sta/Elev= 30
  4566.1 1009.04  4605.3 1006.92  4612.1 1006.21  4637.1 1002.13  4659.7  999.14
  4678.9  996.13  4704.4  993.38    4717  992.63  4745.5  991.65    4769  988.63
  4787.6  987.64  4805.6   987.4  4811.9  987.46  4831.1  987.27  4840.2  986.96
  4888.2  986.32  4898.8  984.67    4924  981.51  4934.5   981.3  4949.6  981.69
    4992   981.5    4998   974.4    5002   974.4    5008   981.5  5044.6  990.13
  5046.1  990.31  5109.9  995.48  5169.1 1006.94  5200.5 1008.17    5203 1008.33
#Mann= 3 ,-1,0
  4566.1     .15       0    4992     .05       0    5008     .15       0
#XS Ineff= 2 , 0
          4981.5   987.2  5018.5           987.2
Permanent Ineff=
       F       F
Bank Sta=4992,5008
XS Rating Curve= 0 ,0
Exp/Cntr=0.5,0.3

Type RM Length L Ch R = 2 ,55407   ,,,
BEGIN DESCRIPTION:
Ann Drive - TOR
Structure ID: LDS_GC_15A
Approximate Survey Structure
END DESCRIPTION:
Bridge Culvert--1,0,-1,-1, 0
Deck Dist Width WeirC Skew NumUp NumDn MinLoCord MaxHiCord MaxSubmerge Is_Ogee
16,50,3,0, 20, 20, , , , 0, 1,1,,
  4556.8  4573.7  4579.4    4604  4667.6    4707  4758.3  4769.6  4787.7  4799.9
    4826    4831  5037.2  5049.9  5076.4  5093.2  5118.3    5142    5195  5219.8
  1008.1 1006.94 1006.72 1005.44  996.36  995.35  988.82   988.1  987.71   987.9
  987.41   987.2   987.2  991.81  994.12   994.8  996.73  997.54 1008.21 1010.34
  952.18  952.18  952.18  952.18  952.18  952.18  952.18  952.18  952.18  952.18
  952.18  952.18  952.18  952.18  952.18  952.18  952.18  952.18  952.18  952.18
  4556.8  4573.7  4579.4    4604  4667.6    4707  4758.3  4769.6  4787.7  4799.9
    4826    4831  5037.2  5049.9  5076.4  5093.2  5118.3    5142    5195  5219.8
  1008.1 1006.94 1006.72 1005.44  996.36  995.35  988.82   988.1  987.71   987.9
  987.41   987.2   987.2  991.81  994.12   994.8  996.73  997.54 1008.21 1010.34
  951.93  951.93  951.93  951.93  951.93  951.93  951.93  951.93  951.93  951.93
  951.93  951.93  951.93  951.93  951.93  951.93  951.93  951.93  951.93  951.93
Culvert=1,5,5,50,0.015,0.2,1,1,3,974,5000,973.75,5000,Culvert #1  , 0 ,16
    5000    5000
BC Culvert Barrel=1,,0
Culvert Bottom n=0.015
BC Design=,, 0 ,, 0 ,,,,,,
BC HTab HWMax=1009.04
BC Use User HTab Curves=0
BC User HTab FreeFlow(D)= 0

Type RM Length L Ch R = 1 ,55372   ,179,179,179
BEGIN DESCRIPTION:
Georges Creek 110.5
END DESCRIPTION:
XS GIS Cut Line= 4
       1517344.8      1097616.83      1517552.71      1097332.84
      1517674.42      1097122.39       1517687.1      1097056.46
#Sta/Elev= 30
    4560 1006.64  4595.1  1003.9  4626.7  999.36  4665.3  998.46  4675.9  996.62
  4684.5  996.35  4730.9  989.97  4774.3  989.87  4783.9  989.32  4788.5  988.57
  4808.7  987.81  4814.2  987.86  4827.4  986.86  4867.2  987.47  4896.7  981.74
  4916.8  979.86  4923.4   979.8    4948  978.39  4952.7  977.84    4992  978.03
    4998  970.93    5002  970.93    5008  978.03  5036.5  984.17  5067.3     994
    5090  994.93  5101.8  995.83  5167.9  998.12  5207.2 1008.21  5222.2 1009.62
#Mann= 3 ,-1,0
    4560     .15       0    4992     .05       0    5008     .15       0
#XS Ineff= 2 , 0
          4987.5   987.2  5012.5           987.2
Permanent Ineff=
       F       F
Bank Sta=4992,5008
XS Rating Curve= 0 ,0
Exp/Cntr=0.5,0.3

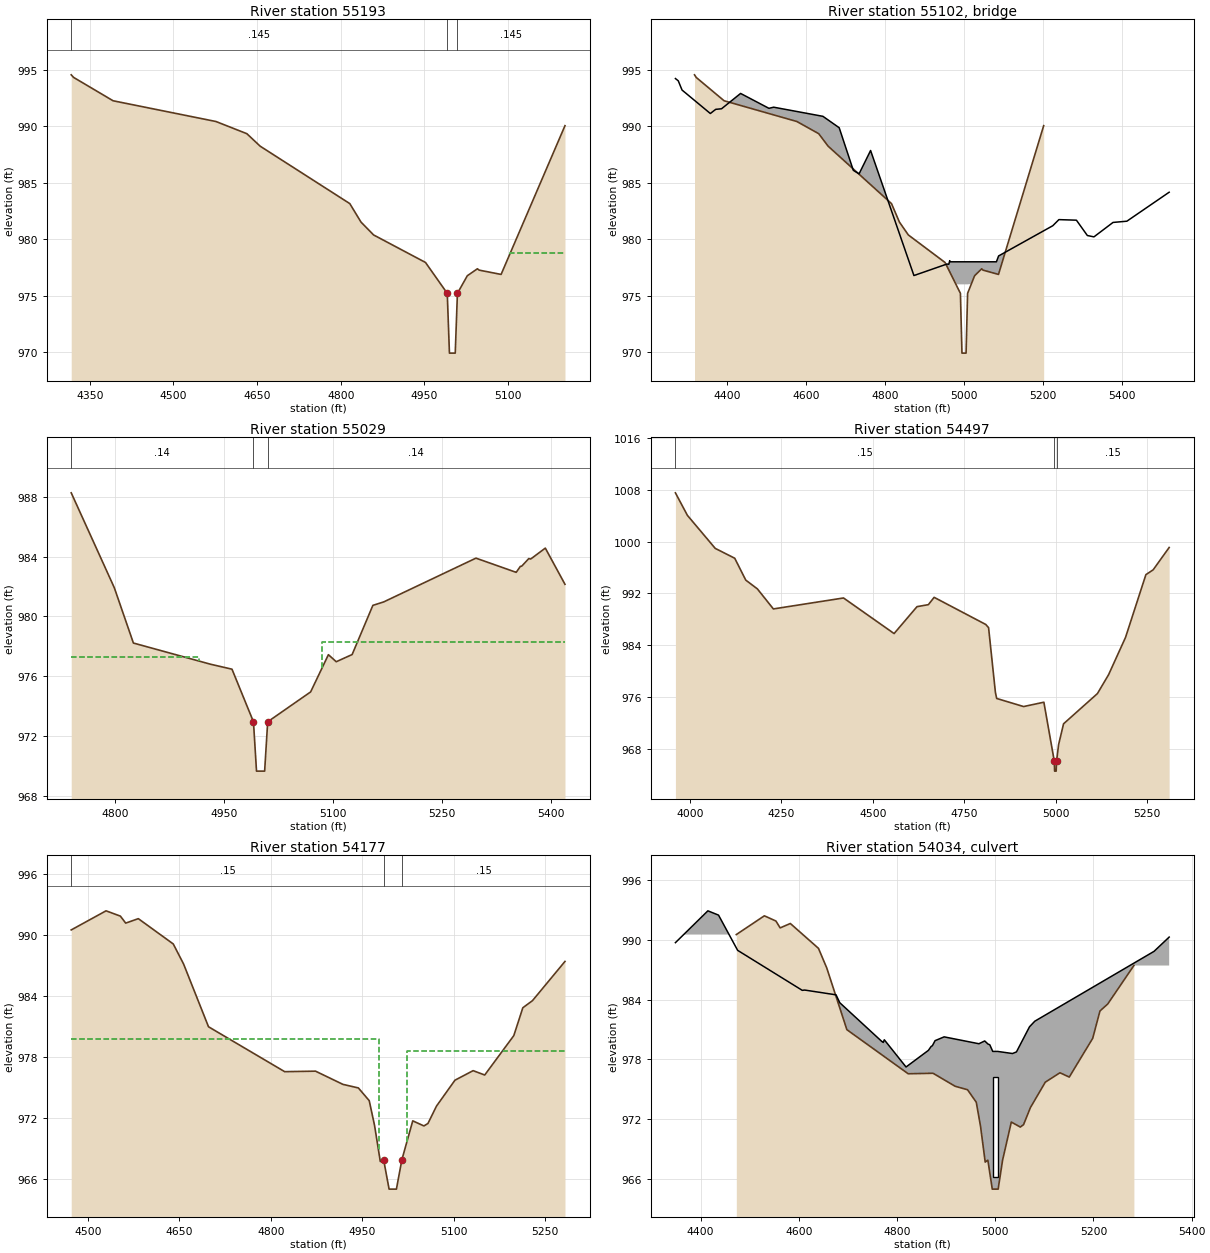
Type RM Length L Ch R = 1 ,55193   ,164,164,164
BEGIN DESCRIPTION:
Georges Creek 110.0
END DESCRIPTION:
XS GIS Cut Line= 3
      1517536.27      1097928.13      1517787.49      1097241.47
       1517720.5      1097020.96
#Sta/Elev= 19
  4316.9  994.58  4321.2  994.35  4391.9  992.28  4576.3  990.44  4631.7  989.36
  4655.6  988.25  4816.2  983.16  4836.3  981.52  4858.9  980.38  4951.9  977.94
  4990.9   975.2  4994.8   969.9  5005.2   969.9  5009.1   975.2  5026.8  976.76
  5044.9  977.38  5048.1  977.26  5087.4  976.88  5201.9  990.07
#Mann= 3 ,-1,0
  4316.9    .145       0  4990.9    .049       0  5009.1    .145       0
#XS Ineff= 2 , 0
            4897  977.07    5103          978.81
Permanent Ineff=
       F       F
Bank Sta=4990.9,5009.1
XS Rating Curve= 0 ,0
Exp/Cntr=0.5,0.3

Type RM Length L Ch R = 3 ,55102   ,,,
BEGIN DESCRIPTION:
N. Gray Haven Lane - TOR
Structure ID: LDS_GC_15
Approximate Survey Structure
END DESCRIPTION:
Bridge Culvert--1,0,-1,-1, 0
Deck Dist Width WeirC Skew NumUp NumDn MinLoCord MaxHiCord MaxSubmerge Is_Ogee
84.5,13,3,0, 34, 34, , , , 0, 1,1,,
  4268.5  4275.7  4285.3    4357  4370.7  4385.4  4433.7  4505.5  4517.6  4642.4
  4683.6  4719.4    4734  4763.2  4868.4    4873  4956.7  4961.4  4963.8  4964.2
  4981.5  4981.5  5018.5  5018.5  5082.1  5087.7  5225.1  5240.5  5284.9  5312.6
  5329.3  5377.7  5412.8    5520
  994.25  994.05  993.23  991.15  991.52  991.57  992.93  991.61  991.71   990.9
  989.89  986.11   985.8  987.87  977.25  976.78   977.8  977.78   978.1     978
     978     978     978     978     978  978.52   981.2  981.74  981.69  980.33
  980.21  981.49   981.6  984.17
   949.9   949.9   949.9   949.9   949.9   949.9   949.9   949.9   949.9   949.9
   949.9   949.9   949.9   949.9   949.9   949.9   949.9   949.9   949.9   949.9
   949.9     976     976   949.9   949.9   949.9   949.9   949.9   949.9   949.9
   949.9   949.9   949.9   949.9
  4268.5  4275.7  4285.3    4357  4370.7  4385.4  4433.7  4505.5  4517.6  4642.4
  4683.6  4719.4    4734  4763.2  4868.4    4873  4956.7  4961.4  4963.8  4964.2
  4981.5  4981.5  5018.5  5018.5  5082.1  5087.7  5225.1  5240.5  5284.9  5312.6
  5329.3  5377.7  5412.8    5520
  994.25  994.05  993.23  991.15  991.52  991.57  992.93  991.61  991.71   990.9
  989.89  986.11   985.8  987.87  977.25  976.78   977.8  977.78   978.1     978
     978     978     978     978     978  978.52   981.2  981.74  981.69  980.33
  980.21  981.49   981.6  984.17
   949.9   949.9   949.9   949.9   949.9   949.9   949.9   949.9   949.9   949.9
   949.9   949.9   949.9   949.9   949.9   949.9   949.9   949.9   949.9   949.9
   949.9     976     976   949.9   949.9   949.9   949.9   949.9   949.9   949.9
   949.9   949.9   949.9   949.9
Abutment Skew #Up #Dn= , 2 , 2
  4981.5  4982.5
     976  976.29
  4981.5  4982.5
     976  975.44
Abutment Skew #Up #Dn= , 2 , 2
  5017.5  5018.5
  976.82     976
  5017.5  5018.5
  971.88     976
BR Coef=-1 ,-1 , 0 ,1.25, 0 ,,,0.8,0,2,0,
WSPro=,,,, 1 ,,,, 0 ,,,, 0 ,,,,-1 ,-1 ,-1 , 0 , 0 , 0 , 0 , 0
BC Design=,, 0 ,, 0 ,,,,,,
BC HTab HWMax=994.58
BC Use User HTab Curves=0
BC User HTab FreeFlow(D)= 0

Type RM Length L Ch R = 1 ,55029   ,532,532,532
BEGIN DESCRIPTION:
Georges Creek 109.5
END DESCRIPTION:
XS GIS Cut Line= 3
      1517644.46      1097990.65      1517923.68      1097348.14
      1518004.74      1096831.74
#Sta/Elev= 24
    4739  988.27  4798.4  981.92  4824.7  978.22  4931.2   976.8  4960.6  976.47
  4990.2  972.95  4994.4  969.65  5005.6  969.65  5009.8  972.95    5069  974.95
  5093.5  977.44  5104.3  976.97  5126.2  977.45  5154.8  980.74  5169.7  980.97
  5296.9   983.9  5352.3  982.95  5352.8  982.98  5358.1  983.35  5359.9  983.36
  5369.7  983.87  5372.3  983.84  5392.5  984.57  5419.6  982.15
#Mann= 3 ,-1,0
    4739     .14       0  4990.2    .048       0  5009.8     .14       0
#XS Ineff= 2 , 0
            4915  977.29    5085          978.27
Permanent Ineff=
       F       F
Bank Sta=4990.2,5009.8
XS Rating Curve= 0 ,0
Exp/Cntr=0.5,0.3

Type RM Length L Ch R = 1 ,54497   ,320,320,320
BEGIN DESCRIPTION:
Georges Creek 109.0
END DESCRIPTION:
XS GIS Cut Line= 3
      1517616.27      1098342.77       1518347.8      1097604.42
      1518576.02      1097394.72
#Sta/Elev= 30
  3960.6 1007.51  3993.3 1004.04  4069.4  998.94  4122.7  997.42  4152.8  994.05
  4184.6  992.69  4228.3   989.6    4420  991.29  4558.2   985.8  4620.8  989.95
  4651.9  990.26  4667.6  991.39  4808.8   987.2  4816.4  986.71    4835  976.75
  4838.5  975.79  4912.1  974.54  4967.5  975.21  4996.1  966.08  4996.8  964.58
  5001.1  964.58  5002.1  966.08  5007.8  968.68  5021.3  971.88  5113.8  976.54
  5144.3  979.45  5190.6   985.2  5246.3  994.89  5266.1  995.63  5309.9  999.08
#Mann= 3 ,-1,0
  3960.6     .15       0  4996.1     .05       0  5002.1     .15       0
Bank Sta=4996.1,5002.1
XS Rating Curve= 0 ,0
Exp/Cntr=0.5,0.3

Type RM Length L Ch R = 1 ,54177   ,308,308,308
BEGIN DESCRIPTION:
Georges Creek 108.0
END DESCRIPTION:
XS GIS Cut Line= 4
      1518098.47      1098010.81      1518543.93      1097858.39
      1518625.26       1097778.4      1518571.28      1097560.32
#Sta/Elev= 30
  4472.8  990.51  4529.9  992.39  4553.4  991.87  4562.1  991.18  4582.8  991.62
  4640.1  989.13    4657  987.16  4697.9  980.98  4822.8  976.56  4873.4  976.61
  4918.3  975.31  4943.6  974.96  4961.4  973.71  4970.1  971.29  4979.6  967.71
    4985   967.9    4994     965    5006     965    5015   967.9  5032.8  971.72
  5051.1  971.22  5057.7  971.46  5071.7  973.17    5102  975.72  5131.8  976.66
  5150.8  976.23  5198.5  980.11  5213.3  982.85  5229.1  983.55  5282.4  987.41
#Mann= 3 ,-1,0
  4472.8     .15       0    4985     .05       0    5015     .15       0
#XS Ineff= 2 , 0
            4977  979.81    5023          978.59
Permanent Ineff=
       F       F
Bank Sta=4985,5015
XS Rating Curve= 0 ,0
Exp/Cntr=0.5,0.3

Type RM Length L Ch R = 2 ,54034   ,,,
BEGIN DESCRIPTION:
Fleetwood Dr. 2 (Georges Cr.) - TOR
Structure ID: LDS_GC_14
Approximate Survey Structure
END DESCRIPTION:
Bridge Culvert--1,0,-1,-1, 0
Deck Dist Width WeirC Skew NumUp NumDn MinLoCord MaxHiCord MaxSubmerge Is_Ogee
18,250,3,0, 32, 32, , , , 0, 1,1,,
  4348.8  4414.9  4436.6  4475.5  4607.1  4612.1  4675.9  4683.5  4768.6    4769
  4769.5  4771.4    4772  4774.1  4818.4    4864  4869.5    4872  4877.5    4896
  4966.8  4978.6  4985.5  4988.9    4995    5005  5035.1  5043.2  5069.8  5080.6
  5323.4  5354.2
   989.7  992.89  992.46  988.93  984.92  984.95  984.47  983.68  979.82  979.82
  979.78  979.73   979.7  979.97  977.24  978.91   979.3  979.37  979.88  980.26
  979.57  979.85  979.53  979.47   978.8   978.8  978.59  978.75  981.27  981.83
  988.83  990.26
  943.13  943.13  943.13  943.13  943.13  943.13  943.13  943.13  943.13  943.13
  943.13  943.13  943.13  943.13  943.13  943.13  943.13  943.13  943.13  943.13
  943.13  943.13  943.13  943.13  943.13  943.13  943.13  943.13  943.13  943.13
  943.13  943.13
  4348.8  4414.9  4436.6  4475.5  4607.1  4612.1  4675.9  4683.5  4768.6    4769
  4769.5  4771.4    4772  4774.1  4818.4    4864  4869.5    4872  4877.5    4896
  4966.8  4978.6  4985.5  4988.9    4995    5005  5035.1  5043.2  5069.8  5080.6
  5323.4  5354.2
   989.7  992.89  992.46  988.93  984.92  984.95  984.47  983.68  979.82  979.82
  979.78  979.73   979.7  979.97  977.24  978.91   979.3  979.37  979.88  980.26
  979.57  979.85  979.53  979.47   978.8   978.8  978.59  978.75  981.27  981.83
  988.83  990.26
  941.88  941.88  941.88  941.88  941.88  941.88  941.88  941.88  941.88  941.88
  941.88  941.88  941.88  941.88  941.88  941.88  941.88  941.88  941.88  941.88
  941.88  941.88  941.88  941.88  941.88  941.88  941.88  941.88  941.88  941.88
  941.88  941.88
Culvert=2,10,10,250,0.015,0.4,1,8,1,966.2,5000,964.95,5000,Culvert #1  , 0 ,18
    5000    5000
BC Culvert Barrel=1,,0
Culvert Bottom n=0.015
BC Design=,, 0 ,, 0 ,,,,,,
BC HTab HWMax=992.39
BC Use User HTab Curves=0
BC User HTab FreeFlow(D)= 0