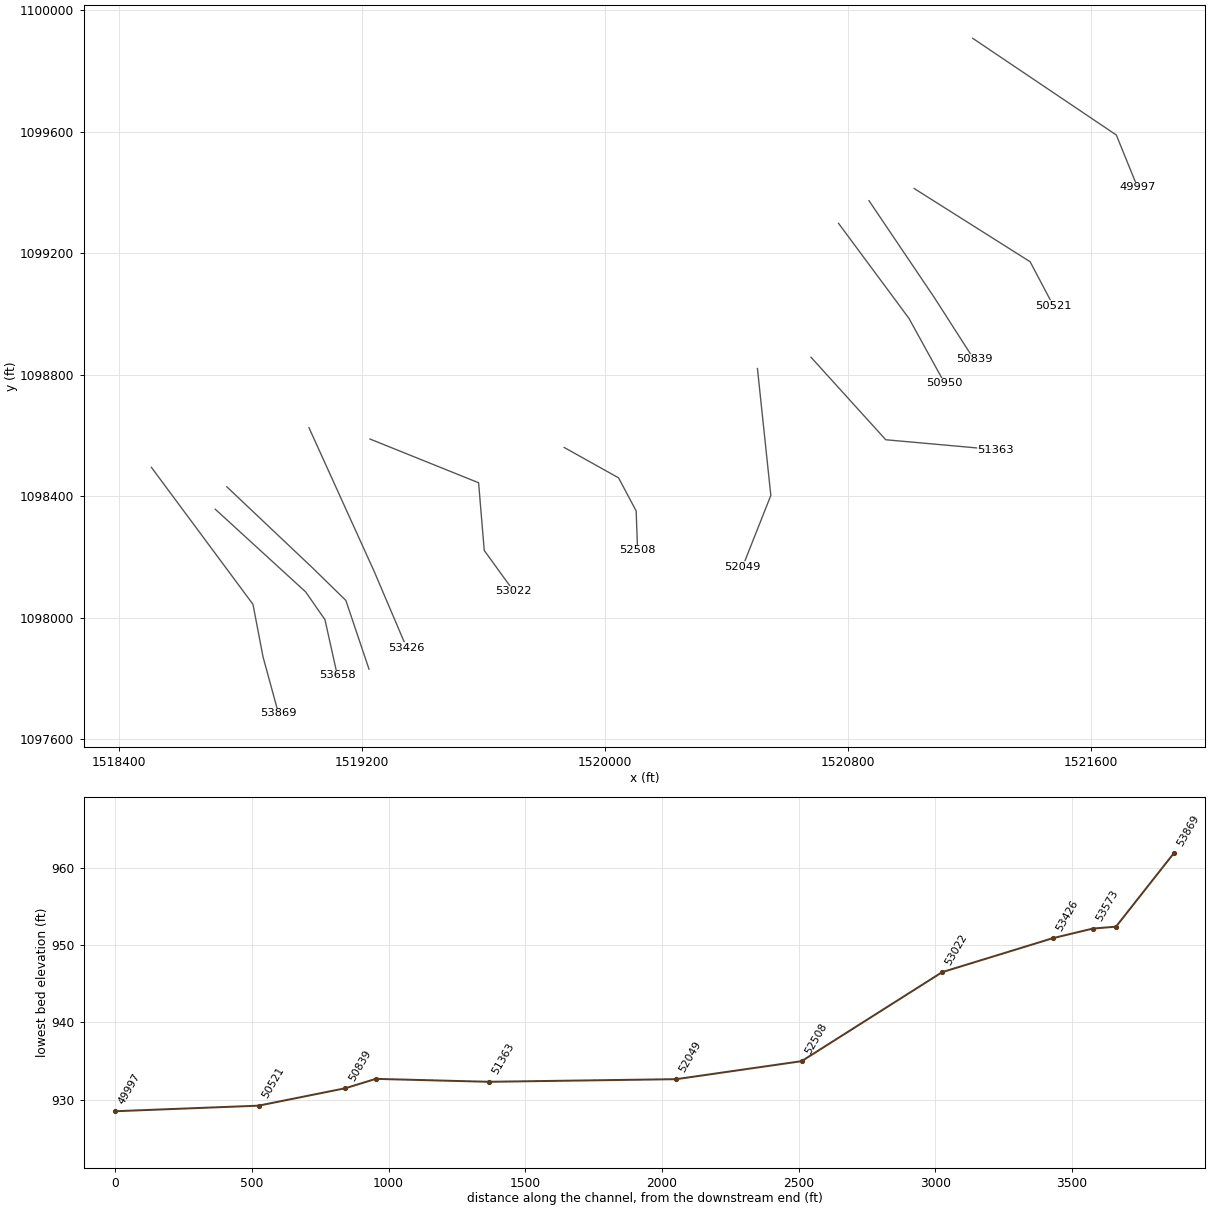
HEC-RAS study GeorgesCreek.prj: Georges Creek Limited Detail Study

--- GeorgesCreek.g06 (geometry) --- (continued)

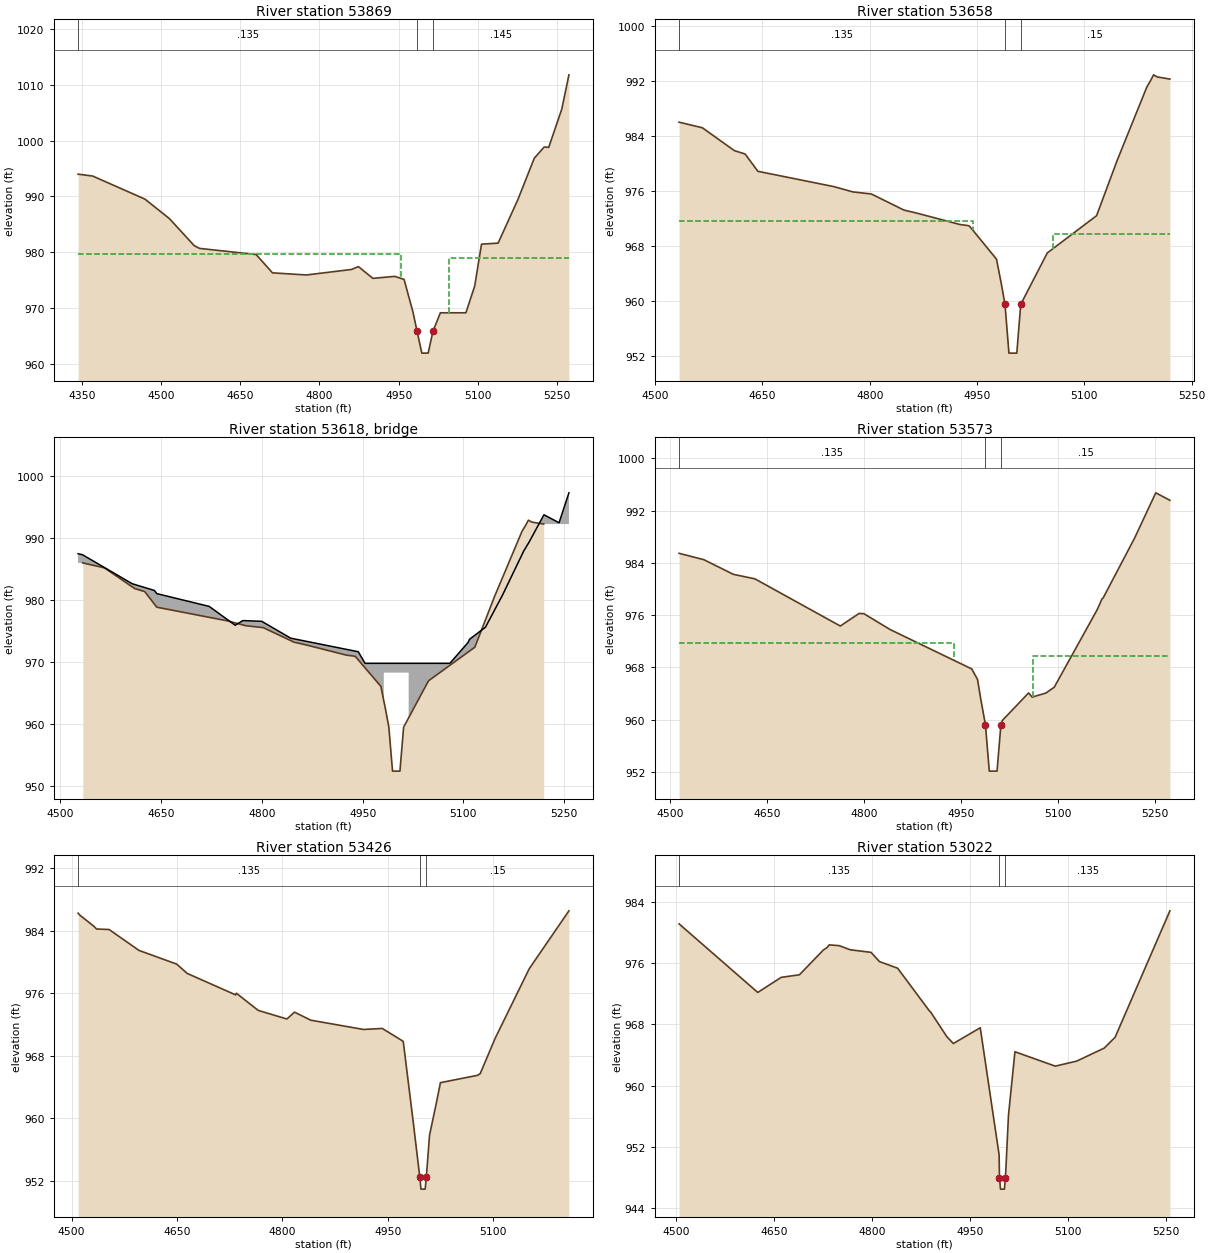
Type RM Length L Ch R = 1 ,53869   ,211,211,211
BEGIN DESCRIPTION:
Georges Creek 107.9
END DESCRIPTION:
XS GIS Cut Line= 4
      1518506.19      1098494.64      1518840.58      1098043.69
      1518873.58      1097871.06       1518924.5      1097684.66
#Sta/Elev= 30
  4342.4  994.01    4370  993.67  4469.1  989.53  4515.5  986.03  4562.6  981.17
  4572.8  980.68  4679.9  979.58  4710.9  976.29  4775.3  975.91  4860.7   976.9
  4873.8  977.41  4901.2   975.3  4942.5  975.66  4960.3  975.12  4977.1  969.29
    4985  965.78    4994  961.88    5006  961.88    5015  965.78  5029.1  969.12
  5077.5  969.12  5094.2  973.92  5107.1  981.44  5138.6  981.63  5176.5  989.54
  5207.1  996.87  5225.9  998.88  5234.5  998.82  5259.3  1005.7  5272.8 1011.84
#Mann= 3 ,-1,0
  4342.4    .135       0    4985     .05       0    5015    .145       0
#XS Ineff= 2 , 0
            4955  979.69    5045          978.92
Permanent Ineff=
       F       F
Bank Sta=4985,5015
XS Rating Curve= 0 ,0
Exp/Cntr=0.5,0.3

Type RM Length L Ch R = 1 ,53658   ,85,85,85
BEGIN DESCRIPTION:
Georges Creek 107.7
END DESCRIPTION:
XS GIS Cut Line= 4
      1518716.49       1098356.7      1519014.06      1098084.56
      1519077.65        1097993.      1519118.34      1097809.88
#Sta/Elev= 27
  4533.4  986.01  4565.9   985.2  4610.7  981.87  4625.7  981.38  4643.6  978.86
  4749.9  976.63  4776.4  975.86  4802.2  975.56  4847.7  973.22  4865.9  972.77
  4925.9  971.12  4936.7  970.97  4939.3  970.89  4977.1  966.08  4983.6  962.63
    4989   959.5  4994.5   952.4  5005.5   952.4    5011   959.5  5048.1  966.98
    5117   972.4  5146.1  980.53  5187.2  991.11  5192.5  992.06  5196.7   992.9
  5201.9  992.59  5219.5  992.28
#Mann= 3 ,-1,0
  4533.4    .135       0    4989     .05       0    5011     .15       0
#XS Ineff= 2 , 0
            4944  971.58    5056           969.8
Permanent Ineff=
       F       F
Bank Sta=4989,5011
XS Rating Curve= 0 ,0
Exp/Cntr=0.5,0.3

Type RM Length L Ch R = 3 ,53618   ,,,
BEGIN DESCRIPTION:
Footbridge (Georges Cr.) - TOR
Structure ID: Footbridge (Georges Cr.)
Approximate Survey Structure
END DESCRIPTION:
Bridge Culvert--1,0,-1,-1, 0
Deck Dist Width WeirC Skew NumUp NumDn MinLoCord MaxHiCord MaxSubmerge Is_Ogee
37.5,5,3,0, 26, 26, , , , 0, 1,1,,
  4526.5    4533    4607  4640.1  4643.7  4721.6  4760.3  4771.7  4799.8  4842.9
  4943.5  4953.6  4981.5  4981.5  5018.5  5018.5  5079.8  5106.8  5109.1  5132.8
  5158.2  5189.8  5197.6  5219.8  5242.3    5257
  987.49  987.33  982.65  981.56  981.05  978.99  975.95   976.7  976.58  973.86
  971.67   969.8   969.8   969.8   969.8   969.8   969.8  973.15  973.68  975.63
  980.82  987.94  989.34  993.78  992.49  997.32
   932.4   932.4   932.4   932.4   932.4   932.4   932.4   932.4   932.4   932.4
   932.4   932.4   932.4   968.3   968.3   932.4   932.4   932.4   932.4   932.4
   932.4   932.4   932.4   932.4   932.4   932.4
  4526.5    4533    4607  4640.1  4643.7  4721.6  4760.3  4771.7  4799.8  4842.9
  4943.5  4953.6  4981.5  4981.5  5018.5  5018.5  5079.8  5106.8  5109.1  5132.8
  5158.2  5189.8  5197.6  5219.8  5242.3    5257
  987.49  987.33  982.65  981.56  981.05  978.99  975.95   976.7  976.58  973.86
  971.67   969.8   969.8   969.8   969.8   969.8   969.8  973.15  973.68  975.63
  980.82  987.94  989.34  993.78  992.49  997.32
   932.4   932.4   932.4   932.4   932.4   932.4   932.4   932.4   932.4   932.4
   932.4   932.4   932.4   968.3   968.3   932.4   932.4   932.4   932.4   932.4
   932.4   932.4   932.4   932.4   932.4   932.4
Abutment Skew #Up #Dn= , 2 , 2
  4981.5  4982.5
   968.3  963.43
  4981.5  4982.5
   968.3  963.28
Abutment Skew #Up #Dn= , 2 , 2
  5017.5  5018.5
  969.24   968.3
  5017.5  5018.5
   961.4   968.3
BR Coef=-1 ,-1 , 0 ,1.25, 0 ,,,0.8,0,2,0,
WSPro=,,,, 1 ,,,, 0 ,,,, 0 ,,,,-1 ,-1 ,-1 , 0 , 0 , 0 , 0 , 0
BC Design=,, 0 ,, 0 ,,,,,,
BC HTab HWMax=992.9
BC Use User HTab Curves=0
BC User HTab FreeFlow(D)= 0

Type RM Length L Ch R = 1 ,53573   ,147,147,147
BEGIN DESCRIPTION:
Gedorges Creek 107.5
END DESCRIPTION:
XS GIS Cut Line= 4
      1518754.64      1098430.45      1519036.95       1098163.4
      1519146.32      1098056.59      1519222.61      1097830.23
#Sta/Elev= 27
  4513.4  985.46  4551.7  984.49  4597.4  982.25    4631  981.55  4763.2  974.34
  4792.2  976.26  4799.7  976.23  4840.6  973.79  4966.8  967.78  4975.8  966.17
  4980.7  963.21    4988  959.25    4994  952.15    5006  952.15    5012  959.25
  5014.5  959.93  5054.9  964.11  5060.4  963.47  5081.7  964.09  5094.6  964.98
  5160.9  976.79  5165.9  977.88  5168.4  978.46  5170.3  978.62    5219  987.77
  5251.9  994.71  5273.8  993.57
#Mann= 3 ,-1,0
  4513.4    .135       0    4988     .05       0    5012     .15       0
#XS Ineff= 2 , 0
            4939  971.77    5061           969.8
Permanent Ineff=
       F       F
Bank Sta=4988,5012
XS Rating Curve= 0 ,0
Exp/Cntr=0.5,0.3

Type RM Length L Ch R = 1 ,53426   ,404,404,404
BEGIN DESCRIPTION:
Georges Creek 107.0
END DESCRIPTION:
XS GIS Cut Line= 3
        1519025.        1098625.      1519239.87      1098151.41
      1519346.64      1097900.72
#Sta/Elev= 30
  4509.2  986.23  4512.5  985.92    4532  984.53  4535.5   984.2  4553.3  984.14
  4595.9  981.46  4649.5  979.71  4664.3  978.52  4733.4  975.77  4734.4  975.98
  4765.5  973.78  4806.3  972.68  4817.1  973.56  4840.2  972.53  4915.3  971.34
    4942  971.47  4971.8  969.82  4985.9  959.56  4995.4   952.4    4997   950.9
    5003   950.9  5004.6   952.4  5009.2  957.81  5018.5  961.75  5024.7  964.53
  5077.5  965.47  5081.3  965.69  5102.6  970.22    5151  979.11  5207.5  986.53
#Mann= 3 ,-1,0
  4509.2    .135       0  4995.4     .05       0  5004.6     .15       0
Bank Sta=4995.4,5004.6
XS Rating Curve= 0 ,0
Exp/Cntr=0.3,0.1

Type RM Length L Ch R = 1 ,53022   ,514,514,514
BEGIN DESCRIPTION:
Georges Creek 106.0
END DESCRIPTION:
XS GIS Cut Line= 4
      1519225.94      1098587.78       1519583.4      1098443.87
      1519601.96      1098221.04      1519699.45      1098086.42
#Sta/Elev= 29
  4504.8  981.13  4625.3  972.18  4661.3  974.15  4689.1  974.48  4725.9  977.73
  4731.5  978.04  4734.7  978.39  4750.2  978.28  4766.8  977.75  4798.7  977.41
  4811.8   976.2  4839.5  975.34  4888.3  969.75  4890.2   969.6  4914.8  966.41
  4924.8  965.51    4966  967.57  4994.9  950.97  4995.4  948.01    4997  946.51
    5003  946.51  5004.6  948.01  5009.2  956.12  5019.1  964.44  5080.9  962.56
  5113.8  963.22  5155.9  964.92  5172.5  966.33  5256.4  982.83
#Mann= 3 ,-1,0
  4504.8    .135       0  4995.4     .05       0  5004.6    .135       0
Bank Sta=4995.4,5004.6
XS Rating Curve= 0 ,0
Exp/Cntr=0.3,0.1

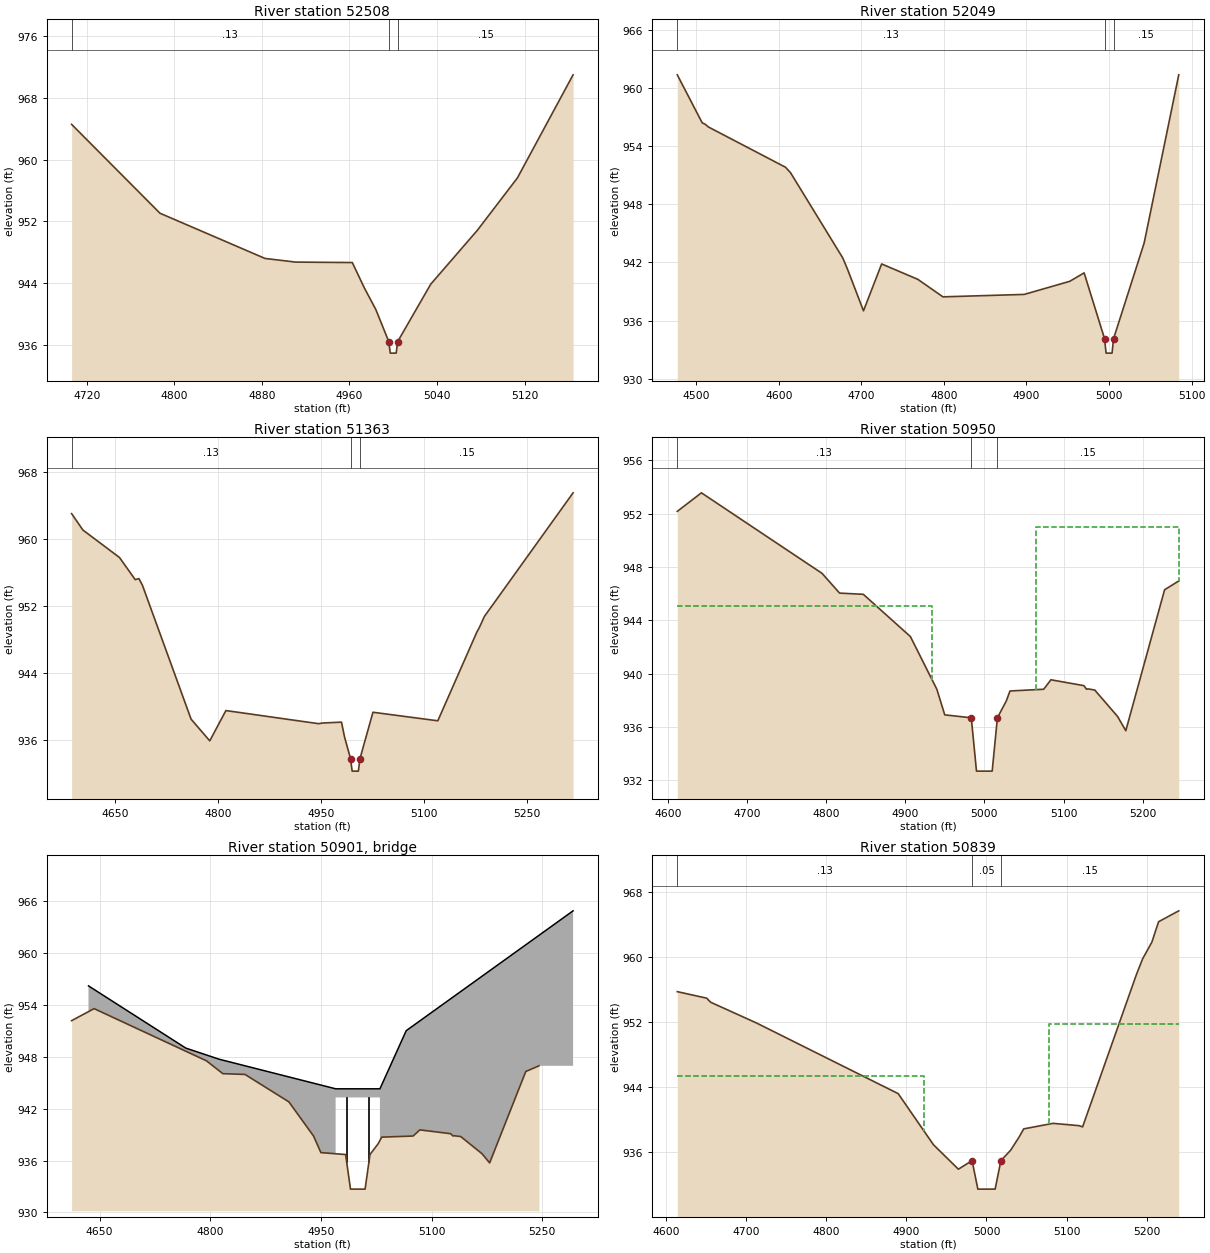
Type RM Length L Ch R = 1 ,52508   ,459,459,459
BEGIN DESCRIPTION:
Georges Creek 105.0
END DESCRIPTION:
XS GIS Cut Line= 4
      1519865.41      1098559.93      1520044.14      1098460.12
      1520102.17      1098351.03      1520106.81      1098221.04
#Sta/Elev= 15
    4706  964.54  4786.8  953.06  4882.8  947.22  4910.7  946.75  4962.6  946.69
  4973.4  943.47  4984.1  940.62  4995.9  936.49  4997.3  934.99  5002.7  934.99
  5004.1  936.49  5034.3   943.9  5076.8  950.84  5113.5  957.62  5164.4  970.94
#Mann= 3 ,-1,0
    4706     .13       0  4995.9     .05       0  5004.1     .15       0
Bank Sta=4995.9,5004.1
XS Rating Curve= 0 ,0
Exp/Cntr=0.3,0.1

Type RM Length L Ch R = 1 ,52049   ,686,686,686
BEGIN DESCRIPTION:
Georges Creek 104.0
END DESCRIPTION:
XS GIS Cut Line= 3
      1520501.41       1098819.9      1520545.51      1098402.09
      1520452.66      1098167.66
#Sta/Elev= 21
  4477.1  961.34  4507.3  956.39  4510.8  956.25  4514.7  955.97  4608.1  951.82
  4614.2  951.26  4677.5  942.47  4683.3   941.3  4702.6  937.02  4724.6  941.85
  4768.5  940.26  4798.8  938.46  4897.2  938.71  4952.4  940.06  4969.8  940.93
  4994.5  934.16  4996.4  932.66  5003.6  932.66  5005.5  934.16  5042.5  944.01
  5084.4  961.34
#Mann= 3 ,-1,0
  4477.1     .13       0  4994.5     .05       0  5005.5     .15       0
Bank Sta=4994.5,5005.5
XS Rating Curve= 0 ,0
Exp/Cntr=0.3,0.1

Type RM Length L Ch R = 1 ,51363   ,413,413,413
BEGIN DESCRIPTION:
Georges Creek 103.0
END DESCRIPTION:
XS GIS Cut Line= 3
      1520677.81      1098857.03      1520923.85      1098585.46
      1521285.95      1098552.96
#Sta/Elev= 24
  4587.1  963.02  4603.6  961.06  4656.8  957.79  4679.7  955.15  4685.1  955.27
  4690.2  954.48    4761  938.52  4788.2  935.93  4811.7  939.54  4946.4  937.98
  4953.6  938.06    4980  938.16  4984.4  936.39  4993.1  933.82  4995.5  932.32
  5004.5  932.32  5006.9  933.82  5024.8  939.05  5025.7  939.34  5120.2  938.32
  5177.1  948.91  5180.6  949.43    5188  950.76  5317.1   965.5
#Mann= 3 ,-1,0
  4587.1     .13       0  4993.1     .05       0  5006.9     .15       0
Bank Sta=4993.1,5006.9
XS Rating Curve= 0 ,0
Exp/Cntr=0.5,0.3

Type RM Length L Ch R = 1 ,50950   ,111,111,111
BEGIN DESCRIPTION:
Georges Creek 102.0
END DESCRIPTION:
XS GIS Cut Line= 4
      1520768.34      1099298.05      1520939.25      1099067.47
      1521000.45       1098984.7      1521117.89      1098771.37
#Sta/Elev= 24
  4612.1  952.18  4642.6  953.57    4795  947.53  4817.1  946.05  4847.1  945.96
  4906.6  942.79    4940  938.84    4950  936.92  4983.5   936.7  4990.1   932.7
  5009.9   932.7  5016.5   936.7  5027.8  937.97  5032.4  938.71    5075  938.84
  5084.1  939.55  5125.8  939.11  5129.1  938.84  5130.7  938.87  5139.5  938.78
  5168.3   936.8  5178.7  935.73  5227.7   946.3  5245.6  946.96
#Mann= 3 ,-1,0
  4612.1     .13       0  4983.5     .05       0  5016.5     .15       0
#XS Ineff= 2 , 0
          4934.5  945.07  5065.5          951.02
Permanent Ineff=
       F       F
Bank Sta=4983.5,5016.5
XS Rating Curve= 0 ,0
Exp/Cntr=0.5,0.3

Type RM Length L Ch R = 3 ,50901   ,,,
BEGIN DESCRIPTION:
Glenwood Rd. (Georges Cr.) - TOR
Structure ID: LDS_GC_12
Approximate Survey Structure
END DESCRIPTION:
Bridge Culvert--1,0,-1,-1, 0
Deck Dist Width WeirC Skew NumUp NumDn MinLoCord MaxHiCord MaxSubmerge Is_Ogee
35.5,27,3,0, 9, 9, , , , 0, 1,1,,
    4635  4766.8  4812.1    4970    4970    5030    5030  5065.6  5291.8
   956.2  949.01  947.72   944.3   944.3   944.3   944.3  951.02  964.88
   912.7   912.7   912.7   912.7   943.3   943.3   912.7   912.7   912.7
    4635  4766.8  4812.1    4970    4970    5030    5030  5065.6  5291.8
   956.2  949.01  947.72   944.3   944.3   944.3   944.3  951.02  964.88
   912.7   912.7   912.7   912.7   943.3   943.3   912.7   912.7   912.7
Pier Skew, UpSta & Num, DnSta & Num=  ,4985, 2 ,4985, 2 , 0 , 0 , 0 ,0,0
       1       1
   939.7   943.3
       1       1
  939.45   943.3
Pier Skew, UpSta & Num, DnSta & Num=  ,5015, 2 ,5015, 2 , 0 , 0 , 0 ,0,0
       1       1
   939.7   943.3
       1       1
  939.45   943.3
Abutment Skew #Up #Dn= , 2 , 2
    4970  4971.5
   943.3  934.28
    4970  4971.5
   943.3  933.51
Abutment Skew #Up #Dn= , 2 , 2
  5028.5    5030
  938.08   943.3
  5028.5    5030
  936.57   943.3
BR Coef=-1 ,-1 , 0 ,1.25, 0 ,,,0.8,0,2,0,
WSPro=,,,, 1 ,,,, 0 ,,,, 0 ,,,,-1 ,-1 ,-1 , 0 , 0 , 0 , 0 , 0
BC Design=,, 0 ,, 0 ,,,,,,
BC HTab HWMax=953.57
BC Use User HTab Curves=0
BC User HTab FreeFlow(D)= 0

Type RM Length L Ch R = 1 ,50839   ,318,318,318
BEGIN DESCRIPTION:
Georges Creek 101.5
END DESCRIPTION:
XS GIS Cut Line= 3
      1520868.69      1099372.46      1521084.33      1099052.67
      1521214.32      1098849.99
#Sta/Elev= 22
  4613.7  955.75  4650.4  954.95  4655.4  954.45  4712.9  951.89  4889.7  943.22
  4933.7  936.95  4964.9  933.94    4982  934.99  4989.2  931.49  5010.8  931.49
    5018  934.99    5030  936.25  5040.7  937.88  5046.5  938.89    5083  939.57
  5115.5  939.29  5120.1  939.14  5187.3  957.85    5195  959.77  5206.6  961.83
    5215  964.34  5240.2  965.68
#Mann= 3 ,-1,0
  4613.7     .13       0    4982     .05       0    5018     .15       0
#XS Ineff= 2 , 0
          4921.5  945.35  5078.5          951.81
Permanent Ineff=
       F       F
Bank Sta=4982,5018
XS Rating Curve= 0 ,0
Exp/Cntr=0.5,0.3

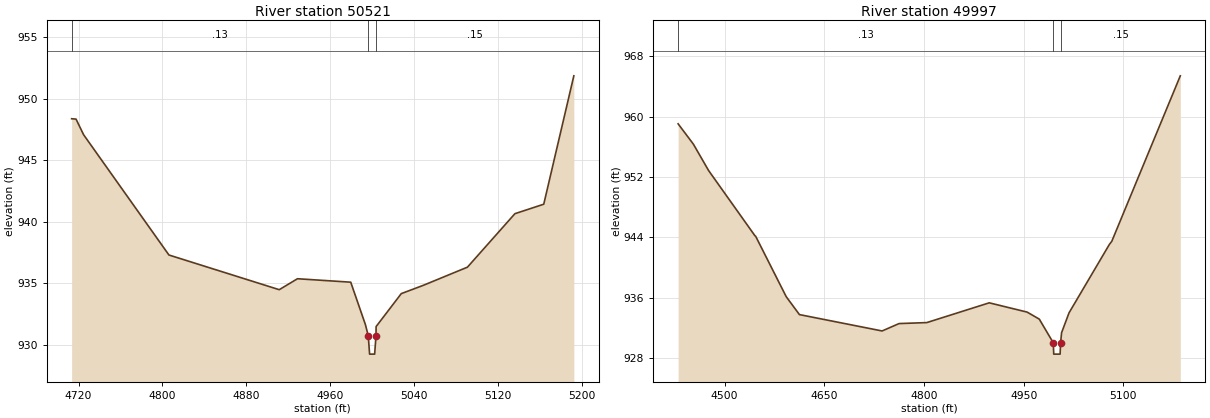
Type RM Length L Ch R = 1 ,50521   ,524,524,524
BEGIN DESCRIPTION:
Georges Creek 101.0
END DESCRIPTION:
XS GIS Cut Line= 3
      1521017.39      1099412.65      1521399.19      1099171.51
      1521475.55      1099026.83
#Sta/Elev= 19
  4713.4  948.37  4717.6  948.34  4724.8  947.07  4806.2  937.29  4911.4  934.47
  4928.8  935.36  4979.6  935.08  4993.6  931.63  4996.3  930.73  4997.6  929.23
  5002.4  929.23  5003.7  930.73  5003.8  931.47  5027.8  934.15    5049  934.83
  5090.9   936.3  5136.2  940.65  5163.7  941.42  5192.4  951.86
#Mann= 3 ,-1,0
  4713.4     .13       0  4996.3     .05       0  5003.7     .15       0
Bank Sta=4996.3,5003.7
XS Rating Curve= 0 ,0
Exp/Cntr=0.3,0.1

Type RM Length L Ch R = 1 ,49997   ,500,500,500
BEGIN DESCRIPTION:
Georges Creek 100.0
END DESCRIPTION:
XS GIS Cut Line= 3
       1521210.3      1099906.98        1521683.      1099588.67
      1521752.86      1099416.67
#Sta/Elev= 23
  4430.1  959.04  4453.1  956.34    4476  952.84  4545.7   944.2  4546.8  944.13
  4592.7  936.13  4612.6  933.75    4737  931.58  4762.5  932.56  4804.2  932.69
  4898.2  935.31  4955.2  934.08  4973.6  933.14  4975.6  932.83  4994.5  930.01
  4995.2  928.51  5004.8  928.51  5005.5  930.01    5007  931.35  5018.2  933.98
  5078.9  943.05  5082.5  943.46  5185.6   965.4
#Mann= 3 ,-1,0
  4430.1     .13       0  4994.5     .05       0  5005.5     .15       0
Bank Sta=4994.5,5005.5
XS Rating Curve= 0 ,0
Exp/Cntr=0.3,0.1