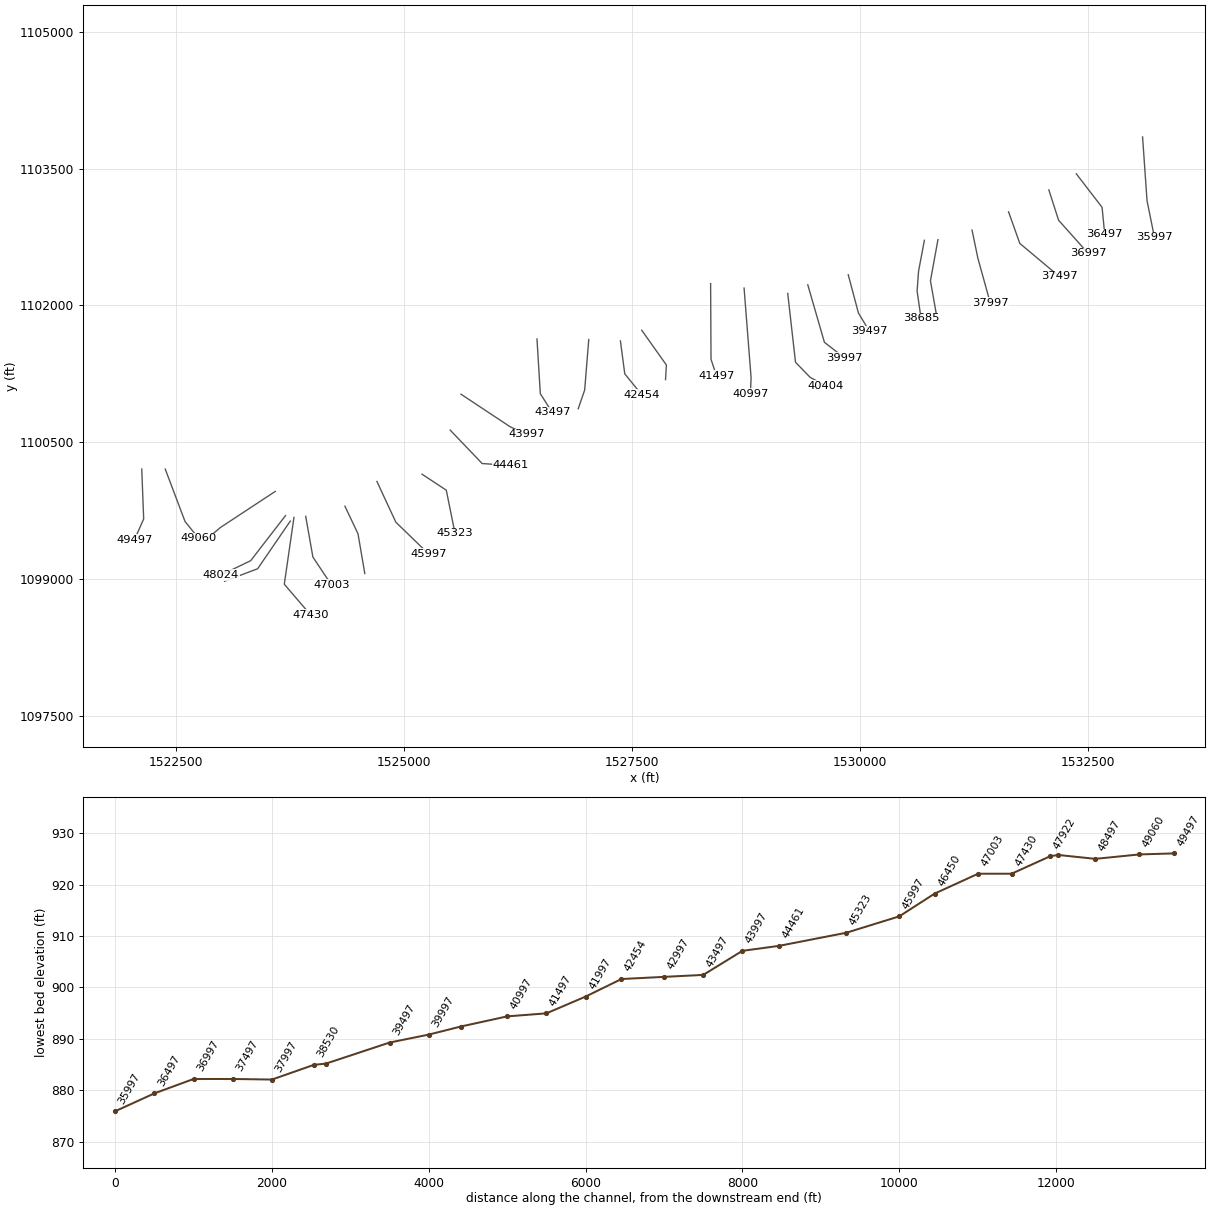
HEC-RAS study GeorgesCreek.prj: Georges Creek Limited Detail Study

--- GeorgesCreek.g06 (geometry) --- (continued)

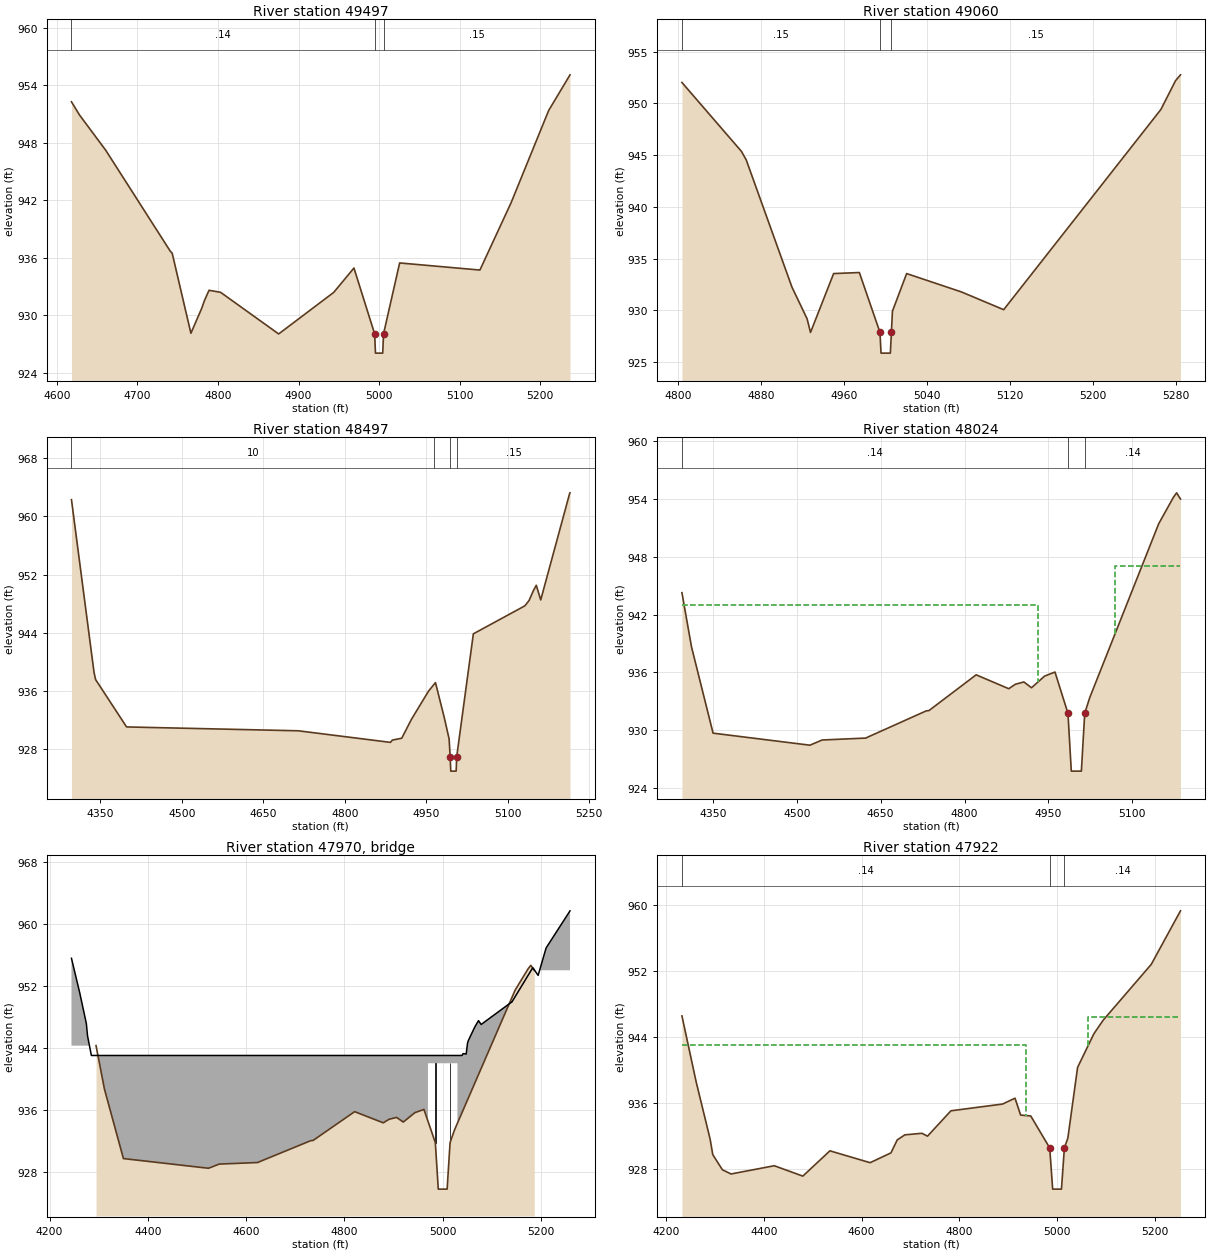
Type RM Length L Ch R = 1 ,49497   ,437,437,437
BEGIN DESCRIPTION:
Georges Creek 99.0
END DESCRIPTION:
XS GIS Cut Line= 3
      1522126.63      1100204.38      1522147.74      1099656.99
      1522046.25      1099428.72
#Sta/Elev= 22
  4618.3  952.26  4628.3  950.88  4660.8  947.21  4740.8   936.7  4743.3  936.47
  4766.5  928.13    4780  930.75  4783.3  931.54    4789  932.61  4803.3   932.4
  4875.4  928.06  4943.7  932.39  4968.8  934.93  4994.5  928.06  4995.5  926.06
  5004.5  926.06  5005.5  928.06  5025.5  935.46  5125.1  934.72  5163.8  941.74
  5210.4  951.35  5236.9  955.07
#Mann= 3 ,-1,0
  4618.3     .14       0  4994.5     .05       0  5005.5     .15       0
Bank Sta=4994.5,5005.5
XS Rating Curve= 0 ,0
Exp/Cntr=0.3,0.1

Type RM Length L Ch R = 1 ,49060   ,563,563,563
BEGIN DESCRIPTION:
Georges Creek 98.0
END DESCRIPTION:
XS GIS Cut Line= 3
      1522383.84      1100204.38      1522600.86      1099629.67
      1522749.57       1099444.8
#Sta/Elev= 19
  4803.5  952.02  4860.9  945.36  4865.5  944.54  4909.6  932.24  4924.2  929.18
  4927.5  927.86  4949.8  933.55  4974.6  933.65  4994.5  927.86  4995.5  925.86
  5004.5  925.86  5005.5  927.86  5006.5  929.91  5020.2  933.55  5072.9  931.78
  5113.8  930.06  5265.4  949.41  5279.5  952.19  5284.3  952.76
#Mann= 3 ,-1,0
  4803.5     .15       0  4994.5     .05       0  5005.5     .15       0
Bank Sta=4994.5,5005.5
XS Rating Curve= 0 ,0
Exp/Cntr=0.3,0.1

Type RM Length L Ch R = 1 ,48497   ,473,473,473
BEGIN DESCRIPTION:
Georges Creek 97.0
END DESCRIPTION:
XS GIS Cut Line= 3
      1523589.53      1099959.23      1522988.77      1099563.69
        1522825.        1099425.
#Sta/Elev= 27
    4297  962.29  4338.5  938.58  4341.4  937.58    4398  931.12  4398.9  931.07
  4714.5  930.54  4884.1  928.95  4887.5  929.26  4904.9  929.52  4922.7  932.11
  4954.2  935.99  4965.1  936.99    4967  937.16  4982.9  932.43  4992.1  929.42
    4994     927  4995.1     925    5005     925  5006.1     927  5036.7  943.86
  5131.6  947.71  5139.4  948.46  5147.1  949.78  5152.5  950.53  5160.7  948.52
  5213.8  963.11  5214.6  963.23
#Mann= 4 ,-1,0
    4297      10       0  4965.1     .15       0    4994     .05       0
  5006.1     .15       0
Bank Sta=4994,5006.1
XS Rating Curve= 0 ,0
Exp/Cntr=0.5,0.3

Type RM Length L Ch R = 1 ,48024   ,102,102,102
BEGIN DESCRIPTION:
Georges Creek 96.0
END DESCRIPTION:
XS GIS Cut Line= 3
      1523702.06      1099693.97      1523320.26      1099199.64
      1522994.72       1099042.9
#Sta/Elev= 25
  4294.5  944.27  4311.6  938.66  4350.2   929.7  4523.4  928.45  4545.3  928.99
  4623.8  929.19  4625.8  929.26  4731.5  932.01  4736.3  932.04  4820.8  935.75
  4879.1  934.31  4890.9  934.77  4906.2  935.01  4919.8  934.41  4943.3  935.62
  4961.8  936.04    4985  931.76    4991  925.76    5009  925.76    5015  931.76
    5024  933.39  5147.4  951.43  5173.8  954.18  5179.4  954.63  5186.3  953.99
#Mann= 3 ,-1,0
  4294.5     .14       0    4985    .049       0    5015     .14       0
#XS Ineff= 2 , 0
            4931     943    5069          947.08
Permanent Ineff=
       F       F
Bank Sta=4985,5015
XS Rating Curve= 0 ,0
Exp/Cntr=0.5,0.3

Type RM Length L Ch R = 3 ,47970   ,,,
BEGIN DESCRIPTION:
Jordan Rd. (Georges Cr.) - TOR
Structure ID: Jordan Rd. (Georges Cr.)
Approximate Survey Structure
END DESCRIPTION:
Bridge Culvert--1,0,-1,-1, 0
Deck Dist Width WeirC Skew NumUp NumDn MinLoCord MaxHiCord MaxSubmerge Is_Ogee
39,30,3,0, 24, 24, , , , 0, 1,1,,
  4244.5  4261.3  4274.8  4277.2    4285    4970    4970    5030    5030  5039.2
  5041.5  5047.8  5050.5    5052  5064.9  5072.8  5078.2  5140.1  5140.5  5181.9
  5183.5  5194.2  5210.4  5259.1
  955.54  951.09  947.12  945.53     943     943     943     943     943     943
  943.24  943.19   944.6   944.9  946.63   947.5     947  949.88  949.87  954.18
  954.31  953.33  956.87  961.66
  905.76  905.76  905.76  905.76  905.76  905.76     942     942  905.76  905.76
  905.76  905.76  905.76  905.76  905.76  905.76  905.76  905.76  905.76  905.76
  905.76  905.76  905.76  905.76
  4244.5  4261.3  4274.8  4277.2    4285    4970    4970    5030    5030  5039.2
  5041.5  5047.8  5050.5    5052  5064.9  5072.8  5078.2  5140.1  5140.5  5181.9
  5183.5  5194.2  5210.4  5259.1
  955.54  951.09  947.12  945.53     943     943     943     943     943     943
  943.24  943.19   944.6   944.9  946.63   947.5     947  949.88  949.87  954.18
  954.31  953.33  956.87  961.66
  905.76  905.76  905.76  905.76  905.76  905.76     942     942  905.76  905.76
  905.76  905.76  905.76  905.76  905.76  905.76  905.76  905.76  905.76  905.76
  905.76  905.76  905.76  905.76
Pier Skew, UpSta & Num, DnSta & Num=  ,4985, 2 ,4985, 2 , 0 , 0 , 0 ,0,0
       1       1
     938     942
       1       1
  937.75     942
Pier Skew, UpSta & Num, DnSta & Num=  ,5015, 2 ,5015, 2 , 0 , 0 , 0 ,0,0
       1       1
     938     942
       1       1
  937.75     942
Abutment Skew #Up #Dn= , 2 , 2
    4970  4972.5
     942  936.94
    4970  4972.5
     942  931.59
Abutment Skew #Up #Dn= , 2 , 2
  5027.5    5030
  934.85     942
  5027.5    5030
  934.04     942
BR Coef=-1 ,-1 , 0 ,1.25, 0 ,,,0.8,0,2,0,
WSPro=,,,, 1 ,,,, 0 ,,,, 0 ,,,,-1 ,-1 ,-1 , 0 , 0 , 0 , 0 , 0
BC Design=,, 0 ,, 0 ,,,,,,
BC HTab HWMax=954.63
BC Use User HTab Curves=0
BC User HTab FreeFlow(D)= 0

Type RM Length L Ch R = 1 ,47922   ,492,492,492
BEGIN DESCRIPTION:
Georges Creek 95.5
END DESCRIPTION:
XS GIS Cut Line= 3
      1523754.31      1099633.69      1523396.62      1099111.22
      1523034.91      1098974.58
#Sta/Elev= 30
  4232.6  946.54  4261.9  938.48  4290.2   931.6  4295.7   929.7  4315.4  927.86
    4333  927.35  4421.6  928.35  4479.9  927.09  4535.3  930.16  4617.6  928.72
  4660.2  929.91    4673  931.48  4688.6   932.1  4723.6  932.29    4735  931.94
  4782.9  935.02  4888.5  935.84    4914  936.55  4925.5   934.5  4946.2  934.39
    4985  930.51    4991  925.51    5009  925.51    5015  930.51  5022.1  931.71
    5042  940.29  5075.4  944.38  5094.2  946.01  5192.7   952.8  5252.5   959.3
#Mann= 3 ,-1,0
  4232.6     .14       0    4985    .049       0    5015     .14       0
#XS Ineff= 2 , 0
            4937     943    5063          946.38
Permanent Ineff=
       F       F
Bank Sta=4985,5015
XS Rating Curve= 0 ,0
Exp/Cntr=0.5,0.3

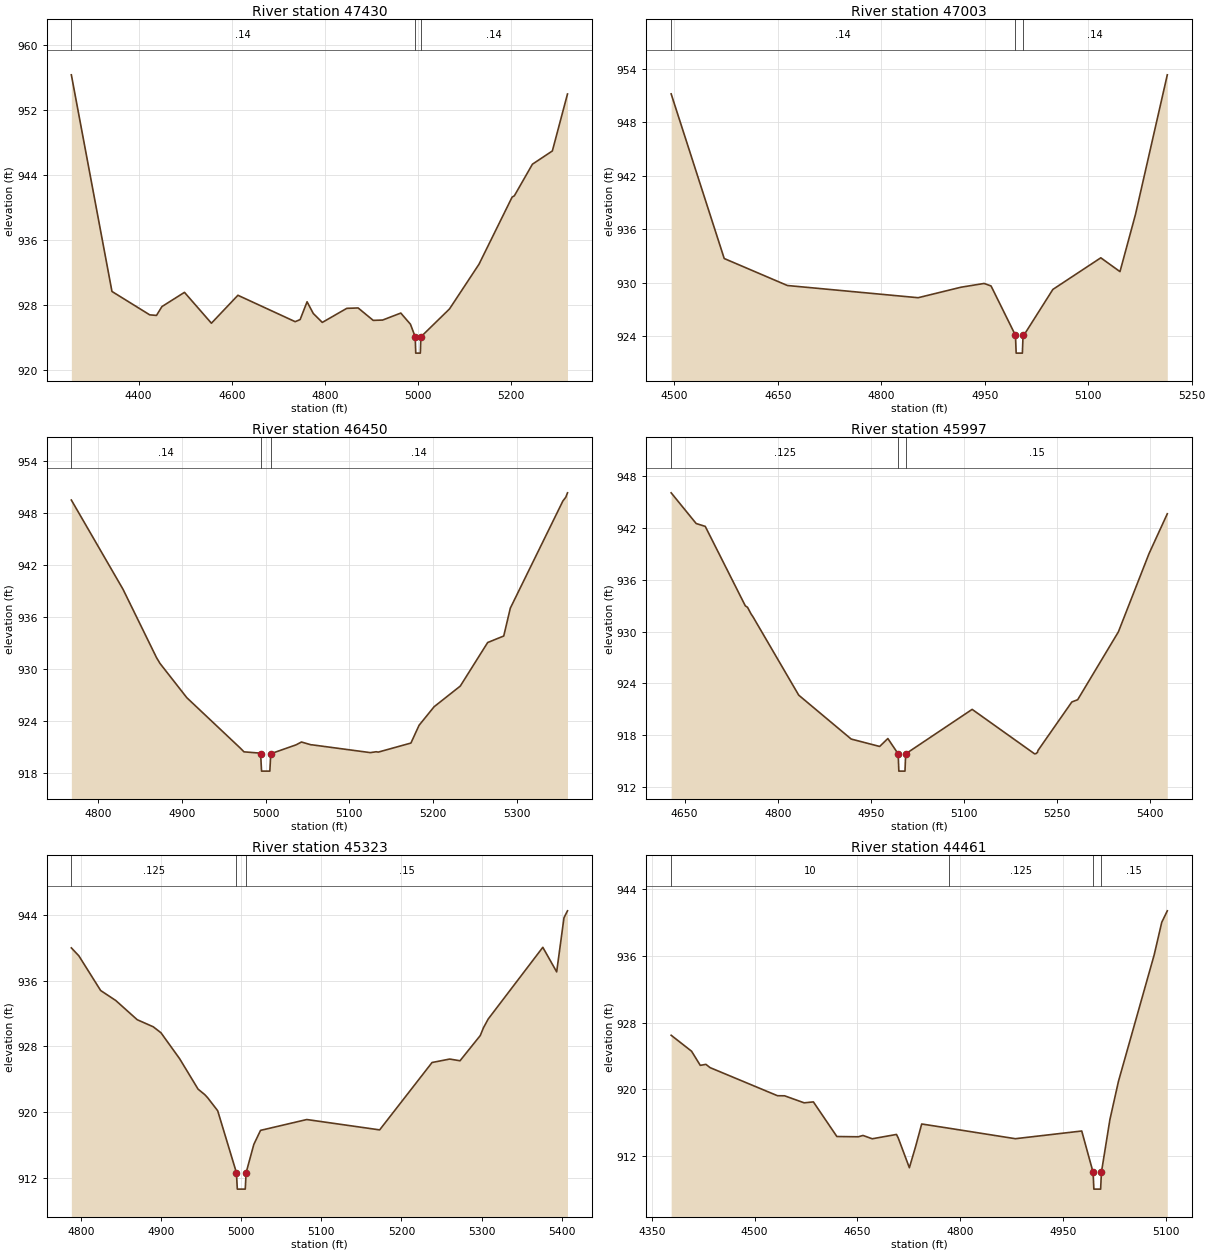
Type RM Length L Ch R = 1 ,47430   ,427,427,427
BEGIN DESCRIPTION:
Georges Creek 95.0
END DESCRIPTION:
XS GIS Cut Line= 3
       1523794.5      1099673.88       1523688.6      1098941.61
      1523975.59      1098606.78
#Sta/Elev= 30
  4255.7  956.36  4342.9   929.7    4424  926.82  4438.5  926.75  4450.2  927.84
  4498.6  929.59  4556.4  925.79  4613.3  929.23  4736.3  925.98  4746.9  926.24
  4761.8  928.43  4775.1  926.99  4794.5  925.89    4847  927.62  4871.4  927.67
  4903.8  926.14    4924  926.18    4963  927.04  4983.7  925.67    4994  924.11
  4995.1  922.11    5005  922.11  5006.1  924.11  5067.6  927.55  5130.9  933.05
    5202  941.31  5206.8  941.47  5245.6  945.36  5288.4  946.99  5320.9     954
#Mann= 3 ,-1,0
  4255.7     .14       0    4994    .049       0  5006.1     .14       0
Bank Sta=4994,5006.1
XS Rating Curve= 0 ,0
Exp/Cntr=0.3,0.1

Type RM Length L Ch R = 1 ,47003   ,553,553,553
BEGIN DESCRIPTION:
Georges Creek 94.0
END DESCRIPTION:
XS GIS Cut Line= 3
       1523923.1      1099685.94      1524002.17      1099239.24
      1524204.13       1098936.3
#Sta/Elev= 17
  4495.4  951.21  4572.3  932.73  4663.9   929.7  4853.4  928.33  4915.6  929.51
    4949  929.93  4959.1  929.65  4994.5  924.11  4995.5  922.11  5004.5  922.11
  5005.5  924.11  5006.6  924.11  5048.7  929.26  5118.2  932.81    5146  931.26
  5168.4  937.66  5214.6  953.35
#Mann= 3 ,-1,0
  4495.4     .14       0  4994.5    .049       0  5005.5     .14       0
Bank Sta=4994.5,5005.5
XS Rating Curve= 0 ,0
Exp/Cntr=0.3,0.1

Type RM Length L Ch R = 1 ,46450   ,453,453,453
BEGIN DESCRIPTION:
Georges Creek 93.0
END DESCRIPTION:
XS GIS Cut Line= 3
      1524352.95      1099797.29      1524496.44      1099494.35
      1524570.85      1099058.54
#Sta/Elev= 29
  4767.8  949.46  4829.6  939.18  4869.6  931.32  4873.7  930.66  4905.8  926.71
  4969.8   920.9  4974.1  920.48  4990.9  920.35    4994  920.26  4995.1  918.26
    5005  918.26  5006.1  920.26  5036.2  921.28  5042.8  921.61  5054.6  921.28
  5055.2  921.29  5125.1  920.39  5132.1  920.49  5134.6  920.45  5173.6  921.49
  5183.3  923.53  5201.3  925.67  5232.6  928.05  5265.3  933.06  5284.5  933.81
  5292.4  937.02  5355.2  949.35  5358.7  949.79  5360.7  950.29
#Mann= 3 ,-1,0
  4767.8     .14       0    4994    .049       0  5006.1     .14       0
Bank Sta=4994,5006.1
XS Rating Curve= 0 ,0
Exp/Cntr=0.3,0.1

Type RM Length L Ch R = 1 ,45997   ,674,674,674
BEGIN DESCRIPTION:
Georges Creek 92.0
END DESCRIPTION:
XS GIS Cut Line= 3
      1524703.72      1100068.35      1524910.97      1099621.88
      1525267.09      1099276.44
#Sta/Elev= 28
  4628.3  946.09  4668.6  942.53  4683.2   942.2  4747.8  932.98  4751.3  932.82
  4757.3  932.01  4759.9  931.74  4833.8  922.63  4918.3  917.54  4964.2  916.68
  4977.4   917.6    4994  915.82  4995.1  913.82    5005  913.82  5006.1  915.82
  5113.2  920.98  5213.3  915.85  5214.2  915.82  5216.7  915.87  5217.2  915.93
  5218.6     916  5218.8  916.13  5219.5  916.24  5273.8  921.84  5283.2   922.1
  5348.8  929.97  5398.2  939.05  5427.6  943.66
#Mann= 3 ,-1,0
  4628.3    .125       0    4994    .048       0  5006.1     .15       0
Bank Sta=4994,5006.1
XS Rating Curve= 0 ,0
Exp/Cntr=0.3,0.1

Type RM Length L Ch R = 1 ,45323   ,862,862,862
BEGIN DESCRIPTION:
Georges Creek 91.0
END DESCRIPTION:
XS GIS Cut Line= 3
        1525198.      1100148.07      1525463.74      1099972.68
       1525559.4      1099499.66
#Sta/Elev= 30
  4787.9     940  4797.3  939.03  4824.5  934.81  4843.3   933.6  4870.1  931.26
  4890.1   930.4  4899.8  929.67  4923.1  926.51  4946.1  922.81  4954.6  922.13
  4958.1  921.76  4970.6  920.18    4994  912.64  4995.1  910.64    5005  910.64
  5006.1  912.64  5015.7  916.08  5024.1  917.79  5081.8  919.11  5172.8  917.85
  5238.2  926.05  5260.3  926.47  5273.1  926.26  5298.4  929.33  5302.4  930.28
  5308.3  931.34  5376.5  940.07  5393.8  937.08  5402.9  943.66  5407.3  944.51
#Mann= 3 ,-1,0
  4787.9    .125       0    4994    .048       0  5006.1     .15       0
Bank Sta=4994,5006.1
XS Rating Curve= 0 ,0
Exp/Cntr=0.3,0.1

Type RM Length L Ch R = 1 ,44461   ,464,464,464
BEGIN DESCRIPTION:
Georges Creek 89.0
END DESCRIPTION:
XS GIS Cut Line= 3
      1525506.26      1100631.72      1525857.03        1100265.
      1526165.29      1100243.74
#Sta/Elev= 30
  4378.1  926.48  4407.9  924.57  4420.6  922.88  4428.8     923  4434.9  922.61
  4533.3  919.25  4543.7  919.24  4572.2   918.4  4585.7  918.51    4620  914.37
  4651.3  914.34  4658.1   914.5  4671.6   914.1    4707  914.62  4709.7  914.17
  4725.8  910.64    4735   913.2  4743.8  915.87    4783  915.37  4880.5  914.11
  4977.4  915.03    4994  910.08  4995.1  908.08    5005  908.08  5006.1  910.08
  5018.5  916.39    5031  920.97  5083.1  936.08  5094.2  939.99  5102.3  941.36
#Mann= 4 ,-1,0
  4378.1      10       0    4783    .125       0    4994    .048       0
  5006.1     .15       0
Bank Sta=4994,5006.1
XS Rating Curve= 0 ,0
Exp/Cntr=0.3,0.1

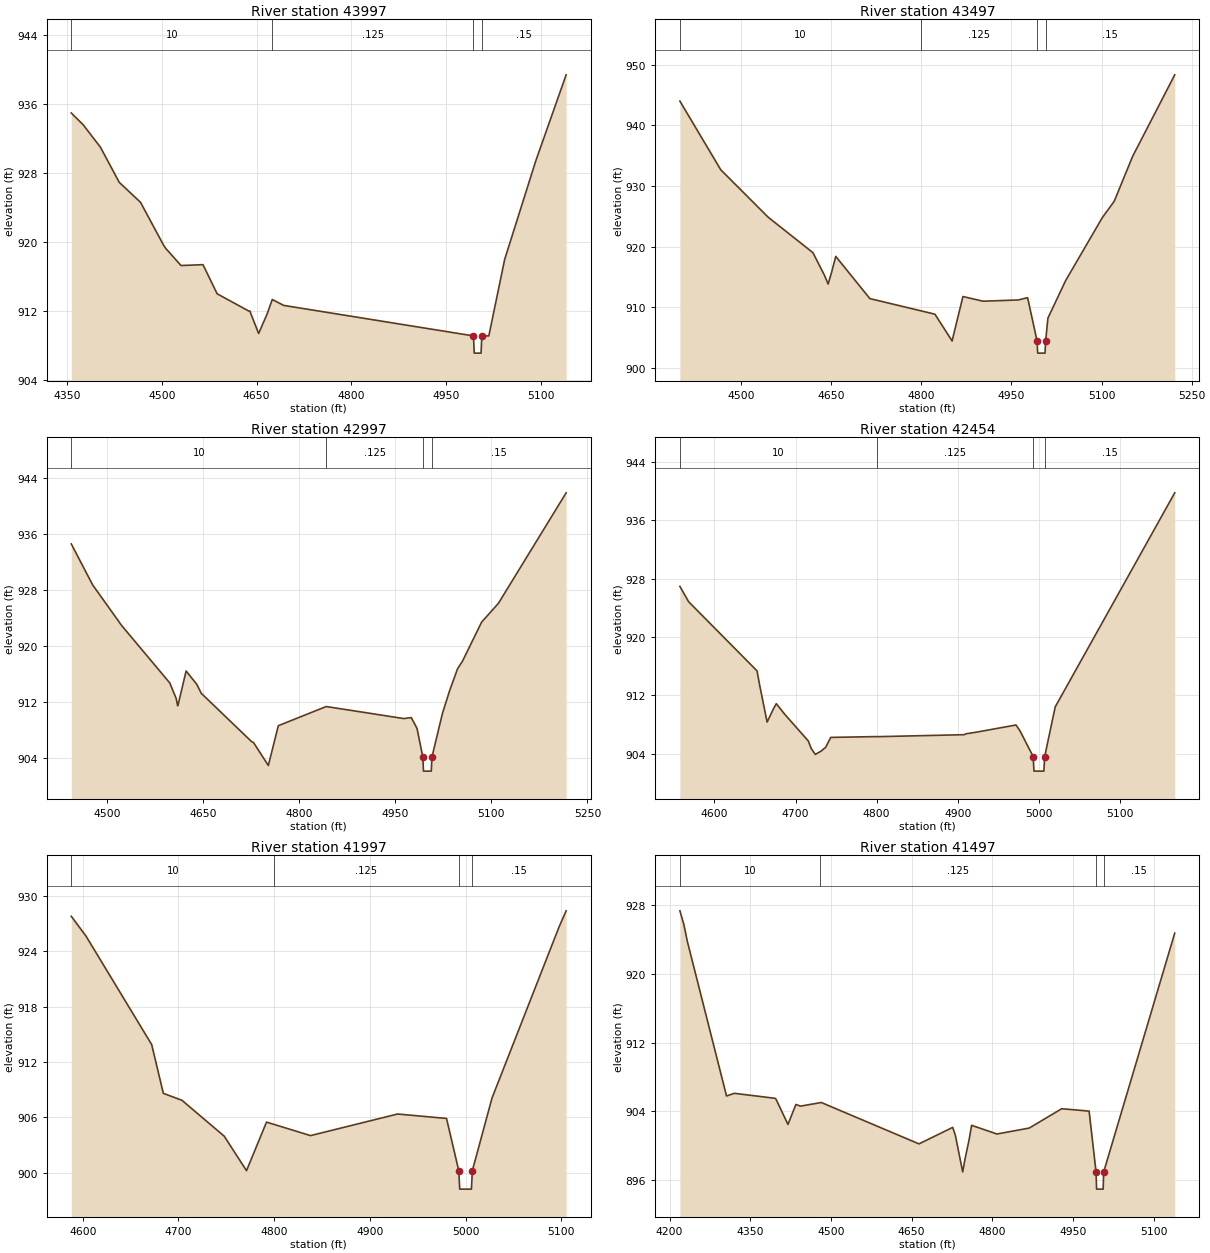
Type RM Length L Ch R = 1 ,43997   ,500,500,500
BEGIN DESCRIPTION:
Georges Creek 88.0
END DESCRIPTION:
XS GIS Cut Line= 3
        1525625.        1101025.      1526161.23      1100669.69
      1526340.68      1100583.88
#Sta/Elev= 26
  4356.7     935  4375.8  933.61  4402.9  931.02  4432.6  926.95  4466.3  924.63
  4502.9  919.64  4506.5  919.26  4530.4  917.29  4565.2  917.39  4587.6  914.01
  4637.6  912.01  4639.6     912  4640.8  911.73  4653.3   909.4  4666.8  911.68
  4674.9  913.35  4675.1  913.34    4693  912.66  4993.4  909.12  4994.6  907.12
  5005.4  907.12  5006.6  909.12  5017.7  909.12  5042.8     918  5091.9  929.41
  5140.1  939.43
#Mann= 4 ,-1,0
  4356.7      10       0  4675.1    .125       0  4993.4    .048       0
  5006.6     .15       0
Bank Sta=4993.4,5006.6
XS Rating Curve= 0 ,0
Exp/Cntr=0.3,0.1

Type RM Length L Ch R = 1 ,43497   ,500,500,500
BEGIN DESCRIPTION:
Georges Creek 87.0
END DESCRIPTION:
XS GIS Cut Line= 3
      1526457.61       1101630.9      1526494.17      1101030.89
        1526625.        1100825.
#Sta/Elev= 28
  4398.9     944    4467  932.65  4467.8  932.58  4545.6  924.86  4620.1  919.01
  4639.3  915.28  4645.4  913.83  4651.3  915.81  4658.1  918.39  4714.8  911.43
    4800  909.41    4823  908.86  4851.6  904.44  4854.5  905.66  4869.6  911.77
  4903.2     911  4961.7  911.21  4977.1  911.58  4992.9  904.44  4993.9  902.44
  5006.1  902.44  5007.1  904.44  5010.9  908.21  5040.2  914.37  5101.5  924.81
  5121.1  927.47  5151.7  934.87  5221.8  948.33
#Mann= 4 ,-1,0
  4398.9      10       0    4800    .125       0  4992.9    .048       0
  5007.1     .15       0
Bank Sta=4992.9,5007.1
XS Rating Curve= 0 ,0
Exp/Cntr=0.3,0.1

Type RM Length L Ch R = 1 ,42997   ,543,543,543
BEGIN DESCRIPTION:
Georges Creek 86.0
END DESCRIPTION:
XS GIS Cut Line= 3
        1527025.        1101625.       1526980.1      1101070.45
      1526909.36      1100865.57
#Sta/Elev= 29
  4443.6  934.53    4477  928.67  4522.1  922.89  4597.5  914.66  4607.5  912.44
  4609.8   911.4  4610.9  911.69    4623  916.37  4639.6  914.48  4646.6  913.19
  4725.3  906.28  4728.3  906.15  4751.5  902.87  4767.1  908.55  4841.9  911.29
  4963.2  909.57  4974.8  909.71  4983.8  908.17  4992.9  904.06  4993.9  902.06
  5006.1  902.06  5007.1  904.06  5023.6  910.33  5034.8  913.58  5047.2   916.7
  5054.8  917.77  5084.8  923.36    5111  926.04  5216.8  941.83
#Mann= 4 ,-1,0
  4443.6      10       0  4841.9    .125       0  4992.9    .048       0
  5007.1     .15       0
Bank Sta=4992.9,5007.1
XS Rating Curve= 0 ,0
Exp/Cntr=0.3,0.1

Type RM Length L Ch R = 1 ,42454   ,457,457,457
BEGIN DESCRIPTION:
Georges Creek 85.0
END DESCRIPTION:
XS GIS Cut Line= 3
      1527371.75      1101609.64      1527419.58      1101248.23
       1527605.6       1101019.7
#Sta/Elev= 29
  4557.5  926.94  4568.3  924.84  4652.6  915.37    4656   913.3    4665  908.36
  4673.2  910.25  4673.7  910.35  4676.3  910.88  4686.6  909.44  4715.7  905.78
  4719.4  904.73  4724.4  903.93  4731.5  904.38  4737.2  904.91  4743.4  906.26
    4800  906.37    4801  906.37  4801.5  906.36  4907.8  906.63    4910  906.75
  4922.1  906.96  4971.7  907.96  4976.6  907.17  4992.9  903.64  4993.9  901.64
  5006.1  901.64  5007.1  903.64  5020.1  910.44  5167.4  939.76
#Mann= 4 ,-1,0
  4557.5      10       0    4800    .125       0  4992.9    .048       0
  5007.1     .15       0
Bank Sta=4992.9,5007.1
XS Rating Curve= 0 ,0
Exp/Cntr=0.3,0.1

Type RM Length L Ch R = 1 ,41997   ,500,500,500
BEGIN DESCRIPTION:
Georges Creek 84.0
END DESCRIPTION:
XS GIS Cut Line= 3
       1527605.6      1101726.56      1527875.94      1101344.76
      1527866.03      1101184.46
#Sta/Elev= 19
    4588   927.8  4603.4  925.65    4672   913.9  4684.2  908.61  4703.6  907.86
  4747.8  903.97  4771.1  900.23    4792  905.49    4800  905.24    4838  904.03
    4929  906.37  4980.1  905.89  4992.9  900.23  4993.9  898.23  5006.1  898.23
  5007.1  900.23  5027.6  908.09  5097.8  926.67  5105.1  928.39
#Mann= 4 ,-1,0
    4588      10       0    4800    .125       0  4992.9    .048       0
  5007.1     .15       0
Bank Sta=4992.9,5007.1
XS Rating Curve= 0 ,0
Exp/Cntr=0.3,0.1

Type RM Length L Ch R = 1 ,41497   ,500,500,500
BEGIN DESCRIPTION:
Georges Creek 83.0
END DESCRIPTION:
XS GIS Cut Line= 3
       1528360.3      1102236.79      1528364.69      1101408.04
        1528425.        1101225.
#Sta/Elev= 28
  4219.3  927.33  4226.5  925.78  4233.1  923.79    4306   905.8  4320.6  906.11
  4396.1  905.53  4397.8  905.45  4420.2  902.49  4434.9  904.81  4443.6  904.62
    4480  905.02  4482.2  905.04  4663.8  900.23  4726.4  902.15  4731.4  901.22
    4745  896.97  4749.3  898.45    4757  900.74  4761.6  902.39  4808.7  901.38
  4868.7  902.07  4929.1  904.32    4980  904.04  4992.9  896.97  4993.9  894.97
  5006.1  894.97  5007.1  896.97  5139.2  924.74
#Mann= 4 ,-1,0
  4219.3      10       0    4480    .125       0  4992.9    .048       0
  5007.1     .15       0
Bank Sta=4992.9,5007.1
XS Rating Curve= 0 ,0
Exp/Cntr=0.3,0.1

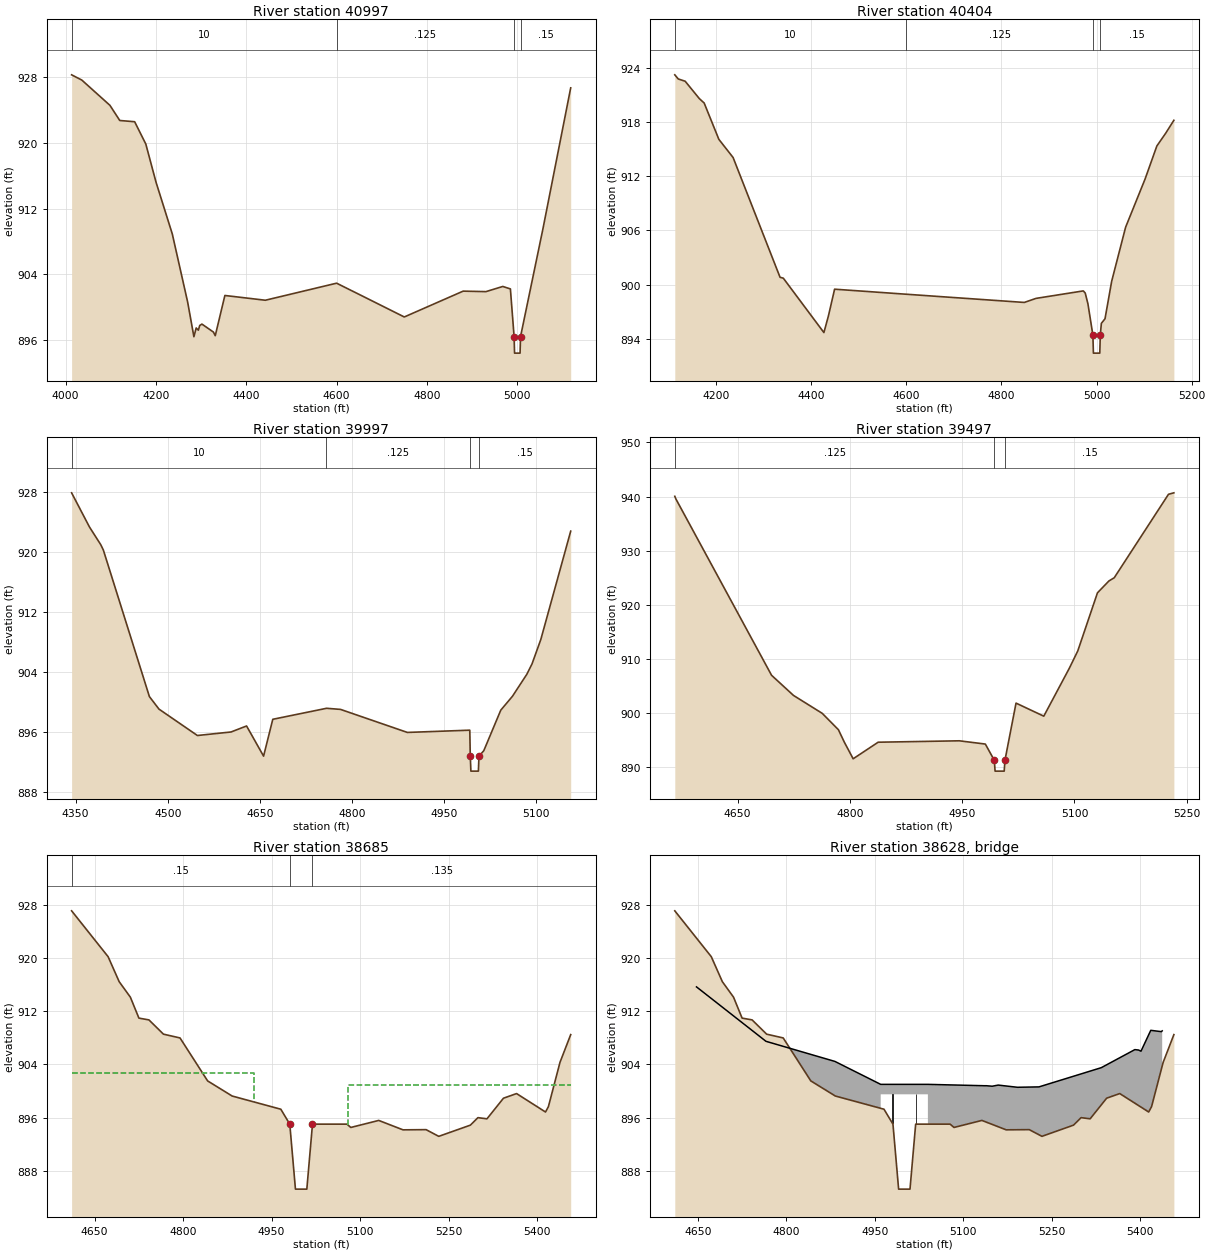
Type RM Length L Ch R = 1 ,40997   ,593,593,593
BEGIN DESCRIPTION:
Georges Creek 82.0
END DESCRIPTION:
XS GIS Cut Line= 3
      1528727.02      1102188.95      1528803.81      1101205.24
      1528796.12      1101030.33
#Sta/Elev= 30
  4013.3  928.32  4035.9  927.68  4098.1   924.6  4119.9  922.75  4152.9   922.6
  4177.5  919.89  4200.1  915.24  4236.2  908.91  4270.2   900.6    4284  896.38
  4289.1  897.45  4293.9  897.18  4296.9  897.75  4301.8  897.92  4327.2  896.95
  4331.3  896.51  4352.6  901.41  4442.2  900.83    4600  902.91  4749.8  898.79
  4880.1  901.94  4930.5  901.88  4967.9  902.51  4984.7  902.21  4992.9  896.38
  4993.9  894.38  5006.1  894.38  5007.1  896.38  5056.8  909.56  5118.2  926.73
#Mann= 4 ,-1,0
  4013.3      10       0    4600    .125       0  4992.9    .048       0
  5007.1     .15       0
Bank Sta=4992.9,5007.1
XS Rating Curve= 0 ,0
Exp/Cntr=0.3,0.1

Type RM Length L Ch R = 1 ,40404   ,407,407,407
BEGIN DESCRIPTION:
Georges Creek 81.0
END DESCRIPTION:
XS GIS Cut Line= 4
      1529205.36      1102130.49      1529290.39      1101375.79
      1529449.84      1101211.03      1529625.22      1101115.36
#Sta/Elev= 30
  4113.1  923.26  4120.4   922.8  4134.9  922.55  4164.6  920.63  4174.9  920.13
  4205.7  916.11  4235.7  914.09  4334.4  900.81  4341.3  900.71  4426.6  894.68
  4436.2  896.54  4449.1  899.49    4600  898.93    4848  898.02  4872.6  898.47
  4972.1   899.3  4976.1  899.06  4981.8  897.86  4992.2   894.4  4993.3   892.4
  5006.7   892.4  5007.8   894.4    5010   895.7  5017.7  896.21  5031.7  900.37
    5061  906.36  5101.9   911.7  5126.7  915.37  5145.1  916.77  5162.5  918.22
#Mann= 4 ,-1,0
  4113.1      10       0    4600    .125       0  4992.2    .048       0
  5007.8     .15       0
Bank Sta=4992.2,5007.8
XS Rating Curve= 0 ,0
Exp/Cntr=0.3,0.1

Type RM Length L Ch R = 1 ,39997   ,500,500,500
BEGIN DESCRIPTION:
Georges Creek 80.0
END DESCRIPTION:
XS GIS Cut Line= 3
        1529425.        1102225.      1529607.37      1101594.32
        1529825.        1101425.
#Sta/Elev= 27
  4343.5  927.95  4372.6  923.39    4391  921.03  4395.2  920.32  4470.2  900.78
  4485.8  899.11  4548.4  895.59  4603.2  896.06  4628.5  896.86  4656.2  892.84
  4671.2  897.75  4757.7   899.2  4758.8  899.22  4781.6  899.07  4890.4     896
  4992.1   896.3  4992.9  892.84  4993.9  890.84  5006.1  890.84  5007.1  892.84
  5014.9  893.56  5042.6  898.97  5061.6  900.82    5085  903.75  5093.5  905.14
  5107.8  908.39  5156.5  922.84
#Mann= 4 ,-1,0
  4343.5      10       0  4757.7    .125       0  4992.9    .048       0
  5007.1     .15       0
Bank Sta=4992.9,5007.1
XS Rating Curve= 0 ,0
Exp/Cntr=0.3,0.1

Type RM Length L Ch R = 1 ,39497   ,812,812,812
BEGIN DESCRIPTION:
Georges Creek 79.0
END DESCRIPTION:
XS GIS Cut Line= 3
      1529868.38      1102335.11      1529979.96      1101915.66
      1530099.57      1101715.94
#Sta/Elev= 24
    4566  940.05  4567.3   939.6  4695.3  906.99  4724.6  903.27    4763  899.96
  4784.6  896.94  4792.5  894.64  4804.3  891.57  4837.7  894.63  4946.1  894.89
  4980.9  894.29  4992.9  891.29  4993.9  889.29  5006.1  889.29  5007.1  891.29
  5021.9  901.85    5059  899.44    5093  908.26  5104.4  911.49  5130.7  922.22
    5146  924.41  5153.1     925  5225.6  940.42  5232.8  940.69
#Mann= 3 ,-1,0
    4566    .125       0  4992.9    .048       0  5007.1     .15       0
Bank Sta=4992.9,5007.1
XS Rating Curve= 0 ,0
Exp/Cntr=0.5,0.3

Type RM Length L Ch R = 1 ,38685   ,155,155,155
BEGIN DESCRIPTION:
Georges Creek 78.0
END DESCRIPTION:
XS GIS Cut Line= 4
       1530702.8      1102712.46      1530639.02      1102374.97
      1530623.08      1102157.06       1530665.6      1101859.43
#Sta/Elev= 30
  4610.9  927.17  4672.8  920.25  4691.5  916.49  4710.5  914.15    4725  910.99
    4742  910.72  4766.6  908.57  4794.7     908  4841.5  901.52  4883.1  899.24
  4965.6  897.25  4980.8     895  4990.4   885.2  5009.7   885.2  5019.3     895
  5077.7     895  5084.3   894.5  5131.6  895.56  5172.8  894.14  5211.9  894.17
  5233.4  893.16    5287  894.85  5299.8  895.98  5315.1   895.8  5343.1  898.91
  5365.3  899.61  5414.4  896.83  5419.3  897.64  5438.9  904.31  5457.1   908.5
#Mann= 3 ,-1,0
  4610.9     .15       0  4980.8    .048       0  5019.3    .135       0
#XS Ineff= 2 , 0
          4920.5  902.76  5079.5          900.92
Permanent Ineff=
       F       F
Bank Sta=4980.8,5019.3
XS Rating Curve= 0 ,0
Exp/Cntr=0.5,0.3

Type RM Length L Ch R = 3 ,38628   ,,,
BEGIN DESCRIPTION:
Grant Valley Rd. - TOR
Structure ID: LDS_GC_11
Approximate Survey Structure
END DESCRIPTION:
Bridge Culvert--1,0,-1,-1, 0
Deck Dist Width WeirC Skew NumUp NumDn MinLoCord MaxHiCord MaxSubmerge Is_Ogee
39.5,35,3,0, 20, 20, , , , 0, 1,1,,
  4647.7  4765.5  4882.4    4960    4960    5040    5040  5137.6  5138.4    5149
  5159.2    5192  5228.4  5334.1  5390.9  5397.1  5401.3  5417.9  5435.8  5437.3
   915.7  907.49  904.46     901     901     901     901  900.79   900.8  900.72
  900.89  900.56  900.62  903.52  906.24  906.18     906  909.15  908.95  909.07
   865.2   865.2   865.2   865.2   899.5   899.5   865.2   865.2   865.2   865.2
   865.2   865.2   865.2   865.2   865.2   865.2   865.2   865.2   865.2   865.2
  4647.7  4765.5  4882.4    4960    4960    5040    5040  5137.6  5138.4    5149
  5159.2    5192  5228.4  5334.1  5390.9  5397.1  5401.3  5417.9  5435.8  5437.3
   915.7  907.49  904.46     901     901     901     901  900.79   900.8  900.72
  900.89  900.56  900.62  903.52  906.24  906.18     906  909.15  908.95  909.07
   865.2   865.2   865.2   865.2   899.5   899.5   865.2   865.2   865.2   865.2
   865.2   865.2   865.2   865.2   865.2   865.2   865.2   865.2   865.2   865.2
Pier Skew, UpSta & Num, DnSta & Num=  ,4980, 2 ,4980, 2 , 0 , 0 , 0 ,0,0
       1       1
  894.37   899.5
       1       1
  889.84   899.5
Pier Skew, UpSta & Num, DnSta & Num=  ,5020, 2 ,5020, 2 , 0 , 0 , 0 ,0,0
       1       1
  896.14   899.5
       1       1
  895.68   899.5
Abutment Skew #Up #Dn= , 2 , 2
    4960    4963
   899.5  897.28
    4960    4963
   899.5  892.74
Abutment Skew #Up #Dn= , 2 , 2
    5037    5040
  895.08   899.5
    5037    5040
  895.04   899.5
BR Coef=-1 ,-1 , 0 ,1.25, 0 ,,,0.8,0,2,0,
WSPro=,,,, 1 ,,,, 0 ,,,, 0 ,,,,-1 ,-1 ,-1 , 0 , 0 , 0 , 0 , 0
BC Design=,, 0 ,, 0 ,,,,,,
BC HTab HWMax=927.17
BC Use User HTab Curves=0
BC User HTab FreeFlow(D)= 0

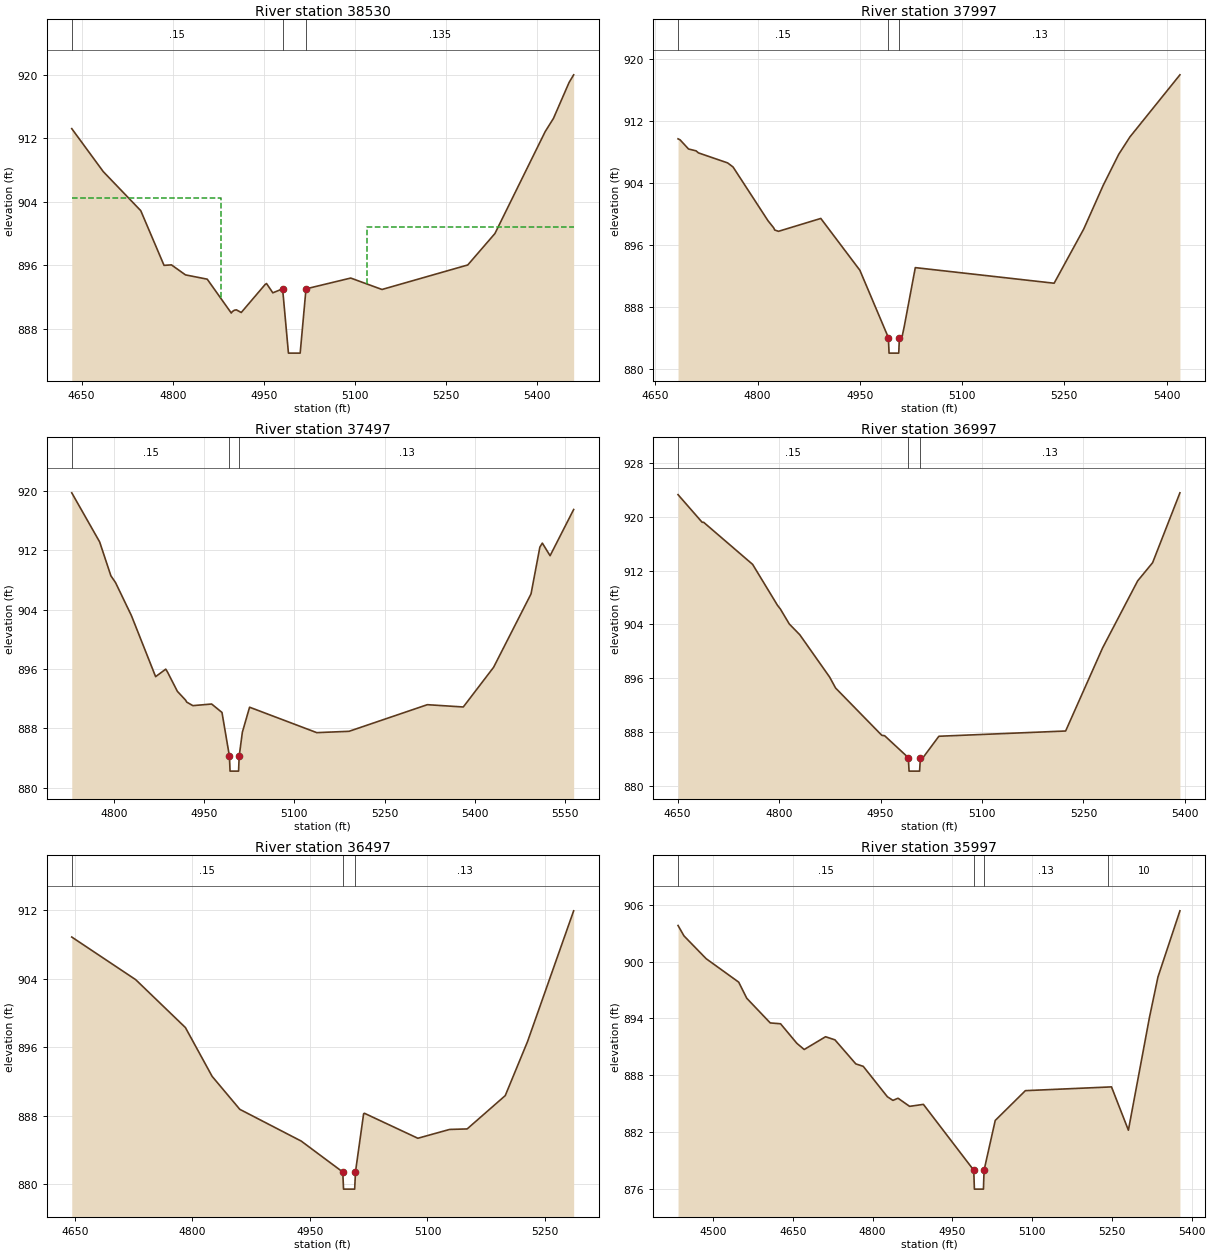
Type RM Length L Ch R = 1 ,38530   ,533,533,533
BEGIN DESCRIPTION:
Georges Creek 77.0
END DESCRIPTION:
XS GIS Cut Line= 3
      1530851.61      1102720.43      1530769.23      1102268.67
      1530833.01      1101907.27
#Sta/Elev= 27
  4633.7  913.24  4685.6  907.82  4747.3   902.9  4785.6  896.01  4797.8  896.07
  4820.9  894.81  4856.7  894.27  4896.3     890  4898.1  890.19  4901.5  890.36
  4904.8   890.4  4912.7  890.07  4951.7  893.57  4954.3  893.72  4964.7  892.55
  4980.8  893.05  4990.4  884.95  5009.7  884.95  5019.3  893.05  5092.9  894.41
  5144.4  892.97  5285.6  896.06  5330.3  900.02    5413  912.86  5426.7  914.54
  5452.4  919.06  5459.9  920.02
#Mann= 3 ,-1,0
  4633.7     .15       0  4980.8    .048       0  5019.3    .135       0
#XS Ineff= 2 , 0
          4879.5  904.54  5120.5          900.83
Permanent Ineff=
       F       F
Bank Sta=4980.8,5019.3
XS Rating Curve= 0 ,0
Exp/Cntr=0.5,0.3

Type RM Length L Ch R = 1 ,37997   ,500,500,500
BEGIN DESCRIPTION:
Georges Creek 76.0
END DESCRIPTION:
XS GIS Cut Line= 3
        1531225.        1102825.      1531289.22      1102515.03
        1531425.        1102025.
#Sta/Elev= 26
  4683.4  909.72  4686.4  909.59  4698.8  908.41  4709.9  908.17  4713.3  907.91
  4756.1  906.62  4764.1  906.09  4815.4  899.16  4823.7  898.25  4825.2  897.97
  4830.7   897.8  4892.8  899.46  4950.1  892.78  4991.9   884.1  4992.9   882.1
  5007.1   882.1  5008.1   884.1  5011.7   884.1    5015  885.45  5031.4  893.12
    5235  891.11  5278.5  898.11    5307  903.73  5329.7  907.72  5346.2  909.97
  5419.5  917.97
#Mann= 3 ,-1,0
  4683.4     .15       0  4991.9    .048       0  5008.1     .13       0
Bank Sta=4991.9,5008.1
XS Rating Curve= 0 ,0
Exp/Cntr=0.3,0.1

Type RM Length L Ch R = 1 ,37497   ,500,500,500
BEGIN DESCRIPTION:
Georges Creek 75.0
END DESCRIPTION:
XS GIS Cut Line= 3
        1531625.        1103025.      1531748.38      1102678.61
        1532181.      1102315.96
#Sta/Elev= 30
  4729.6  919.74    4776  913.12  4794.7  908.55  4802.4  907.64  4828.8  903.19
  4869.1  894.95  4885.9  895.96  4888.5  895.63  4905.3  892.97    4919  891.78
  4920.8  891.52  4931.1  891.04  4962.3  891.26  4979.5  890.12  4991.9  884.21
  4992.9  882.21  5007.1  882.21  5008.1  884.21  5013.4  887.46  5025.4  890.83
  5137.2   887.4  5190.9  887.58  5321.1  891.17  5380.9  890.86  5431.3  896.21
  5493.6  906.11  5508.3  912.42  5512.4  912.96  5525.3  911.26  5564.5  917.49
#Mann= 3 ,-1,0
  4729.6     .15       0  4991.9    .048       0  5008.1     .13       0
Bank Sta=4991.9,5008.1
XS Rating Curve= 0 ,0
Exp/Cntr=0.3,0.1

Type RM Length L Ch R = 1 ,36997   ,500,500,500
BEGIN DESCRIPTION:
Georges Creek 74.0
END DESCRIPTION:
XS GIS Cut Line= 3
       1532066.9      1103265.09      1532173.53      1102932.37
      1532497.38       1102570.1
#Sta/Elev= 23
  4650.6  923.28  4686.2  919.18  4688.5  919.17  4760.9  912.92  4797.6  906.85
  4801.8  906.31  4815.1  904.07  4830.7  902.46  4874.7  896.19  4883.6  894.55
  4951.9  887.53  4956.1  887.47  4991.1  884.21  4992.2  882.21  5007.8  882.21
  5008.9  884.21  5012.8  884.21  5036.3  887.39  5223.7  888.17  5278.3   900.5
  5330.2  910.47  5352.3  913.17  5392.7  923.55
#Mann= 3 ,-1,0
  4650.6     .15       0  4991.1    .048       0  5008.9     .13       0
Bank Sta=4991.1,5008.9
XS Rating Curve= 0 ,0
Exp/Cntr=0.3,0.1

Type RM Length L Ch R = 1 ,36497   ,500,500,500
BEGIN DESCRIPTION:
Georges Creek 73.0
END DESCRIPTION:
XS GIS Cut Line= 3
      1532367.72      1103441.43      1532649.91      1103074.45
      1532678.91      1102777.56
#Sta/Elev= 18
  4646.1  908.85  4727.7  903.87  4791.1  898.28  4825.2  892.58  4860.5  888.73
  4938.9  885.02  4991.9  881.41  4992.9  879.41  5007.1  879.41  5008.1  881.41
  5018.5  888.21  5019.5  888.27  5087.7  885.35  5128.2  886.38  5150.6  886.44
  5199.2  890.33  5227.6  896.63  5286.5  911.91
#Mann= 3 ,-1,0
  4646.1     .15       0  4991.9    .048       0  5008.1     .13       0
Bank Sta=4991.9,5008.1
XS Rating Curve= 0 ,0
Exp/Cntr=0.3,0.1

Type RM Length L Ch R = 1 ,35997   ,499,499,499
BEGIN DESCRIPTION:
Georges Creek 72.0
END DESCRIPTION:
XS GIS Cut Line= 3
      1533093.83      1103845.98      1533142.46       1103148.1
      1533223.49      1102746.44
#Sta/Elev= 30
  4434.2  903.81  4445.4  902.71  4487.1   900.3  4548.3  897.82  4563.4  896.12
  4607.6  893.51    4627  893.42  4657.7  891.35  4671.5   890.7  4711.6  892.05
  4729.3  891.72  4768.5  889.18  4782.5  888.92  4827.8  885.71  4838.3  885.32
  4847.9  885.55  4869.7  884.69  4895.6   884.9  4990.3  877.94  4991.5  875.94
  5008.5  875.94  5009.7  877.94  5030.7   883.2  5087.4  886.35  5242.5  886.73
  5249.3  886.75  5281.1  882.17  5320.7  894.09  5336.7  898.37    5378  905.36
#Mann= 4 ,-1,0
  4434.2     .15       0  4990.3    .048       0  5009.7     .13       0
  5242.5      10       0
Bank Sta=4990.3,5009.7
XS Rating Curve= 0 ,0
Exp/Cntr=0.3,0.1