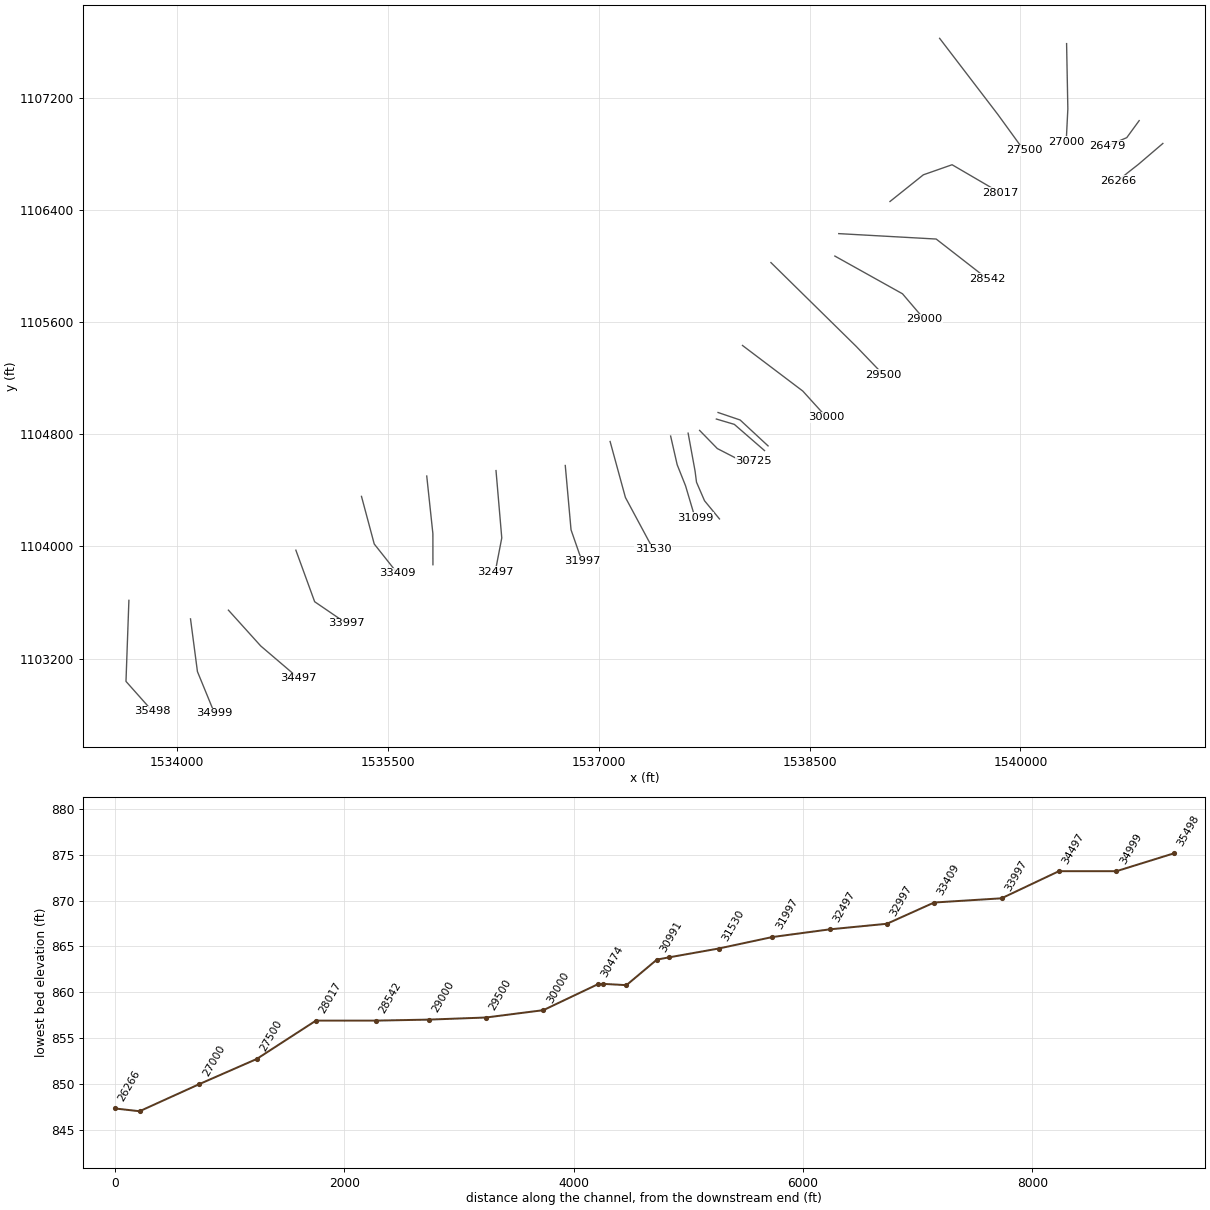
HEC-RAS study GeorgesCreek.prj: Georges Creek Limited Detail Study

--- GeorgesCreek.g06 (geometry) --- (continued)

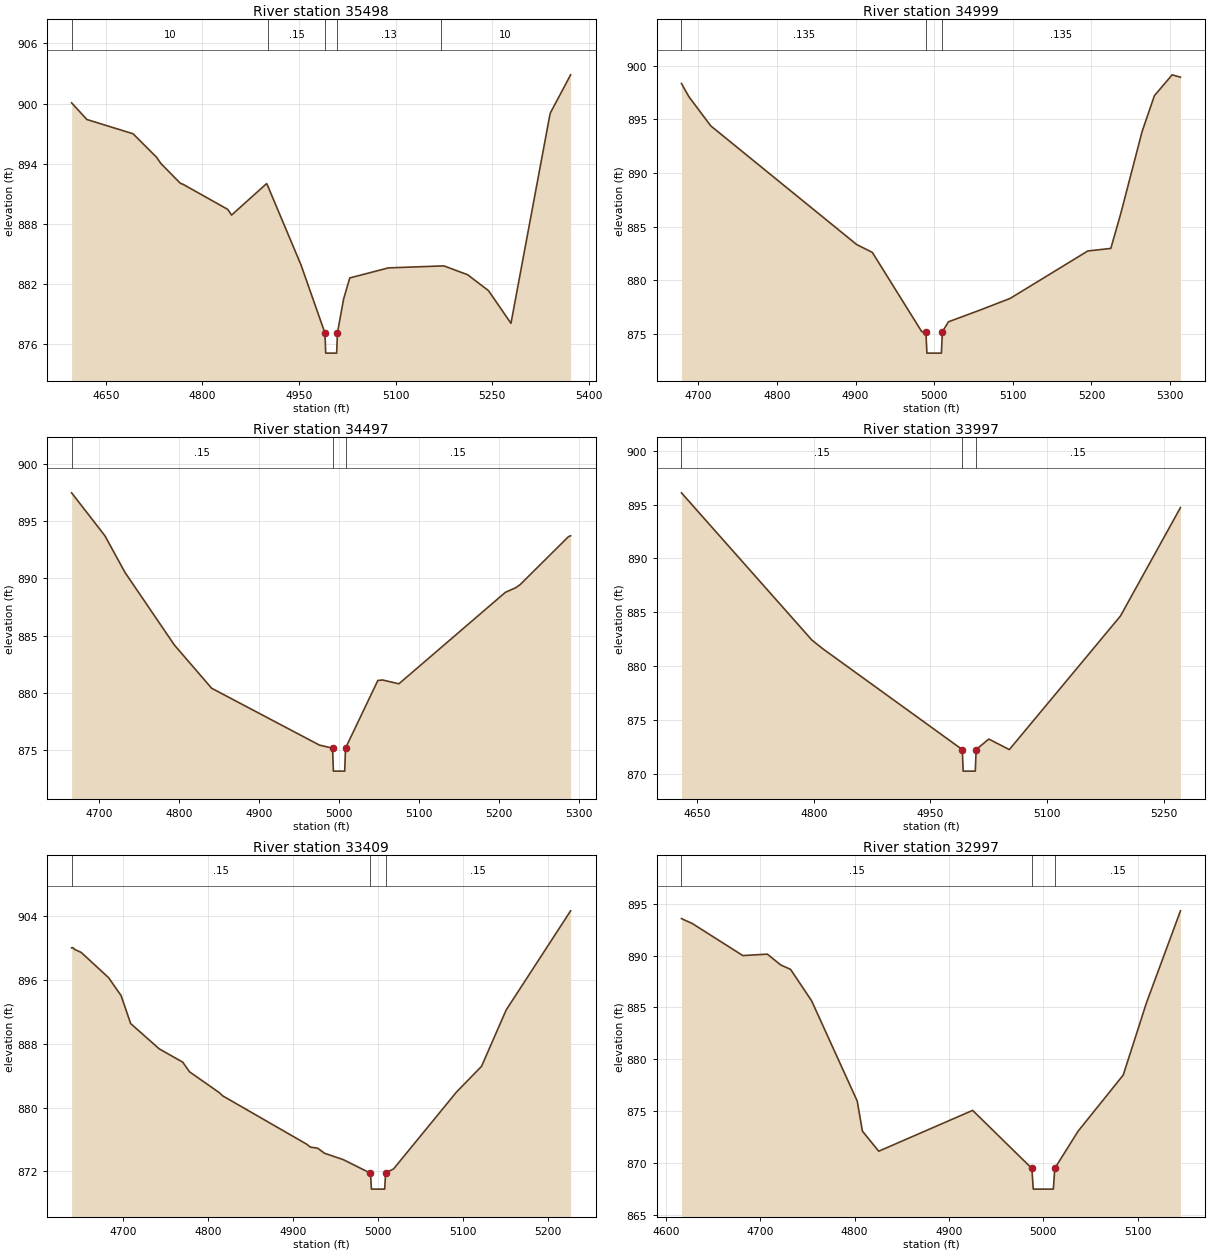
Type RM Length L Ch R = 1 ,35498   ,499,499,499
BEGIN DESCRIPTION:
Georges Creek 71.0
END DESCRIPTION:
XS GIS Cut Line= 3
      1533657.86      1103615.18      1533637.11      1103036.88
        1533825.        1102825.
#Sta/Elev= 29
  4596.6  900.07  4620.3  898.41  4692.1  896.99  4728.6  894.65  4735.3  894.03
  4765.1  892.09  4767.4     892  4769.1  891.98  4839.2  889.46  4845.2  888.89
  4899.7  892.03    4901  891.86  4901.8  891.74  4953.2  883.91  4990.3  877.14
  4991.5  875.14  5008.5  875.14  5009.7  877.14  5019.3  880.53  5028.9  882.63
  5088.9  883.63  5170.2  883.82  5175.1  883.83    5212  882.95  5244.4  881.37
  5279.4  878.11  5339.2  898.65  5340.6  899.06  5372.1  902.86
#Mann= 5 ,-1,0
  4596.6      10       0  4901.8     .15       0  4990.3    .048       0
  5009.7     .13       0  5170.2      10       0
Bank Sta=4990.3,5009.7
XS Rating Curve= 0 ,0
Exp/Cntr=0.3,0.1

Type RM Length L Ch R = 1 ,34999   ,502,502,502
BEGIN DESCRIPTION:
Georges Creek 70.0
END DESCRIPTION:
XS GIS Cut Line= 3
      1534096.12      1103482.92      1534145.39       1103106.9
      1534267.27      1102808.68
#Sta/Elev= 20
  4678.6  898.33    4688  897.11  4715.9  894.38  4901.5  883.32  4921.4  882.59
  4984.2   875.2  4989.5   875.2  4990.8   873.2  5009.2   873.2  5010.5   875.2
  5018.2  876.12  5057.9   877.2  5096.7   878.3  5195.4  882.72  5224.7  882.96
  5237.5  886.24  5264.4  893.83  5280.1  897.19  5302.7  899.14  5313.3  898.92
#Mann= 3 ,-1,0
  4678.6    .135       0  4989.5    .048       0  5010.5    .135       0
Bank Sta=4989.5,5010.5
XS Rating Curve= 0 ,0
Exp/Cntr=0.3,0.1

Type RM Length L Ch R = 1 ,34497   ,500,500,500
BEGIN DESCRIPTION:
Georges Creek 69.0
END DESCRIPTION:
XS GIS Cut Line= 3
      1534365.82      1103545.16      1534595.81      1103289.47
      1534863.72      1103060.22
#Sta/Elev= 18
  4665.1  897.45  4706.8  893.71    4732  890.51  4793.9  884.18  4840.5  880.42
  4975.4  875.47  4991.9   875.2  4992.9   873.2  5007.1   873.2  5008.1   875.2
  5048.6   881.1  5054.6  881.14    5075  880.81  5208.3  888.78  5221.5  889.19
  5226.9  889.46  5287.3  893.63    5290  893.71
#Mann= 3 ,-1,0
  4665.1     .15       0  4991.9     .05       0  5008.1     .15       0
Bank Sta=4991.9,5008.1
XS Rating Curve= 0 ,0
Exp/Cntr=0.3,0.1

Type RM Length L Ch R = 1 ,33997   ,588,588,588
BEGIN DESCRIPTION:
Georges Creek 68.0
END DESCRIPTION:
XS GIS Cut Line= 3
      1534845.57      1103973.05      1534979.23      1103605.36
      1535203.44       1103451.8
#Sta/Elev= 11
  4629.7  896.09  4797.6  882.41  4811.5  881.61  4991.1  872.24  4992.2  870.24
  5007.8  870.24  5008.9  872.24  5025.2  873.22  5051.6  872.24  5194.6  884.65
  5271.8  894.72
#Mann= 3 ,-1,0
  4629.7     .15       0  4991.1     .05       0  5008.9     .15       0
Bank Sta=4991.1,5008.9
XS Rating Curve= 0 ,0
Exp/Cntr=0.3,0.1

Type RM Length L Ch R = 1 ,33409   ,412,412,412
BEGIN DESCRIPTION:
Georges Creek 67.0
END DESCRIPTION:
XS GIS Cut Line= 3
      1535312.36      1104356.85      1535403.12      1104017.13
      1535569.09      1103807.08
#Sta/Elev= 28
  4639.1  900.06  4640.6  900.08    4641  900.03  4641.2  900.02  4642.4  899.87
  4650.4  899.48  4682.7  896.31  4697.4  894.06  4708.6  890.56  4742.4  887.37
  4769.9  885.72    4778   884.5  4813.5  881.85  4816.8   881.5  4916.1  875.41
  4920.3  875.05  4928.8  874.92    4937  874.28  4959.1  873.48  4991.1  871.78
  4992.2  869.78  5007.8  869.78  5008.9  871.78  5018.4  872.33  5092.3  881.95
  5121.9  885.19  5150.9  892.26  5226.8   904.7
#Mann= 3 ,-1,0
  4639.1     .15       0  4991.1     .05       0  5008.9     .15       0
Bank Sta=4991.1,5008.9
XS Rating Curve= 0 ,0
Exp/Cntr=0.3,0.1

Type RM Length L Ch R = 1 ,32997   ,500,500,500
BEGIN DESCRIPTION:
Georges Creek 66.0
END DESCRIPTION:
XS GIS Cut Line= 3
      1535776.55      1104502.07      1535820.27      1104090.84
      1535820.63      1103869.32
#Sta/Elev= 19
  4616.3  893.57  4627.9  893.09  4681.4     890  4707.4  890.14  4721.5   889.1
    4732  888.67  4754.3  885.64  4802.7  875.96  4808.2  873.06  4825.5  871.12
  4925.1  875.06  4987.9  869.46  4989.4  867.46  5010.7  867.46  5012.2  869.46
    5037  873.06  5084.8  878.47  5109.5  885.46  5145.5  894.32
#Mann= 3 ,-1,0
  4616.3     .15       0  4987.9     .05       0  5012.2     .15       0
Bank Sta=4987.9,5012.2
XS Rating Curve= 0 ,0
Exp/Cntr=0.3,0.1

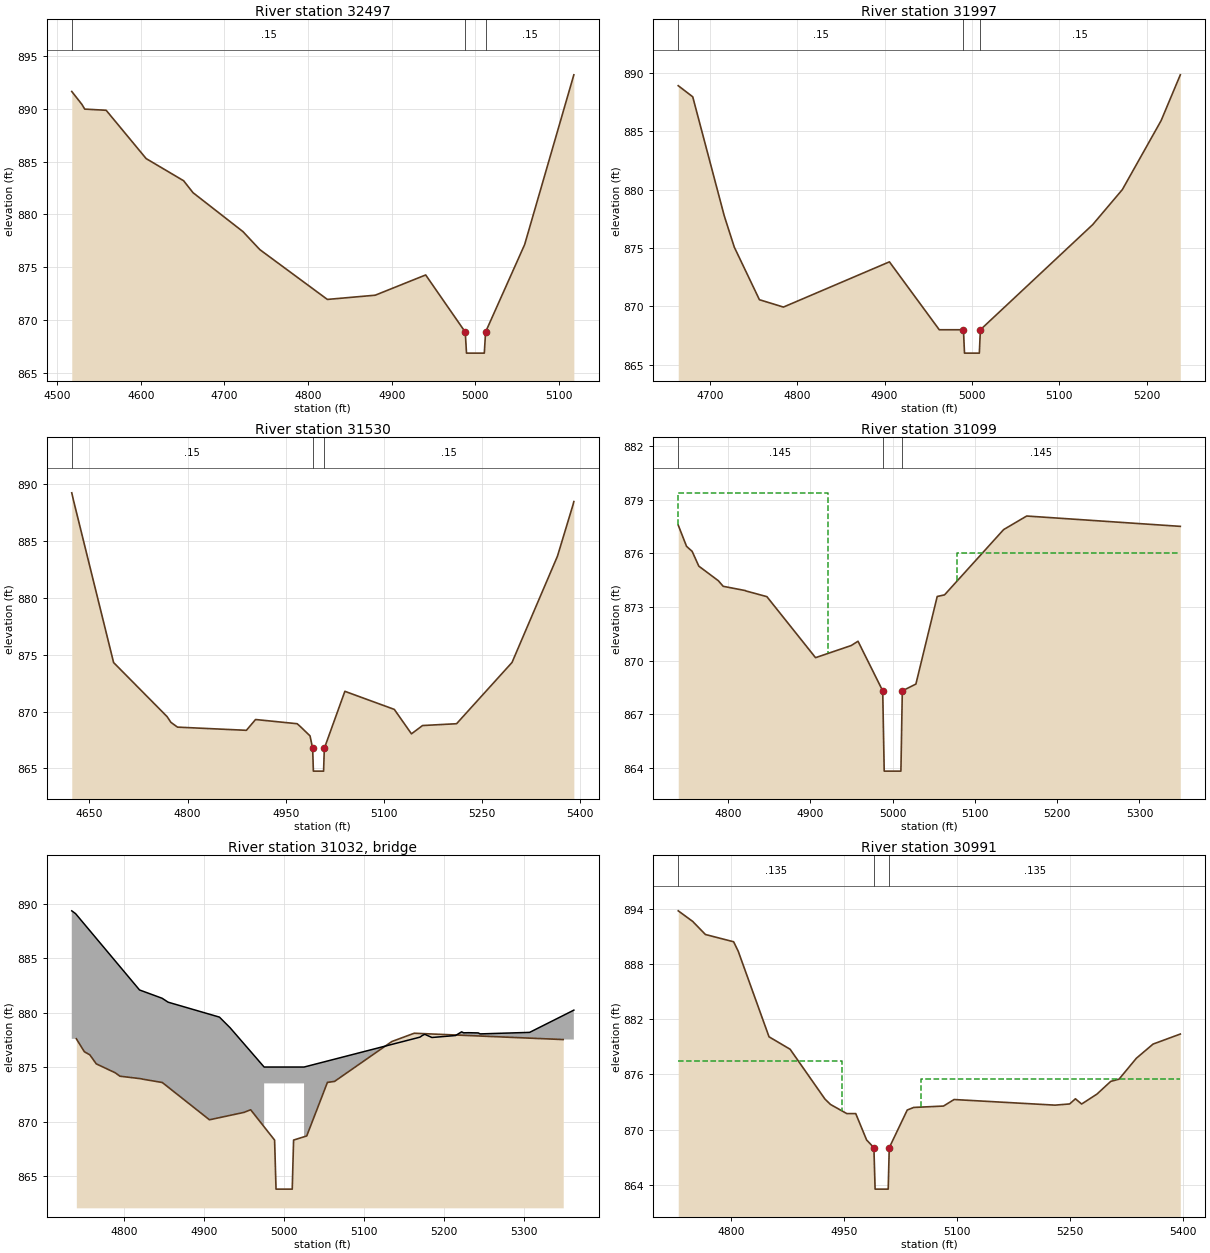
Type RM Length L Ch R = 1 ,32497   ,500,500,500
BEGIN DESCRIPTION:
Georges Creek 65.0
END DESCRIPTION:
XS GIS Cut Line= 3
      1536269.27      1104540.97      1536310.29      1104060.34
      1536264.08      1103820.05
#Sta/Elev= 18
  4517.6  891.65  4529.7  890.43  4533.1  889.98  4558.7  889.87  4606.5  885.29
  4651.3  883.19  4662.5  882.06  4722.2  878.37  4742.4  876.66  4823.1  871.94
  4880.3  872.34  4940.6  874.26  4987.9  868.85  4989.4  866.85  5010.7  866.85
  5012.2  868.85  5058.9  877.14  5117.7  893.23
#Mann= 3 ,-1,0
  4517.6     .15       0  4987.9     .05       0  5012.2     .15       0
Bank Sta=4987.9,5012.2
XS Rating Curve= 0 ,0
Exp/Cntr=0.3,0.1

Type RM Length L Ch R = 1 ,31997   ,467,467,467
BEGIN DESCRIPTION:
Georges Creek 64.0
END DESCRIPTION:
XS GIS Cut Line= 3
      1536761.99      1104577.28      1536803.05      1104118.22
      1536881.28      1103892.66
#Sta/Elev= 16
  4663.6  888.89  4680.2  887.94  4716.3  877.76  4727.8  875.08  4756.6  870.58
  4784.1  869.95  4905.5  873.82  4962.6  868.01  4990.3  868.01  4991.5  866.01
  5008.5  866.01  5009.7  868.01  5138.3     877  5172.3     880  5216.7   885.9
  5238.7  889.82
#Mann= 3 ,-1,0
  4663.6     .15       0  4990.3     .05       0  5009.7     .15       0
Bank Sta=4990.3,5009.7
XS Rating Curve= 0 ,0
Exp/Cntr=0.3,0.1

Type RM Length L Ch R = 1 ,31530   ,431,431,431
BEGIN DESCRIPTION:
Georges Creek 63.0
END DESCRIPTION:
XS GIS Cut Line= 3
      1537080.96      1104748.43      1537189.87      1104349.07
      1537386.96      1103980.83
#Sta/Elev= 24
  4623.2  889.24  4625.6  888.63  4687.1  874.31  4768.7  869.56  4774.6  869.05
  4784.7  868.63  4889.9  868.35  4903.9   869.3  4967.4  868.93  4972.3  868.68
  4987.1  867.86  4991.1  866.76  4992.2  864.76  5007.8  864.76  5008.9  866.76
  5040.3  871.78  5115.8  870.19    5142  868.04  5158.9  868.77  5210.9  868.93
  5295.6  874.32    5365  883.67  5388.8   888.2    5390  888.47
#Mann= 3 ,-1,0
  4623.2     .15       0  4991.1     .05       0  5008.9     .15       0
Bank Sta=4991.1,5008.9
XS Rating Curve= 0 ,0
Exp/Cntr=0.5,0.3

Type RM Length L Ch R = 1 ,31099   ,108,108,108
BEGIN DESCRIPTION:
Georges Creek 62.5
END DESCRIPTION:
XS GIS Cut Line= 4
      1537511.44      1104787.33      1537558.12      1104582.46
      1537617.76      1104432.05      1537685.18      1104203.85
#Sta/Elev= 22
  4739.7  877.59  4749.8   876.4  4756.6  876.12  4764.7  875.29  4788.5  874.47
  4794.3  874.16  4821.3  873.92  4821.9   873.9  4847.4  873.58  4906.5  870.16
  4949.8  870.84  4958.1  871.08  4988.1   868.3  4989.9   863.8  5010.2   863.8
  5011.9   868.3  5028.4  868.68  5054.3  873.59  5063.2  873.68    5135  877.34
    5163   878.1  5349.6  877.52
#Mann= 3 ,-1,0
  4739.7    .145       0  4988.1    .043       0  5011.9    .145       0
#XS Ineff= 2 , 0
          4921.5   879.4  5078.5          876.01
Permanent Ineff=
       F       F
Bank Sta=4988.1,5011.9
XS Rating Curve= 0 ,0
Exp/Cntr=0.5,0.3

Type RM Length L Ch R = 3 ,31032   ,,,
BEGIN DESCRIPTION:
Lenhardt Rd. (Georges Cr.) - TOR
Structure ID: LDS_GC_10
Approximate Survey Structure
END DESCRIPTION:
Bridge Culvert--1,0,-1,-1, 0
Deck Dist Width WeirC Skew NumUp NumDn MinLoCord MaxHiCord MaxSubmerge Is_Ogee
53.5,27,3,0, 23, 23, , , , 0, 1,1,,
    4734  4738.8  4818.9  4847.2  4854.7    4919  4932.4    4975    4975    5025
    5025  5170.1  5173.3  5176.3  5185.2  5214.7  5222.4  5224.9  5230.9  5243.2
  5245.6  5307.6    5363
  889.33  889.07  882.07  881.31  880.95  879.58   878.6     875     875     875
     875  877.74   877.9     878  877.71  877.89  878.23  878.14  878.15  878.13
  878.04  878.18  880.22
   843.8   843.8   843.8   843.8   843.8   843.8   843.8   843.8   873.5   873.5
   843.8   843.8   843.8   843.8   843.8   843.8   843.8   843.8   843.8   843.8
   843.8   843.8   843.8
    4734  4738.8  4818.9  4847.2  4854.7    4919  4932.4    4975    4975    5025
    5025  5170.1  5173.3  5176.3  5185.2  5214.7  5222.4  5224.9  5230.9  5243.2
  5245.6  5307.6    5363
  889.33  889.07  882.07  881.31  880.95  879.58   878.6     875     875     875
     875  877.74   877.9     878  877.71  877.89  878.23  878.14  878.15  878.13
  878.04  878.18  880.22
   843.8   843.8   843.8   843.8   843.8   843.8   843.8   843.8   873.5   873.5
   843.8   843.8   843.8   843.8   843.8   843.8   843.8   843.8   843.8   843.8
   843.8   843.8   843.8
Abutment Skew #Up #Dn= , 2 , 2
    4975    4976
   873.5  868.34
    4975    4976
   873.5   869.7
Abutment Skew #Up #Dn= , 2 , 2
    5024    5025
  869.26   873.5
    5024    5025
  869.02   873.5
BR Coef=-1 ,-1 , 0 ,1.25, 0 ,,,0.8,0,2,0,
WSPro=,,,, 1 ,,,, 0 ,,,, 0 ,,,,-1 ,-1 ,-1 , 0 , 0 , 0 , 0 , 0
BC Design=,, 0 ,, 0 ,,,,,,
BC HTab HWMax=878.1
BC Use User HTab Curves=0
BC User HTab FreeFlow(D)= 0

Type RM Length L Ch R = 1 ,30991   ,266,266,266
BEGIN DESCRIPTION:
Georges Creek 62.0
END DESCRIPTION:
XS GIS Cut Line= 5
      1537635.91      1104808.08      1537685.18      1104538.38
      1537695.56      1104457.99      1537752.61      1104325.73
      1537858.93      1104196.07
#Sta/Elev= 30
  4729.9  893.77  4749.1  892.62    4766   891.2  4803.5  890.41  4809.6  889.38
  4850.5  880.09  4878.5  878.74  4924.8  873.33  4932.2  872.74  4953.9  871.75
  4965.7  871.75  4980.1  868.89  4989.8  868.05  4991.4  863.55  5008.8  863.55
  5010.2  868.05  5034.1  872.14  5042.7  872.42  5082.2  872.57  5096.3  873.28
  5230.4  872.67  5249.8   872.8  5257.5  873.36  5265.7  872.79  5286.1  873.87
  5304.4  875.25  5315.4  875.49  5338.4  877.76  5360.6   879.3  5396.8  880.39
#Mann= 3 ,-1,0
  4729.9    .135       0  4989.8    .043       0  5010.2    .135       0
#XS Ineff= 2 , 0
          4947.5  877.43  5052.5          875.52
Permanent Ineff=
       F       F
Bank Sta=4989.8,5010.2
XS Rating Curve= 0 ,0
Exp/Cntr=0.5,0.3

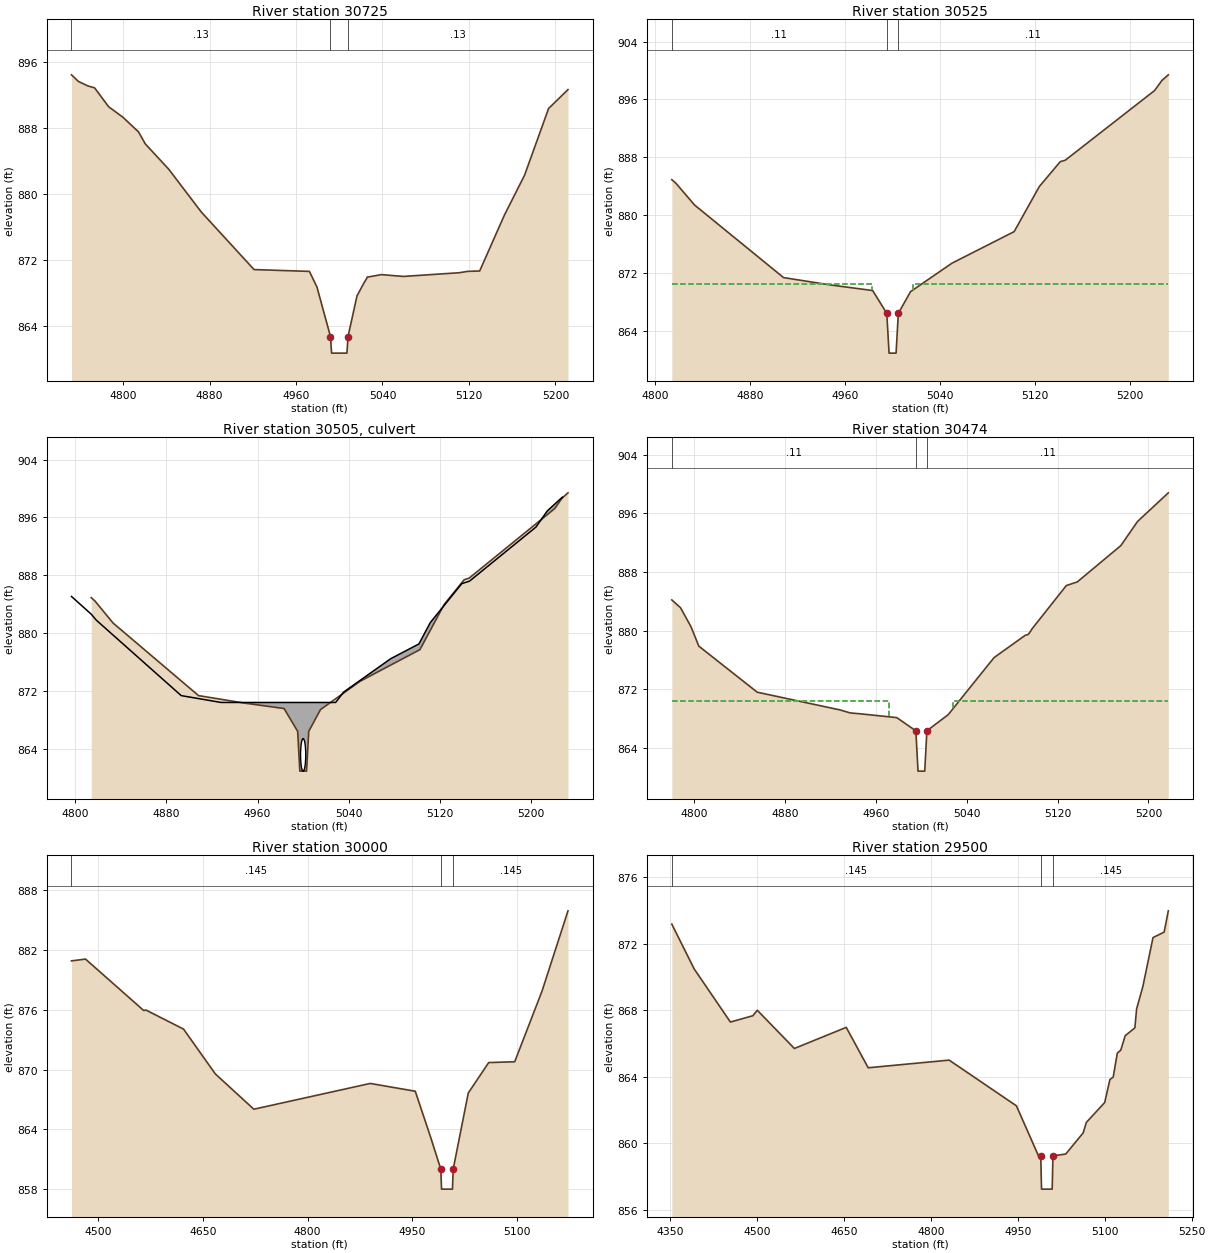
Type RM Length L Ch R = 1 ,30725   ,200,200,200
BEGIN DESCRIPTION:
Georges Creek 61.5
END DESCRIPTION:
XS GIS Cut Line= 4
      1537717.64      1104827.58      1537843.69      1104698.07
      1537997.38      1104618.64      1538102.71      1104611.73
#Sta/Elev= 30
  4752.3  894.47  4758.7  893.67  4767.4  893.13  4773.7  892.89  4786.7   890.6
  4799.8  889.34  4814.3  887.56  4820.6   886.1  4842.3  883.03  4872.4  877.85
  4921.2  870.88  4972.4  870.66  4979.4  868.76  4991.9  862.76  4992.9  860.76
  5007.1  860.76  5008.1  862.76  5016.4  867.68  5022.8  869.25  5025.3  869.78
  5025.8  869.96    5039  870.27  5059.3  870.05  5111.1   870.5  5118.5  870.66
  5129.9  870.71  5152.9  877.51  5171.4   882.3  5193.7   890.4  5211.6  892.68
#Mann= 3 ,-1,0
  4752.3     .13       0  4991.9    .042       0  5008.1     .13       0
Bank Sta=4991.9,5008.1
XS Rating Curve= 0 ,0
Exp/Cntr=0.5,0.3

Type RM Length L Ch R = 1 ,30525   ,51,51,51
BEGIN DESCRIPTION:
Georges Creek 61.0
END DESCRIPTION:
XS GIS Cut Line= 3
      1537836.79      1104908.74      1537964.57      1104870.75
      1538179.25      1104683.78
#Sta/Elev= 19
  4814.2   884.9  4817.5  884.44  4833.3   881.4  4908.3  871.35  4947.5  870.34
  4983.3  869.56  4995.2   866.4  4997.1   860.9    5003   860.9  5004.9   866.4
  5015.2  869.41    5050  873.34  5102.4  877.71  5123.6  883.95  5141.2  887.39
  5145.5   887.6  5220.6  897.23  5226.8  898.63  5232.2  899.41
#Mann= 3 ,-1,0
  4814.2     .11       0  4995.2    .041       0  5004.9     .11       0
#XS Ineff= 2 , 0
          4982.8   870.4  5017.3           870.4
Permanent Ineff=
       F       F
Bank Sta=4995.2,5004.9
XS Rating Curve= 0 ,0
Exp/Cntr=0.5,0.3

Type RM Length L Ch R = 2 ,30505   ,,,
BEGIN DESCRIPTION:
Unnamed Trail (Georges Cr.) - TOR
Structure ID: Unnamed Trail (Georges Cr.)
Approximate Survey Structure
END DESCRIPTION:
Bridge Culvert--1,0,-1,-1, 0
Deck Dist Width WeirC Skew NumUp NumDn MinLoCord MaxHiCord MaxSubmerge Is_Ogee
15,10,3,0, 15, 15, , , , 0, 1,1,,
  4796.9  4814.4  4818.5  4893.1  4928.1  5028.5  5035.4  5076.7  5101.5  5111.5
  5139.1  5145.8  5204.1  5214.1  5227.3
  885.07  882.59  881.81  871.35   870.4   870.4  871.83  876.45   878.5  881.46
  886.85  887.18  894.67  896.92  898.82
   840.9   840.9   840.9   840.9   840.9   840.9   840.9   840.9   840.9   840.9
   840.9   840.9   840.9   840.9   840.9
  4796.9  4814.4  4818.5  4893.1  4928.1  5028.5  5035.4  5076.7  5101.5  5111.5
  5139.1  5145.8  5204.1  5214.1  5227.3
  885.07  882.59  881.81  871.35   870.4   870.4  871.83  876.45   878.5  881.46
  886.85  887.18  894.67  896.92  898.82
  840.85  840.85  840.85  840.85  840.85  840.85  840.85  840.85  840.85  840.85
  840.85  840.85  840.85  840.85  840.85
Culvert=1,4.5,4.5,10,0.015,0.4,1,1,3,860.9,5000,860.85,5000,Culvert #1  , 0 ,15
    5000    5000
BC Culvert Barrel=1,,0
Culvert Bottom n=0.015
BC Design=,, 0 ,, 0 ,,,,,,
BC HTab HWMax=899.41
BC Use User HTab Curves=0
BC User HTab FreeFlow(D)= 0

Type RM Length L Ch R = 1 ,30474   ,474,474,474
BEGIN DESCRIPTION:
Georges Creek 60.5
END DESCRIPTION:
XS GIS Cut Line= 3
      1537848.87      1104955.36      1538006.01      1104901.83
       1538204.6      1104717.06
#Sta/Elev= 25
  4780.3  884.21    4788  883.14  4797.2  880.55  4804.1   877.9  4855.5  871.62
  4926.9  869.25  4927.3  869.25  4937.4  868.79  4946.3  868.67  4978.4  868.15
  4995.2  866.35  4997.1  860.85    5003  860.85  5004.9  866.35  5023.7  868.56
    5064  876.33  5091.4  879.37  5094.1   879.5  5096.3  879.95  5097.5  880.26
  5127.7  886.17  5137.3  886.66  5175.7  891.62  5190.4  894.91  5217.5  898.82
#Mann= 3 ,-1,0
  4780.3     .11       0  4995.2    .042       0  5004.9     .11       0
#XS Ineff= 2 , 0
          4971.8   870.4  5028.3           870.4
Permanent Ineff=
       F       F
Bank Sta=4995.2,5004.9
XS Rating Curve= 0 ,0
Exp/Cntr=0.5,0.3

Type RM Length L Ch R = 1 ,30000   ,500,500,500
BEGIN DESCRIPTION:
Georges Creek 60.0
END DESCRIPTION:
XS GIS Cut Line= 3
      1538022.63      1105433.68      1538451.72      1105108.31
      1538621.79      1104920.12
#Sta/Elev= 19
  4461.5  880.88  4481.6  881.06  4565.1  875.91  4568.2  875.96  4622.2  874.05
  4667.7  869.57    4723  866.03  4889.9  868.61  4954.5  867.83  4976.7  863.19
  4991.1  860.03  4992.2  858.03  5007.8  858.03  5008.9  860.03  5030.5  867.65
  5059.8   870.7  5097.1  870.78  5136.2  877.84  5173.5  885.89
#Mann= 3 ,-1,0
  4461.5    .145       0  4991.1    .043       0  5008.9    .145       0
Bank Sta=4991.1,5008.9
XS Rating Curve= 0 ,0
Exp/Cntr=0.3,0.1

Type RM Length L Ch R = 1 ,29500   ,500,500,500
BEGIN DESCRIPTION:
Georges Creek 59.0
END DESCRIPTION:
XS GIS Cut Line= 3
        1538225.        1106025.      1538831.23      1105427.39
        1539025.        1105225.
#Sta/Elev= 30
  4352.8  873.17  4391.3  870.48  4453.9  867.28  4492.7  867.66  4500.3  867.99
  4564.3  865.69  4653.8  866.96  4691.7  864.53  4831.4  864.99  4947.5  862.24
  4985.6  859.23  4989.5  859.23  4990.8  857.23  5009.2  857.23  5010.5  859.23
  5032.6  859.34  5062.6  860.61  5068.1  861.24  5099.8  862.44  5108.8  863.82
  5114.5  863.97  5121.6  865.41  5127.6  865.59  5135.2  866.46  5151.9  866.93
  5154.9  868.07  5165.7  869.42  5183.2  872.36  5202.4  872.69  5209.6  873.97
#Mann= 3 ,-1,0
  4352.8    .145       0  4989.5    .043       0  5010.5    .145       0
Bank Sta=4989.5,5010.5
XS Rating Curve= 0 ,0
Exp/Cntr=0.3,0.1

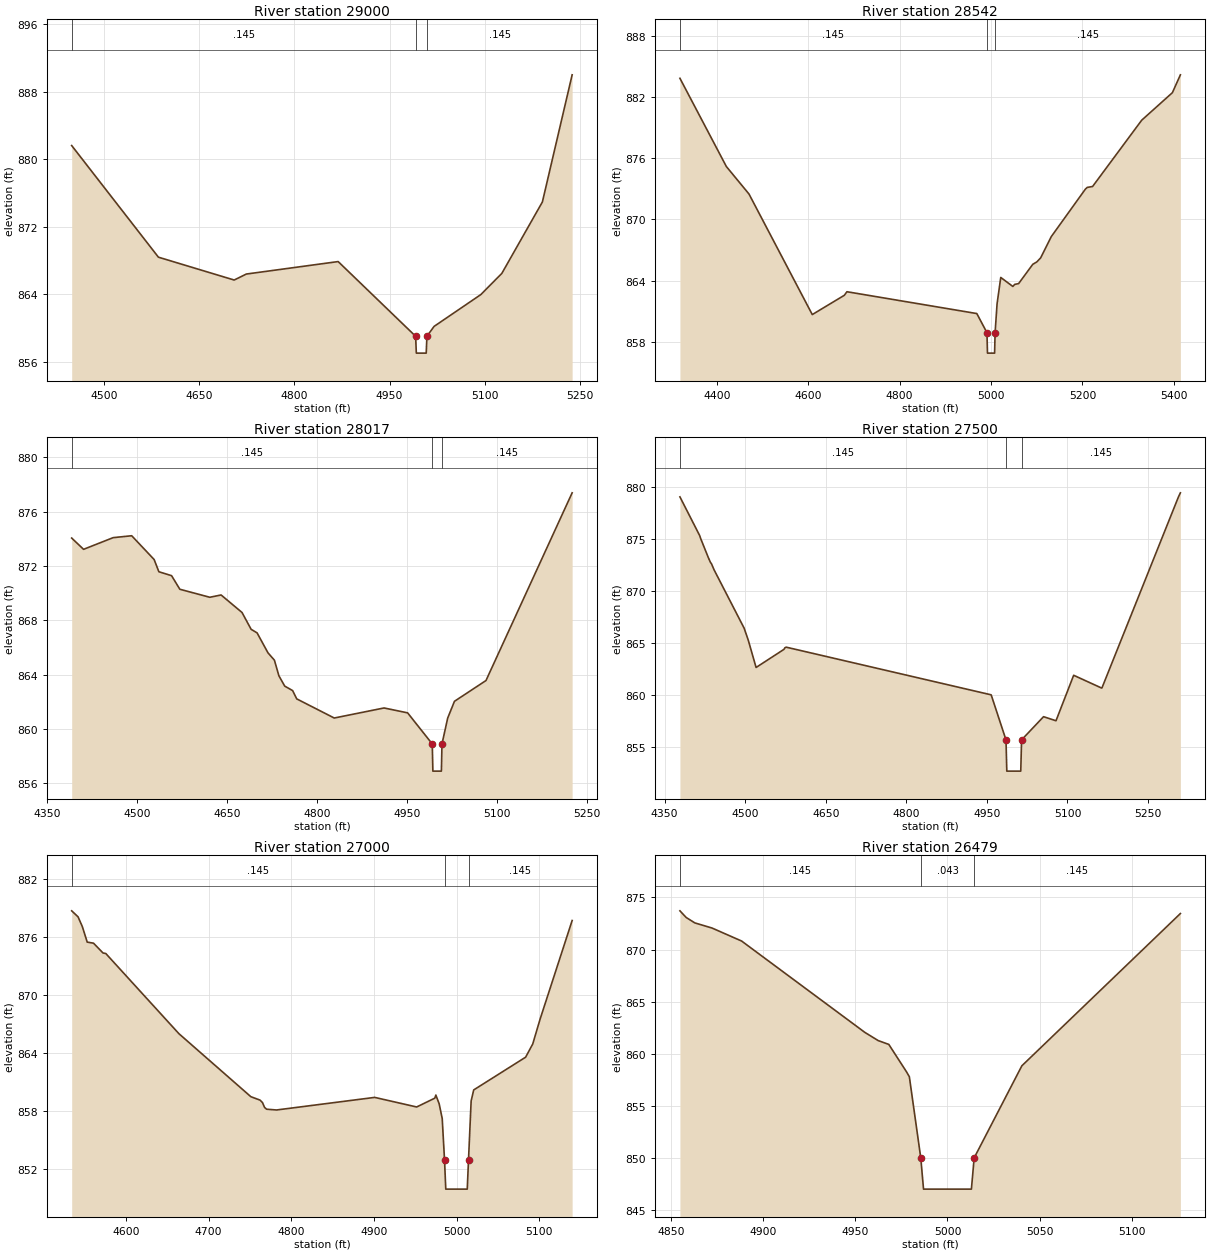
Type RM Length L Ch R = 1 ,29000   ,458,458,458
BEGIN DESCRIPTION:
Georges Creek 58.0
END DESCRIPTION:
XS GIS Cut Line= 3
      1538679.77       1106071.5      1539160.68       1105802.5
      1539314.82      1105621.44
#Sta/Elev= 14
    4449  881.62  4585.7  868.38  4705.1  865.67  4724.3  866.38    4869  867.86
  4991.1     859  4992.2     857  5007.8     857  5008.9     859  5020.2  860.17
  5093.8  863.94    5127  866.46  5190.9  874.93  5237.8  890.01
#Mann= 3 ,-1,0
    4449    .145       0  4991.1    .043       0  5008.9    .145       0
Bank Sta=4991.1,5008.9
XS Rating Curve= 0 ,0
Exp/Cntr=0.3,0.1

Type RM Length L Ch R = 1 ,28542   ,525,525,525
BEGIN DESCRIPTION:
Georges Creek 57.0
END DESCRIPTION:
XS GIS Cut Line= 3
      1538707.38      1106231.64      1539400.42      1106192.99
      1539764.88      1105908.59
#Sta/Elev= 26
    4319  883.84  4420.6  875.19  4470.2  872.49  4608.7  860.67  4678.8  862.56
  4684.6  862.91  4968.9  860.77  4991.1  858.89  4992.2  856.89  5007.8  856.89
  5008.9  858.89  5013.2  861.72  5021.3  864.31  5047.7  863.43  5051.9  863.63
  5060.4  863.71  5091.4   865.6  5100.4  865.84  5108.6  866.23  5131.8  868.31
  5206.5  872.97  5210.6  873.14  5222.3  873.23  5329.8  879.73    5397  882.43
  5414.5  884.18
#Mann= 3 ,-1,0
    4319    .145       0  4991.1    .043       0  5008.9    .145       0
Bank Sta=4991.1,5008.9
XS Rating Curve= 0 ,0
Exp/Cntr=0.3,0.1

Type RM Length L Ch R = 1 ,28017   ,517,517,517
BEGIN DESCRIPTION:
Georges Creek 56.0
END DESCRIPTION:
XS GIS Cut Line= 4
      1539071.85      1106460.82       1539309.3      1106651.33
      1539513.62      1106723.12      1539853.24      1106524.32
#Sta/Elev= 30
  4390.5  874.05  4410.3  873.22  4459.7  874.08  4490.6  874.22    4528  872.47
  4535.9  871.57  4557.1  871.28  4570.9  870.28  4620.9  869.69  4639.7  869.86
  4674.6  868.57  4689.8  867.33  4699.7  867.07  4717.9   865.6  4728.6  865.06
  4736.1  863.91  4745.8  863.15    4759  862.82  4765.8  862.21  4828.4   860.8
  4911.5  861.54  4950.8  861.18  4991.9  858.89  4992.9  856.89  5007.1  856.89
  5008.1  858.89  5017.6  860.79  5028.9  862.03  5081.5  863.56  5225.2  877.38
#Mann= 3 ,-1,0
  4390.5    .145       0  4991.9    .043       0  5008.1    .145       0
Bank Sta=4991.9,5008.1
XS Rating Curve= 0 ,0
Exp/Cntr=0.3,0.1

Type RM Length L Ch R = 1 ,27500   ,500,500,500
BEGIN DESCRIPTION:
Georges Creek 55.0
END DESCRIPTION:
XS GIS Cut Line= 3
        1539425.        1107625.      1539839.49      1107081.36
        1540025.        1106825.
#Sta/Elev= 27
  4378.4  879.05  4415.1  875.34    4417  875.05  4432.2   873.1  4432.3   873.1
  4434.9  872.79  4437.3  872.61  4441.9  872.05    4498  866.43  4505.7  865.27
  4520.2  862.66  4571.8  864.39  4572.8  864.45  4573.7  864.55  4576.3  864.61
  4957.9  860.03  4985.5   855.7    4987   852.7    5013   852.7  5014.5   855.7
  5055.4  857.93  5078.6  857.54  5111.5  861.91  5163.6  860.68  5164.2   860.7
  5306.6  879.05  5310.2  879.44
#Mann= 3 ,-1,0
  4378.4    .145       0  4985.5    .043       0  5014.5    .145       0
Bank Sta=4985.5,5014.5
XS Rating Curve= 0 ,0
Exp/Cntr=0.3,0.1

Type RM Length L Ch R = 1 ,27000   ,521,521,521
BEGIN DESCRIPTION:
Georges Creek 54.0
END DESCRIPTION:
XS GIS Cut Line= 3
      1540328.15      1107587.35      1540337.08      1107121.87
      1540325.39      1106886.03
#Sta/Elev= 30
  4534.4  878.69  4542.1  878.07  4547.3  877.06  4553.2  875.46  4560.8  875.35
  4572.3  874.34  4575.7  874.28  4664.1  866.01  4751.2   859.5  4762.3  859.15
  4765.2   858.9  4767.8  858.39  4770.3  858.21  4782.2  858.13    4901  859.43
  4951.8  858.44  4973.7  859.35    4975  859.67    4979  858.77  4982.7  857.25
  4985.5  852.96    4987  849.96    5013  849.96  5014.5  852.96  5017.7  859.07
  5020.8   860.2  5083.6  863.58  5092.2  864.94  5101.2  867.53  5139.9  877.69
#Mann= 3 ,-1,0
  4534.4    .145       0  4985.5    .043       0  5014.5    .145       0
Bank Sta=4985.5,5014.5
XS Rating Curve= 0 ,0
Exp/Cntr=0.3,0.1

Type RM Length L Ch R = 1 ,26479   ,213,213,213
BEGIN DESCRIPTION:
Georges Creek 53.0
END DESCRIPTION:
XS GIS Cut Line= 3
      1540844.48      1107037.89      1540756.12       1106916.4
      1540620.83      1106858.42
#Sta/Elev= 17
  4854.7  873.72  4858.1  873.08  4862.8  872.56  4872.1  872.07  4888.2  870.82
  4955.2  862.04  4962.4  861.26  4968.2  860.89  4968.3  860.85  4977.8  858.25
  4979.3  857.79  4985.5     850    4987     847    5013     847  5014.5     850
  5040.4  858.84  5126.5  873.46
#Mann= 3 ,-1,0
  4854.7    .145       0  4985.5    .043       0  5014.5    .145       0
Bank Sta=4985.5,5014.5
XS Rating Curve= 0 ,0
Exp/Cntr=0.5,0.3

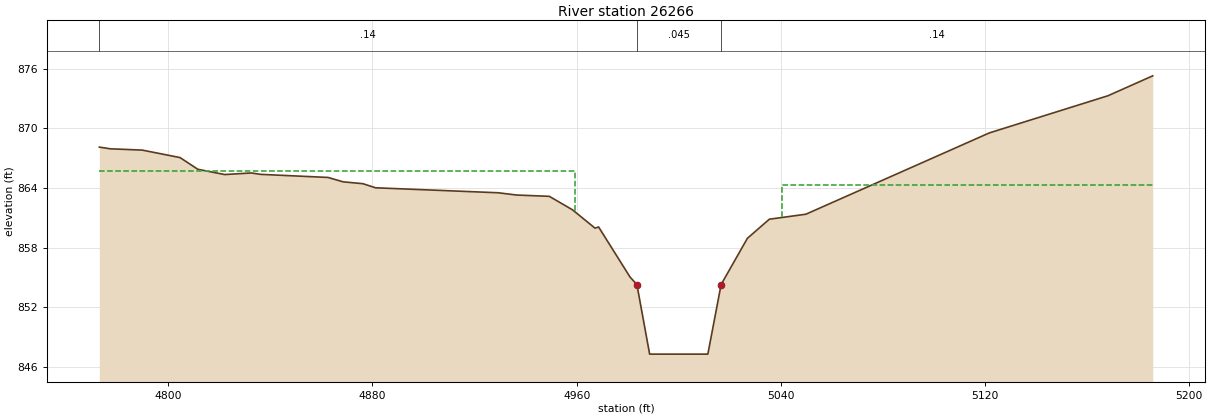
Type RM Length L Ch R = 1 ,26266   ,75,75,75
BEGIN DESCRIPTION:
Georges Creek 52.5
END DESCRIPTION:
XS GIS Cut Line= 4
       1541012.9      1106874.98      1540838.95      1106725.88
      1540761.64      1106665.14      1540696.16      1106610.43
#Sta/Elev= 29
    4773  868.12  4777.3  867.95  4789.8  867.82  4804.6  867.07  4811.6  865.89
  4822.1  865.36  4832.5  865.52  4836.2  865.38  4862.6  865.07  4868.5  864.63
  4876.3  864.44  4881.2  864.03  4929.2  863.53  4936.5   863.3  4949.3  863.17
  4958.4  861.81  4967.2  859.97  4968.6  860.09  4980.9  855.06  4983.6   854.3
  4988.6   847.3  5011.4   847.3  5016.6   854.3  5026.9  858.95  5035.5  860.87
  5049.8  861.37  5121.7  869.55  5168.2  873.29  5185.7  875.29
#Mann= 3 ,-1,0
    4773     .14       0  4983.6    .045       0  5016.6     .14       0
#XS Ineff= 2 , 0
          4959.5  865.75  5040.5           864.3
Permanent Ineff=
       F       F
Bank Sta=4983.6,5016.6
XS Rating Curve= 0 ,0
Exp/Cntr=0.5,0.3