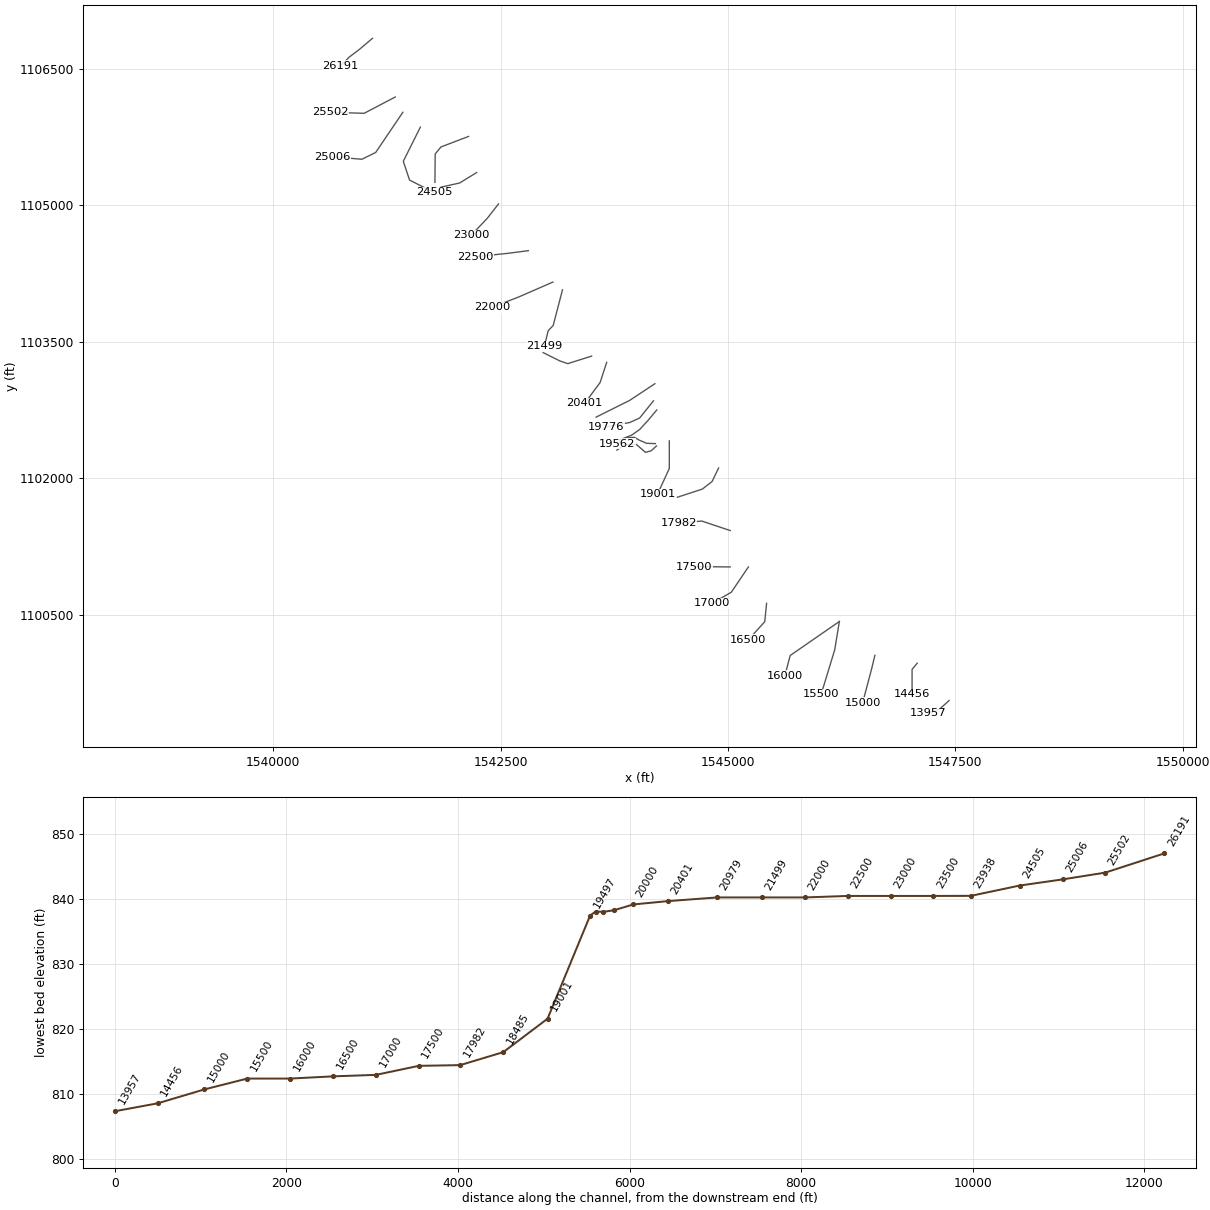
HEC-RAS study GeorgesCreek.prj: Georges Creek Limited Detail Study

--- GeorgesCreek.g06 (geometry) --- (continued)

Type RM Length L Ch R = 3 ,26239   ,,,
BEGIN DESCRIPTION:
Norman Dr. (Georges Cr.) - TOR
Structure ID: LDS_GC_09
Approximate Survey Structure
END DESCRIPTION:
Bridge Culvert--1,0,-1,-1, 0
Deck Dist Width WeirC Skew NumUp NumDn MinLoCord MaxHiCord MaxSubmerge Is_Ogee
13,28,3,0, 19, 19, , , , 0, 1,1,,
  4730.4  4820.9  4821.2  4862.8  4958.1    4961    4964  4972.5  4972.5  5027.5
  5027.5  5051.7  5054.2  5102.8    5107  5118.6  5200.3  5215.1  5216.7
  871.81  868.52  868.49  866.97  865.76  865.73   864.3   864.3   864.3   864.3
   864.3   864.3  864.91  866.93  867.52  868.03  871.16  872.06  872.05
   827.3   827.3   827.3   827.3   827.3   827.3   827.3   827.3   864.3   864.3
   827.3   827.3   827.3   827.3   827.3   827.3   827.3   827.3   827.3
  4730.4  4820.9  4821.2  4862.8  4958.1    4961    4964  4972.5  4972.5  5027.5
  5027.5  5051.7  5054.2  5102.8    5107  5118.6  5200.3  5215.1  5216.7
  871.81  868.52  868.49  866.97  865.76  865.73   864.3   864.3   864.3   864.3
   864.3   864.3  864.91  866.93  867.52  868.03  871.16  872.06  872.05
   827.3   827.3   827.3   827.3   827.3   827.3   827.3   827.3   864.3   864.3
   827.3   827.3   827.3   827.3   827.3   827.3   827.3   827.3   827.3
Abutment Skew #Up #Dn= , 2 , 2
  4972.5  4974.5
   864.3  857.68
  4972.5  4974.5
   864.3  856.78
Abutment Skew #Up #Dn= , 2 , 2
  5025.5  5027.5
  859.09   864.3
  5025.5  5027.5
  857.65   864.3
BR Coef=-1 ,-1 , 0 ,1.25, 0 ,,,0.8,0,2,0,
WSPro=,,,, 1 ,,,, 0 ,,,, 0 ,,,,-1 ,-1 ,-1 , 0 , 0 , 0 , 0 , 0
BC Design=,, 0 ,, 0 ,,,,,,
BC HTab HWMax=875.29
BC Use User HTab Curves=0
BC User HTab FreeFlow(D)= 0

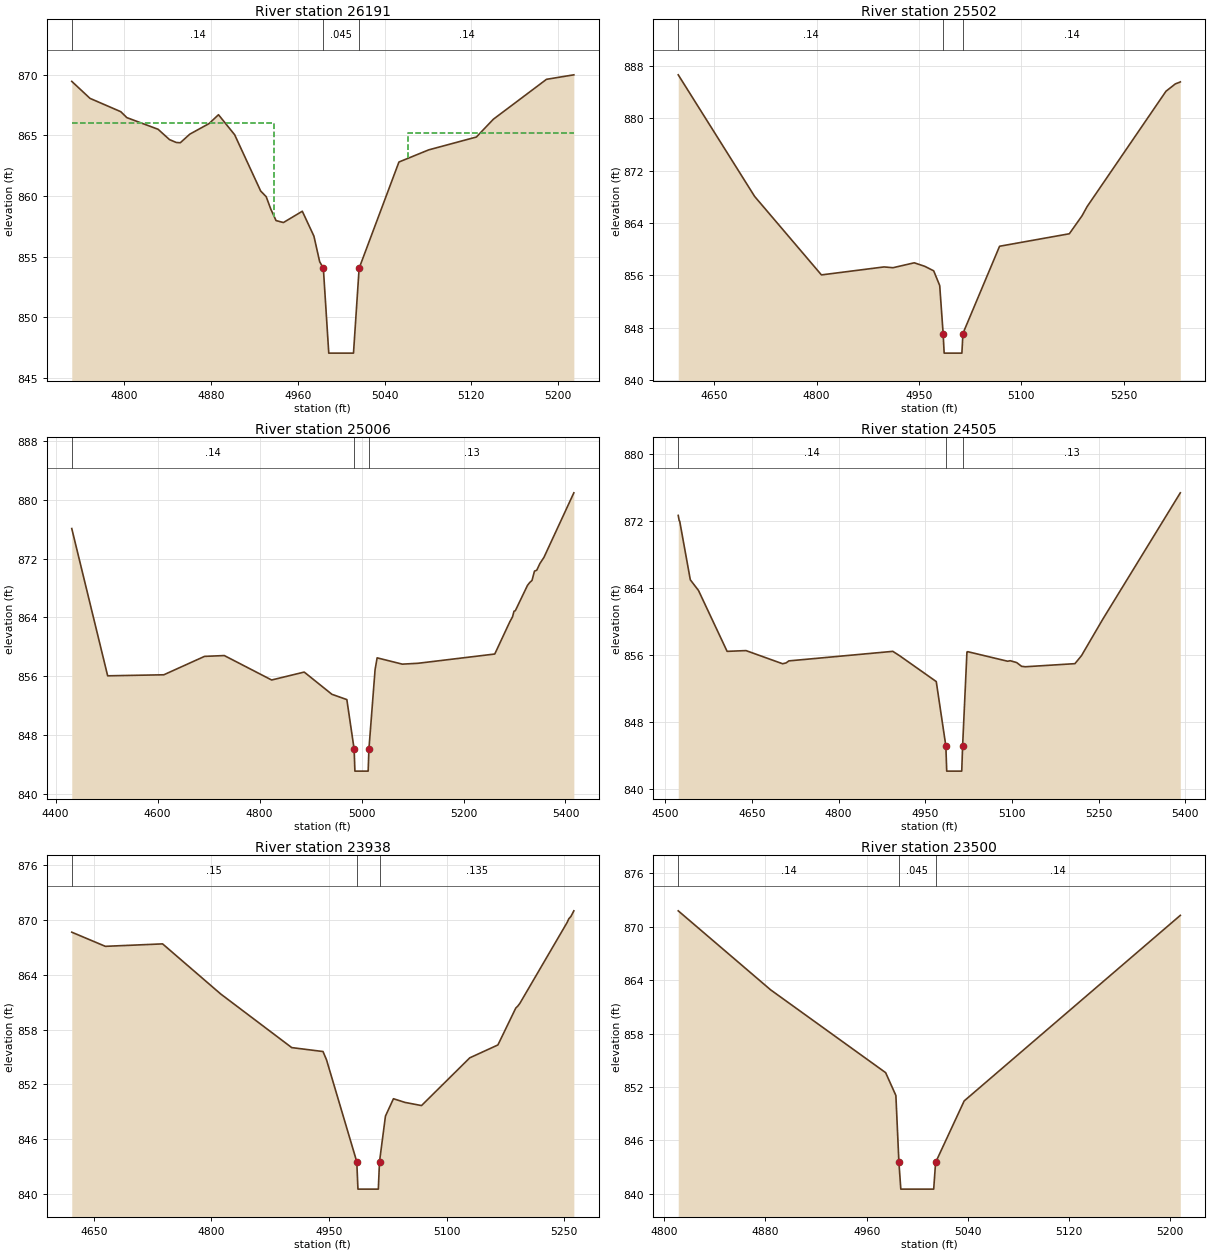
Type RM Length L Ch R = 1 ,26191   ,689,689,689
BEGIN DESCRIPTION:
Georges Creek 52.0
END DESCRIPTION:
XS GIS Cut Line= 4
      1541090.77      1106838.05      1540946.04      1106715.58
       1540834.7      1106631.46      1540741.93      1106534.98
#Sta/Elev= 30
  4751.6  869.46  4768.4  868.06  4796.8  866.96  4802.4  866.47  4831.2  865.51
  4841.7  864.66    4848  864.42  4851.7   864.4  4860.5  865.11  4878.2  865.98
  4886.9  866.71  4901.8  865.06  4925.8  860.42  4930.9  859.95  4935.2  858.91
    4940  857.98  4946.8  857.82  4964.2  858.75  4974.9   856.7  4980.2  854.59
  4983.6  854.05  4988.6  847.05  5011.4  847.05  5016.6  854.05  5053.3  862.81
  5080.7  863.81  5124.7  864.87  5140.4  866.34  5189.4  869.63  5214.6     870
#Mann= 3 ,-1,0
  4751.6     .14       0  4983.6    .045       0  5016.6     .14       0
#XS Ineff= 2 , 0
          4938.5  866.01  5061.5          865.21
Permanent Ineff=
       F       F
Bank Sta=4983.6,5016.6
XS Rating Curve= 0 ,0
Exp/Cntr=0.5,0.3

Type RM Length L Ch R = 1 ,25502   ,496,496,496
BEGIN DESCRIPTION:
Georges Creek 51.0
END DESCRIPTION:
XS GIS Cut Line= 3
      1541341.48      1106192.99       1540999.1      1106013.52
        1540625.        1106025.
#Sta/Elev= 21
  4597.4  886.64  4709.4  868.04  4807.2  856.05    4899  857.27  4912.1  857.15
  4943.2   857.9  4958.7  857.36  4971.7  856.67  4980.5  854.42  4985.5  847.09
    4987  844.09    5013  844.09  5014.5  847.09  5068.2  860.43  5170.4  862.34
  5189.1   865.1  5196.5   866.5    5312  884.13  5325.8  885.26  5332.2  885.51
    5333  885.56
#Mann= 3 ,-1,0
  4597.4     .14       0  4985.5    .045       0  5014.5     .14       0
Bank Sta=4985.5,5014.5
XS Rating Curve= 0 ,0
Exp/Cntr=0.3,0.1

Type RM Length L Ch R = 1 ,25006   ,501,501,501
BEGIN DESCRIPTION:
Georges Creek 50.0
END DESCRIPTION:
XS GIS Cut Line= 4
        1541425.        1106025.      1541126.11      1105582.78
      1540974.25      1105508.23      1540645.68      1105535.85
#Sta/Elev= 30
  4431.7  876.11  4502.1  856.04  4612.2  856.18  4692.1  858.69  4730.9   858.8
  4823.7  855.47  4887.6  856.55  4941.9  853.52  4971.2   852.8  4985.5  846.05
    4987  843.05    5013  843.05  5014.5  846.05  5026.6   856.9  5030.6  858.49
    5080  857.63    5111  857.75  5261.3  859.01    5291  863.43  5296.1  864.07
  5299.1  864.85  5301.6  864.91  5325.5  868.37  5330.2  868.78  5334.3  869.03
  5339.2  870.31  5343.6  870.43  5349.8  871.34  5357.8  872.19  5416.4  880.98
#Mann= 3 ,-1,0
  4431.7     .14       0  4985.5    .045       0  5014.5     .13       0
Bank Sta=4985.5,5014.5
XS Rating Curve= 0 ,0
Exp/Cntr=0.3,0.1

Type RM Length L Ch R = 1 ,24505   ,567,567,567
BEGIN DESCRIPTION:
Georges Creek 49.0
END DESCRIPTION:
XS GIS Cut Line= 4
      1541617.59      1105861.66      1541429.83      1105486.15
      1541498.86      1105279.06      1541766.69      1105143.77
#Sta/Elev= 28
  4522.3  872.65  4523.9  872.04  4524.8  871.98  4543.2  864.96  4557.4  863.68
  4606.9  856.41  4639.6   856.5  4702.9  854.93  4709.1  855.03  4713.7  855.27
  4893.7  856.41    4905  855.91  4968.9   852.8  4985.5   845.1    4987   842.1
    5013   842.1  5014.5   845.1    5022  856.33  5023.4  856.37  5092.4  855.23
  5096.9  855.29  5108.1  855.07  5116.6  854.62  5123.3  854.57  5208.9  854.94
  5220.2  855.89  5257.2  860.26  5391.3  875.35
#Mann= 3 ,-1,0
  4522.3     .14       0  4985.5    .045       0  5014.5     .13       0
Bank Sta=4985.5,5014.5
XS Rating Curve= 0 ,0
Exp/Cntr=0.3,0.1

Type RM Length L Ch R = 1 ,23938   ,438,438,438
BEGIN DESCRIPTION:
Georges Creek 48.0
END DESCRIPTION:
XS GIS Cut Line= 4
      1542147.72       1105759.5        1541844.      1105643.53
      1541780.49      1105566.22      1541777.73      1105254.21
#Sta/Elev= 24
  4621.8  868.66  4664.7  867.11  4737.7  867.38  4811.9  861.89  4902.5  856.02
  4942.4  855.59  4946.9  854.68  4985.5  843.52    4987  840.52    5013  840.52
  5014.5  843.52  5022.1  848.52  5032.3  850.42  5046.9  850.02  5068.1  849.67
  5129.7   854.9  5165.6  856.31  5188.4  860.35  5190.9  860.56  5193.5  860.85
  5253.9  869.72  5256.1  870.13  5258.8  870.39  5262.5     871
#Mann= 3 ,-1,0
  4621.8     .15       0  4985.5    .045       0  5014.5    .135       0
Bank Sta=4985.5,5014.5
XS Rating Curve= 0 ,0
Exp/Cntr=0.3,0.1

Type RM Length L Ch R = 1 ,23500   ,500,500,500
BEGIN DESCRIPTION:
Georges Creek 47.0
END DESCRIPTION:
XS GIS Cut Line= 3
      1542236.07       1105361.9      1542049.68      1105247.53
      1541846.76      1105201.75
#Sta/Elev= 10
    4811   871.8    4884  862.92    4975   853.6  4983.1  851.03  4985.5   843.5
    4987   840.5    5013   840.5  5014.5   843.5  5037.1  850.42    5208  871.29
#Mann= 3 ,-1,0
    4811     .14       0  4985.5    .045       0  5014.5     .14       0
Bank Sta=4985.5,5014.5
XS Rating Curve= 0 ,0
Exp/Cntr=0.3,0.1

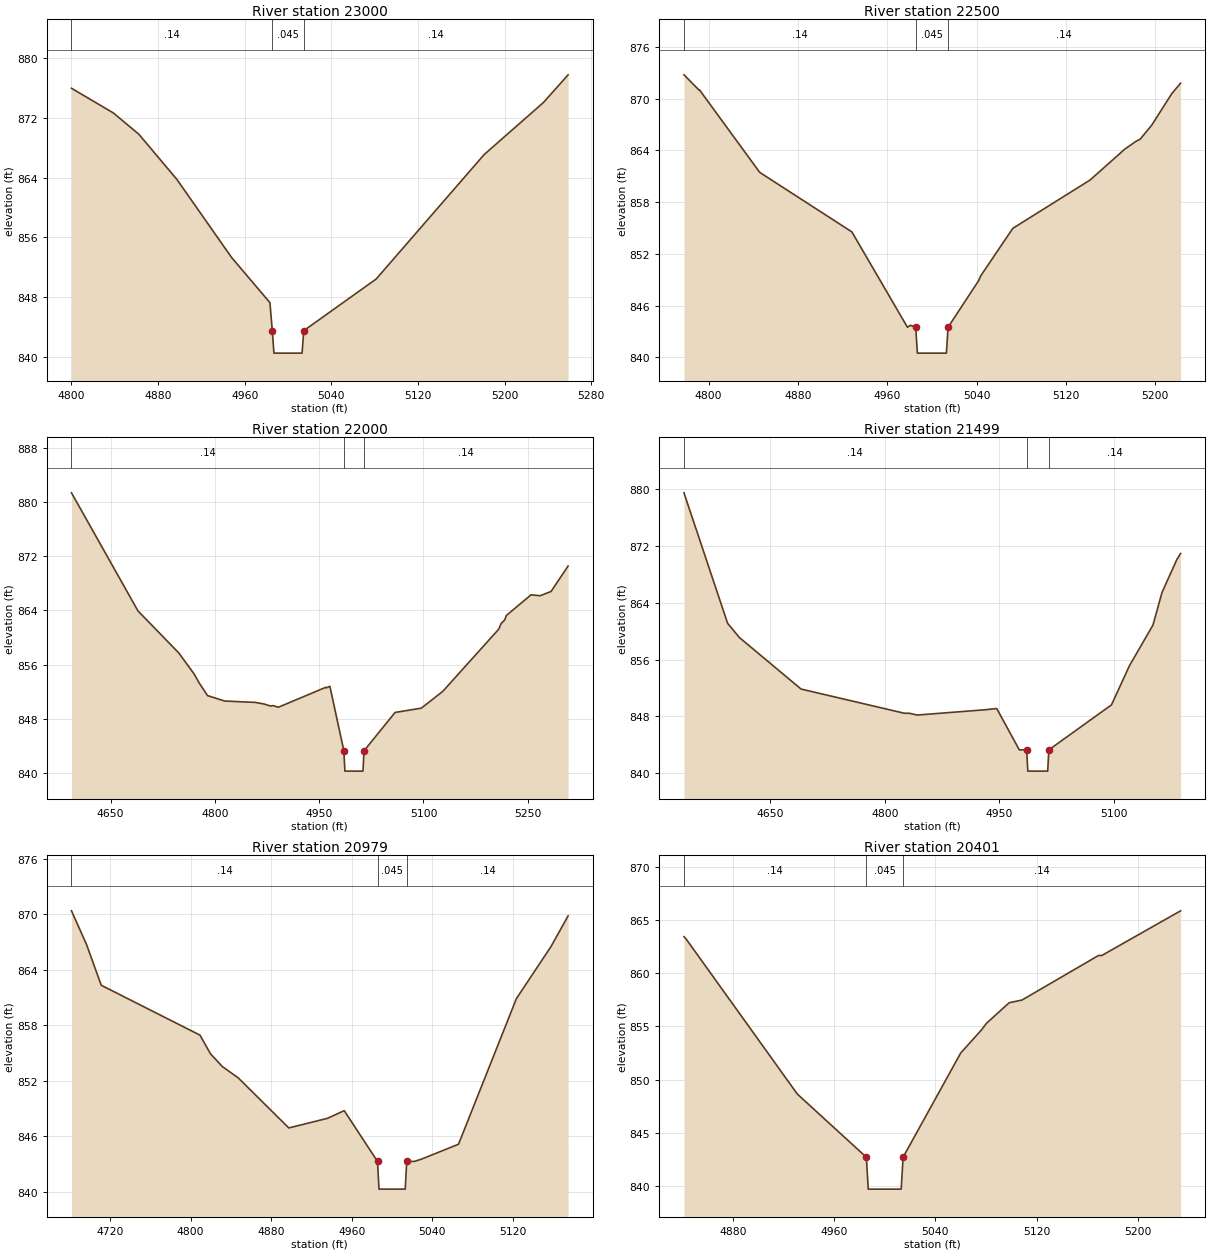
Type RM Length L Ch R = 1 ,23000   ,500,500,500
BEGIN DESCRIPTION:
Georges Creek 46.0
END DESCRIPTION:
XS GIS Cut Line= 3
      1542476.29      1105016.76      1542353.54      1104859.02
      1542175.33      1104671.62
#Sta/Elev= 14
  4800.1  875.96  4838.6  872.67  4862.2  869.82  4897.5  863.74    4948  853.29
  4983.3  847.26  4985.5   843.5    4987   840.5    5013   840.5  5014.5   843.5
  5081.4  850.42    5181  867.07  5235.8  874.05  5258.6  877.76
#Mann= 3 ,-1,0
  4800.1     .14       0  4985.5    .045       0  5014.5     .14       0
Bank Sta=4985.5,5014.5
XS Rating Curve= 0 ,0
Exp/Cntr=0.3,0.1

Type RM Length L Ch R = 1 ,22500   ,500,500,500
BEGIN DESCRIPTION:
Georges Creek 45.0
END DESCRIPTION:
XS GIS Cut Line= 3
      1542804.86      1104503.19      1542584.69      1104474.16
      1542225.03      1104436.93
#Sta/Elev= 22
  4777.9  872.77  4791.5  870.99  4791.9  871.01  4845.4  861.52  4846.7  861.38
  4928.3  854.56  4978.1   843.5  4980.7  843.73  4985.5   843.5    4987   840.5
    5013   840.5  5014.5   843.5    5042  848.93  5043.6  849.43  5072.5  854.97
  5141.7  860.57  5172.7  864.14  5182.8  865.06  5186.6  865.31  5197.1  866.96
  5214.9  870.59  5222.8   871.8
#Mann= 3 ,-1,0
  4777.9     .14       0  4985.5    .045       0  5014.5     .14       0
Bank Sta=4985.5,5014.5
XS Rating Curve= 0 ,0
Exp/Cntr=0.3,0.1

Type RM Length L Ch R = 1 ,22000   ,501,501,501
BEGIN DESCRIPTION:
Georges Creek 44.0
END DESCRIPTION:
XS GIS Cut Line= 3
      1543075.45      1104158.05      1542697.28      1103992.93
      1542410.02      1103881.94
#Sta/Elev= 30
  4593.8  881.33  4689.4  863.91  4748.1  857.71  4770.5  854.55  4777.6  853.25
  4789.5  851.41  4814.2  850.61    4858  850.41  4870.9  850.17  4880.1  849.87
  4883.2  849.94  4891.4   849.7  4959.6  852.64  4960.5  852.56  4965.4  852.79
  4985.5  843.27    4987  840.27    5013  840.27  5014.5  843.27  5059.2  848.93
  5096.9  849.56  5127.9  852.05  5208.2  861.21  5211.8  862.06  5216.9  862.58
  5219.2  863.23  5254.7  866.28  5267.9  866.15  5283.5  866.78    5308  870.53
#Mann= 3 ,-1,0
  4593.8     .14       0  4985.5    .045       0  5014.5     .14       0
Bank Sta=4985.5,5014.5
XS Rating Curve= 0 ,0
Exp/Cntr=0.3,0.1

Type RM Length L Ch R = 1 ,21499   ,520,520,520
BEGIN DESCRIPTION:
Georges Creek 43.0
END DESCRIPTION:
XS GIS Cut Line= 4
      1543180.37      1104072.46      1543078.21      1103680.38
      1543022.99       1103622.4      1542981.57      1103451.21
#Sta/Elev= 21
  4537.6  879.53  4594.6  861.13    4610  859.12  4690.6  851.85  4825.4  848.44
  4832.4  848.43  4842.3  848.18  4930.5  848.92  4946.4   849.1  4975.9  843.27
  4976.7  843.27  4985.5  843.27    4987  840.27    5013  840.27  5014.5  843.27
  5096.4  849.62  5119.9  855.15  5150.6  860.87  5162.4  865.47  5181.9  870.14
  5186.7  870.97
#Mann= 3 ,-1,0
  4537.6     .14       0  4985.5    .045       0  5014.5     .14       0
Bank Sta=4985.5,5014.5
XS Rating Curve= 0 ,0
Exp/Cntr=0.3,0.1

Type RM Length L Ch R = 1 ,20979   ,578,578,578
BEGIN DESCRIPTION:
Georges Creek 42.0
END DESCRIPTION:
XS GIS Cut Line= 4
      1543500.66      1103343.53      1543238.36      1103260.69
        1543150.      1103291.07      1542967.77      1103382.18
#Sta/Elev= 20
  4681.9  870.38  4696.8  866.74  4711.4  862.33  4809.4  856.93  4819.8  854.91
  4831.7  853.52  4847.3  852.31  4897.5  846.89  4935.9  847.93  4952.5  848.76
  4985.5  843.27    4987  840.27    5013  840.27  5014.5  843.27  5022.1  843.27
  5029.3  843.52  5065.9  845.13  5123.3  860.88  5157.7  866.53  5174.6  869.83
#Mann= 3 ,-1,0
  4681.9     .14       0  4985.5    .045       0  5014.5     .14       0
Bank Sta=4985.5,5014.5
XS Rating Curve= 0 ,0
Exp/Cntr=0.3,0.1

Type RM Length L Ch R = 1 ,20401   ,401,401,401
BEGIN DESCRIPTION:
Georges Creek 41.0
END DESCRIPTION:
XS GIS Cut Line= 3
      1543666.33       1103274.5      1543594.54      1103053.61
        1543425.        1102825.
#Sta/Elev= 15
  4841.5  863.44  4843.2  863.22    4931  848.64  4985.5   842.7    4987   839.7
    5013   839.7  5014.5   842.7    5060   852.5  5076.6   854.7  5080.3  855.29
  5098.3  857.23  5108.4  857.48  5168.8  861.67  5171.4  861.67  5233.6  865.87
#Mann= 3 ,-1,0
  4841.5     .14       0  4985.5    .045       0  5014.5     .14       0
Bank Sta=4985.5,5014.5
XS Rating Curve= 0 ,0
Exp/Cntr=0.3,0.1

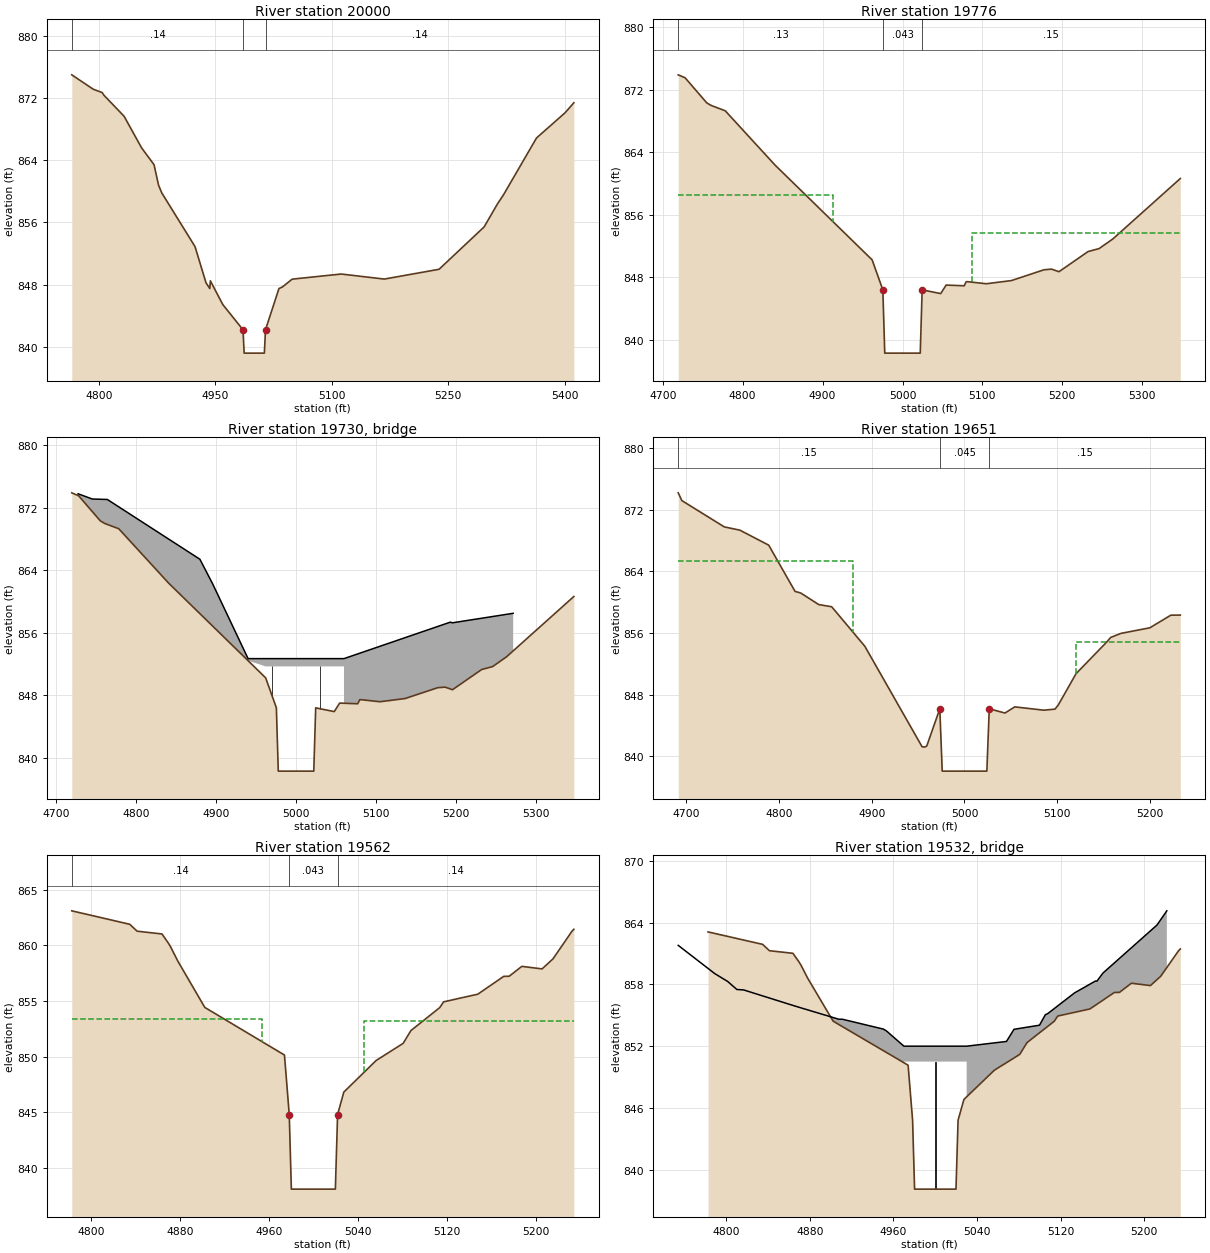
Type RM Length L Ch R = 1 ,20000   ,224,224,224
BEGIN DESCRIPTION:
Georges Creek 40.0
END DESCRIPTION:
XS GIS Cut Line= 3
      1544196.46      1103039.81      1543918.93      1102856.43
      1543550.36      1102672.58
#Sta/Elev= 30
  4764.8  874.97  4792.5  873.12    4804  872.69  4806.3  872.34  4832.2  869.65
  4854.8  865.58  4870.8  863.42  4876.7  860.77  4880.8  859.79  4923.7  852.88
  4937.8  848.23  4942.7  847.49  4943.4  848.49  4959.5  845.43  4985.5  842.19
    4987  839.19    5013  839.19  5014.5  842.19  5031.8  847.49  5036.2  847.69
  5048.9   848.7  5112.1  849.36  5167.6  848.71  5238.2  849.97  5296.3  855.42
  5313.5  858.38  5321.1  859.52  5363.8  866.85  5400.7   870.1  5411.9  871.38
#Mann= 3 ,-1,0
  4764.8     .14       0  4985.5    .045       0  5014.5     .14       0
Bank Sta=4985.5,5014.5
XS Rating Curve= 0 ,0
Exp/Cntr=0.5,0.3

Type RM Length L Ch R = 1 ,19776   ,125,125,125
BEGIN DESCRIPTION:
Georges Creek 39.9
END DESCRIPTION:
XS GIS Cut Line= 4
       1544180.9      1102851.99      1544029.03      1102662.86
      1543920.04      1102613.45      1543658.46      1102565.49
#Sta/Elev= 25
  4719.4  873.92    4728  873.54  4755.1  870.33  4760.6     870  4778.2  869.32
  4840.7  862.35    4962  850.24  4975.4   846.4  4977.8   838.3  5022.2   838.3
  5024.6   846.4  5047.8  845.92  5054.6  847.01  5077.2  846.92  5079.7  847.44
  5081.6  847.44    5105  847.18  5136.5  847.59  5177.1  848.97  5186.5  849.05
  5195.8  848.72  5232.2   851.3    5246  851.68  5263.4  852.93  5347.6  860.65
#Mann= 3 ,-1,0
  4719.4     .13       0  4975.4    .043       0  5024.6     .15       0
#XS Ineff= 2 , 0
            4913  858.53    5087          853.65
Permanent Ineff=
       F       F
Bank Sta=4975.4,5024.6
XS Rating Curve= 0 ,0
Exp/Cntr=0.5,0.3

Type RM Length L Ch R = 3 ,19730   ,,,
BEGIN DESCRIPTION:
Saluda Dam Rd. - TOR
Structure ID: LDS_GC_08
Approximate Survey Structure
END DESCRIPTION:
Bridge Culvert--1,0,-1,-1, 0
Deck Dist Width WeirC Skew NumUp NumDn MinLoCord MaxHiCord MaxSubmerge Is_Ogee
27,38,3,0, 13, 13, , , , 0, 1,1,,
  4727.3    4745  4763.9  4879.7    4894  4895.4    4940    4940    5060    5060
  5193.1  5195.4  5271.7
   873.8  873.13  873.07  865.42   862.6  862.33   852.7   852.7   852.7   852.7
  857.37  857.28   858.5
   818.3   818.3   818.3   818.3   818.3   818.3   818.3   851.7   851.7   818.3
   818.3   818.3   818.3
  4727.3    4745  4763.9  4879.7    4894  4895.4    4940    4940    5060    5060
  5193.1  5195.4  5271.7
   873.8  873.13  873.07  865.42   862.6  862.33   852.7   852.7   852.7   852.7
  857.37  857.28   858.5
   818.3   818.3   818.3   818.3   818.3   818.3   818.3   851.7   851.7   818.3
   818.3   818.3   818.3
Pier Skew, UpSta & Num, DnSta & Num=  ,4970, 2 ,4970, 2 , 0 , 0 , 0 ,0,0
       1       1
  850.77   851.7
       1       1
   839.9   851.7
Pier Skew, UpSta & Num, DnSta & Num=  ,5030, 2 ,5030, 2 , 0 , 0 , 0 ,0,0
       1       1
  849.49   851.7
       1       1
  848.87   851.7
Abutment Skew #Up #Dn= , 2 , 2
    4940    4941
   851.7  854.79
    4940    4941
   851.7  844.04
Abutment Skew #Up #Dn= , 2 , 2
    5059    5060
  846.99   851.7
    5059    5060
  846.33   851.7
BR Coef=-1 ,-1 , 0 ,1.25, 0 ,,,0.8,0,2,0,
WSPro=,,,, 1 ,,,, 0 ,,,, 0 ,,,,-1 ,-1 ,-1 , 0 , 0 , 0 , 0 , 0
BC Design=,, 0 ,, 0 ,,,,,,
BC HTab HWMax=873.92
BC Use User HTab Curves=0
BC User HTab FreeFlow(D)= 0

Type RM Length L Ch R = 1 ,19651   ,89,89,89
BEGIN DESCRIPTION:
Georges Creek 39.6
END DESCRIPTION:
XS GIS Cut Line= 5
      1544216.64      1102750.74       1544127.3      1102643.53
      1544029.02      1102536.32      1543939.68      1102473.78
       1543802.7      1102420.18
#Sta/Elev= 29
  4691.5  874.22  4695.4  873.21  4741.2  869.79  4757.9  869.37    4789  867.42
  4817.4  861.41  4823.5   861.2  4842.9   859.7  4856.9  859.41  4892.6  854.28
  4954.3  841.22  4956.8  841.17  4959.3   841.3  4973.4  846.15    4976  838.05
  5024.1  838.05  5026.7  846.15  5043.6   845.6  5054.2   846.4  5085.5  845.97
  5097.6  846.11  5101.2  846.67  5120.2  850.71  5153.7  854.88  5157.5  855.42
  5168.6  855.95  5199.8  856.68  5222.4  858.32  5232.6  858.33
#Mann= 3 ,-1,0
  4691.5     .15       0  4973.4    .045       0  5026.7     .15       0
#XS Ineff= 2 , 0
            4880  865.36    5120          854.81
Permanent Ineff=
       F       F
Bank Sta=4973.4,5026.7
XS Rating Curve= 0 ,0
Exp/Cntr=0.5,0.3

Type RM Length L Ch R = 1 ,19562   ,65,65,65
BEGIN DESCRIPTION:
Georges Creek 39.3
END DESCRIPTION:
XS GIS Cut Line= 6
      1544201.75      1102381.47      1544106.45      1102384.44
      1544023.07      1102420.18      1543972.44      1102449.96
      1543886.08      1102446.98      1543784.83      1102381.47
#Sta/Elev= 27
  4782.6  863.11  4834.8   861.9  4841.4  861.28  4863.8  861.03  4869.5  860.21
  4871.4   859.9    4878   858.6  4902.3  854.43    4974  850.15  4978.3   844.8
  4980.2   838.1  5019.8   838.1  5021.8   844.8  5027.4  846.82  5056.5  849.66
  5080.8   851.2  5087.8  852.35  5113.8  854.42  5117.2  854.93    5148  855.62
  5171.3  857.22  5176.2  857.23  5187.6  858.12  5205.8  857.89  5215.7   858.8
  5232.8  861.29  5234.4  861.45
#Mann= 3 ,-1,0
  4782.6     .14       0  4978.3    .043       0  5021.8     .14       0
#XS Ineff= 2 , 0
            4954  853.42    5046           853.2
Permanent Ineff=
       F       F
Bank Sta=4978.3,5021.8
XS Rating Curve= 0 ,0
Exp/Cntr=0.5,0.3

Type RM Length L Ch R = 3 ,19532   ,,,
BEGIN DESCRIPTION:
Old Saluda Dam Rd. - TOR
Structure ID: LDS_GC_07
Approximate Survey Structure
END DESCRIPTION:
Bridge Culvert--1,0,-1,-1, 0
Deck Dist Width WeirC Skew NumUp NumDn MinLoCord MaxHiCord MaxSubmerge Is_Ogee
16,28,3,0, 25, 25, , , , 0, 1,1,,
  4754.1  4789.1  4801.4  4810.2  4816.6  4865.8  4907.7  4911.1  4950.4  4953.3
    4970    4970    5030    5030  5068.1  5075.3  5099.7  5105.3  5107.5  5133.2
  5153.3  5154.6  5160.4  5212.1  5221.5
   861.8  859.05  858.29  857.51  857.47   855.9  854.62  854.62  853.66  853.48
     852     852     852     852  852.46  853.64  854.04  855.06  855.16  857.18
  858.34  858.32  859.11  863.78  865.16
   818.1   818.1   818.1   818.1   818.1   818.1   818.1   818.1   818.1   818.1
   818.1   850.5   850.5   818.1   818.1   818.1   818.1   818.1   818.1   818.1
   818.1   818.1   818.1   818.1   818.1
  4754.1  4789.1  4801.4  4810.2  4816.6  4865.8  4907.7  4911.1  4950.4  4953.3
    4970    4970    5030    5030  5068.1  5075.3  5099.7  5105.3  5107.5  5133.2
  5153.3  5154.6  5160.4  5212.1  5221.5
   861.8  859.05  858.29  857.51  857.47   855.9  854.62  854.62  853.66  853.48
     852     852     852     852  852.46  853.64  854.04  855.06  855.16  857.18
  858.34  858.32  859.11  863.78  865.16
   818.1   818.1   818.1   818.1   818.1   818.1   818.1   818.1   818.1   818.1
   818.1   850.5   850.5   818.1   818.1   818.1   818.1   818.1   818.1   818.1
   818.1   818.1   818.1   818.1   818.1
Pier Skew, UpSta & Num, DnSta & Num=  ,5000, 2 ,5000, 2 , 0 , 0 , 0 ,0,0
       1       1
   838.1   850.5
       1       1
  837.85   850.5
Abutment Skew #Up #Dn= , 2 , 2
    4970    4971
   850.5  852.14
    4970    4971
   850.5  846.04
Abutment Skew #Up #Dn= , 2 , 2
    5029    5030
  846.98   850.5
    5029    5030
  844.37   850.5
BR Coef=-1 ,-1 , 0 ,1.25, 0 ,,,0.8,0,2,0,
WSPro=,,,, 1 ,,,, 0 ,,,, 0 ,,,,-1 ,-1 ,-1 , 0 , 0 , 0 , 0 , 0
BC Design=,, 0 ,, 0 ,,,,,,
BC HTab HWMax=863.11
BC Use User HTab Curves=0
BC User HTab FreeFlow(D)= 0

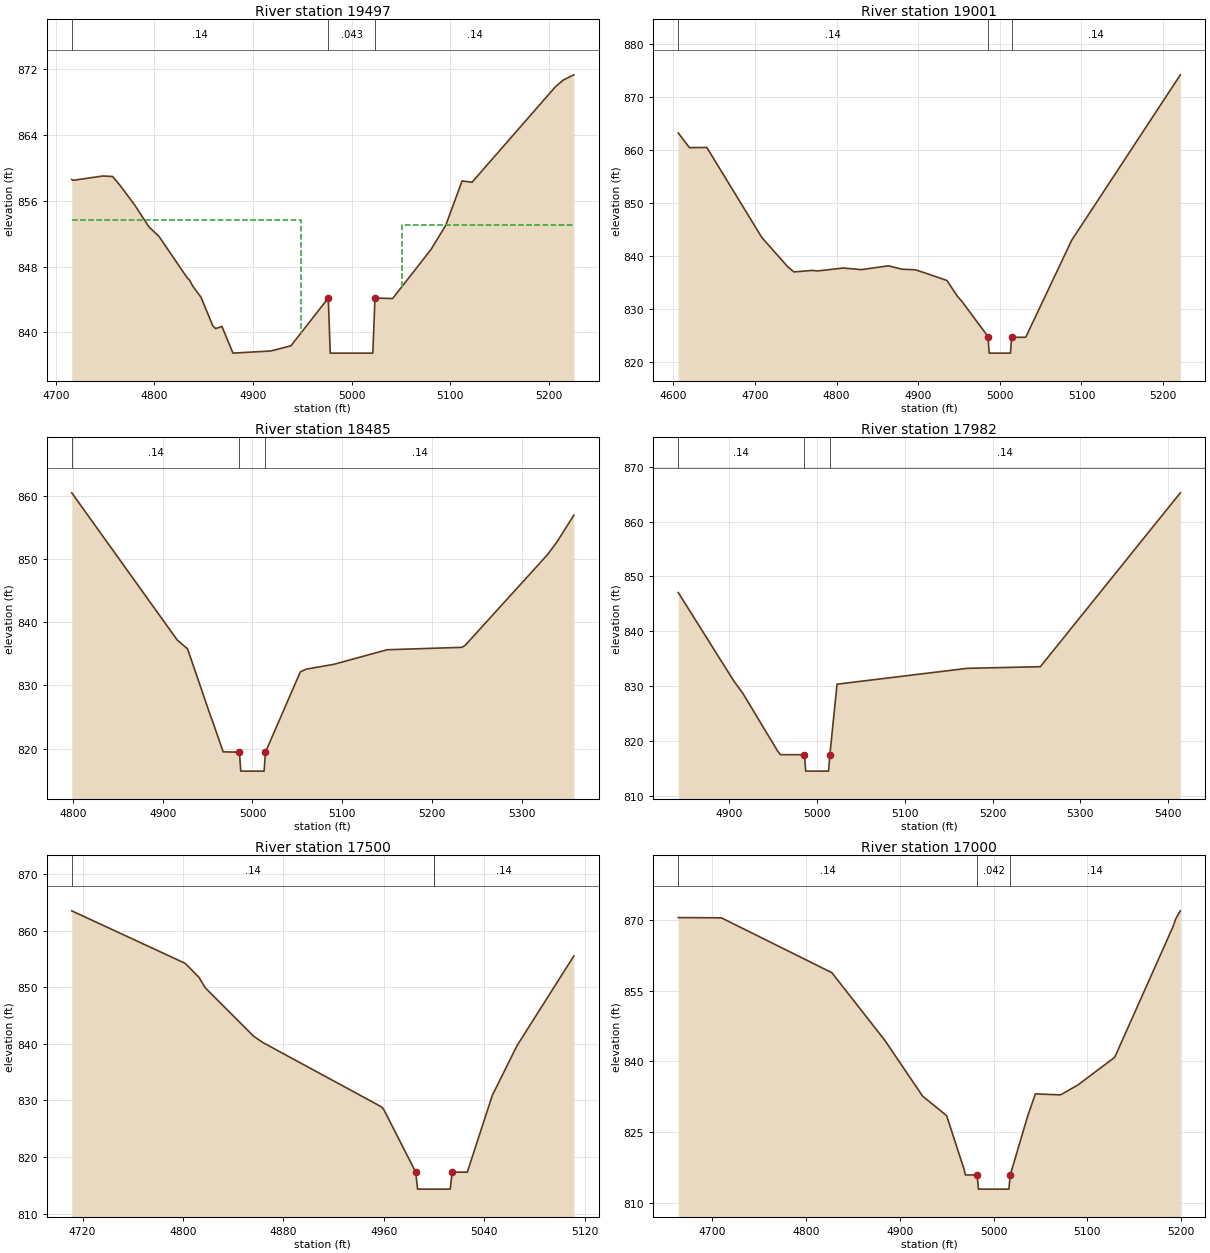
Type RM Length L Ch R = 1 ,19497   ,496,496,496
BEGIN DESCRIPTION:
Georges Creek 39.0
END DESCRIPTION:
XS GIS Cut Line= 6
      1544213.59      1102354.77      1544155.46      1102302.46
      1544092.97      1102285.02       1543992.7      1102372.21
      1543868.21      1102372.53      1543778.87      1102309.99
#Sta/Elev= 30
  4716.1   858.6  4717.4  858.49  4747.7  859.02  4757.5  858.96  4765.1  857.88
  4779.9   855.5  4794.3  852.85  4804.7  851.66    4833  846.68  4835.6  846.36
  4839.4  845.53  4847.2  844.29  4859.2  840.81  4862.1  840.46  4868.5  840.72
  4879.7  837.48    4918  837.74  4938.5  838.37  4976.4  844.18  4978.4  837.48
  5021.6  837.48  5023.8  844.18  5041.7  844.12  5080.8  850.11  5095.6  853.02
  5112.2  858.42  5122.3  858.26  5206.9  869.87  5214.8  870.68  5225.6  871.32
#Mann= 3 ,-1,0
  4716.1     .14       0  4976.4    .043       0  5023.8     .14       0
#XS Ineff= 2 , 0
            4949  853.69    5051          853.03
Permanent Ineff=
       F       F
Bank Sta=4976.4,5023.8
XS Rating Curve= 0 ,0
Exp/Cntr=0.5,0.3

Type RM Length L Ch R = 1 ,19001   ,516,516,516
BEGIN DESCRIPTION:
Georges Creek 38.0
END DESCRIPTION:
XS GIS Cut Line= 3
      1544355.12      1102411.25      1544355.12      1102107.49
        1544225.        1101825.
#Sta/Elev= 26
  4606.2  863.24  4619.9  860.45  4641.2  860.49  4708.6  843.46  4740.3  837.93
  4747.9  836.95  4770.5  837.24  4776.9  837.14  4808.3  837.69  4830.4  837.39
  4863.6  838.11  4879.9  837.48  4896.6  837.35    4910  836.68  4935.3  835.33
  4947.8   832.4  4953.9  831.31  4985.4  824.77  4985.5   824.6    4987   821.6
    5013   821.6  5014.5   824.6  5031.7   824.6    5088  842.95  5220.5  874.09
    5221  874.22
#Mann= 3 ,-1,0
  4606.2     .14       0  4985.5    .043       0  5014.5     .14       0
Bank Sta=4985.5,5014.5
XS Rating Curve= 0 ,0
Exp/Cntr=0.3,0.1

Type RM Length L Ch R = 1 ,18485   ,503,503,503
BEGIN DESCRIPTION:
Georges Creek 37.0
END DESCRIPTION:
XS GIS Cut Line= 4
      1544897.11      1102113.45      1544825.64      1101964.55
      1544718.43      1101881.16      1544444.46      1101791.82
#Sta/Elev= 19
  4798.7  860.47  4916.2  837.19  4927.7   835.8  4953.9  824.94    4955  824.58
  4967.4   819.5  4985.5  819.45    4987  816.45    5013  816.45  5014.5  819.45
  5053.4  832.16    5060  832.58  5090.9  833.35    5150  835.65  5233.3  836.03
    5237  836.34  5328.3  850.62  5339.3   852.7  5358.1  856.94
#Mann= 3 ,-1,0
  4798.7     .14       0  4985.5    .043       0  5014.5     .14       0
Bank Sta=4985.5,5014.5
XS Rating Curve= 0 ,0
Exp/Cntr=0.3,0.1

Type RM Length L Ch R = 1 ,17982   ,482,482,482
BEGIN DESCRIPTION:
Georges Creek 36.0
END DESCRIPTION:
XS GIS Cut Line= 3
        1545025.        1101425.      1544712.48      1101529.76
      1544456.37      1101505.94
#Sta/Elev= 13
  4841.6  847.05  4905.1  830.87  4915.3  828.65  4954.3  818.28  4958.1  817.45
  4985.5  817.45    4987  814.45    5013  814.45  5014.5  817.45  5022.7  830.32
  5171.2  833.21  5254.5  833.51  5414.1  865.24
#Mann= 3 ,-1,0
  4841.6     .14       0  4985.5    .043       0  5014.5     .14       0
Bank Sta=4985.5,5014.5
XS Rating Curve= 0 ,0
Exp/Cntr=0.3,0.1

Type RM Length L Ch R = 1 ,17500   ,500,500,500
BEGIN DESCRIPTION:
Georges Creek 35.0
END DESCRIPTION:
XS GIS Cut Line= 3
        1545025.        1101025.      1544736.45      1101027.88
        1544625.        1101025.
#Sta/Elev= 19
  4711.4   863.5  4801.8  854.22  4812.8  851.75  4817.8   849.9  4856.4  841.34
  4863.8  840.22    4957  829.02  4959.2  828.65  4960.3  828.29  4985.5  817.34
    4987  814.34  4999.9  814.34  5000.1  814.34    5013  814.34  5014.5  817.34
  5026.6  817.34  5046.5  830.89  5066.2  839.68  5111.5  855.53
#Mann= 3 ,-1,0
  4711.4     .14       0  4999.9    .043       0  5000.1     .14       0
Bank Sta=4985.5,5014.5
XS Rating Curve= 0 ,0
Exp/Cntr=0.3,0.1

Type RM Length L Ch R = 1 ,17000   ,500,500,500
BEGIN DESCRIPTION:
Georges Creek 34.0
END DESCRIPTION:
XS GIS Cut Line= 3
        1545225.        1101025.      1545036.37      1100746.39
        1544825.        1100625.
#Sta/Elev= 20
  4663.5  870.44  4709.5  870.39  4827.4  858.77  4883.9  844.45  4924.2  832.64
  4949.8  828.51  4968.3  817.23  4969.8  815.95  4982.3  815.95  4983.8  812.95
  5016.2  812.95  5017.7  815.95  5036.1   828.3  5044.5  833.12  5071.3   832.9
  5089.7  834.98  5129.1  840.85  5190.9  868.33  5194.3   870.2  5199.1  871.87
#Mann= 3 ,-1,0
  4663.5     .14       0  4982.3    .042       0  5017.7     .14       0
Bank Sta=4982.3,5017.7
XS Rating Curve= 0 ,0
Exp/Cntr=0.3,0.1

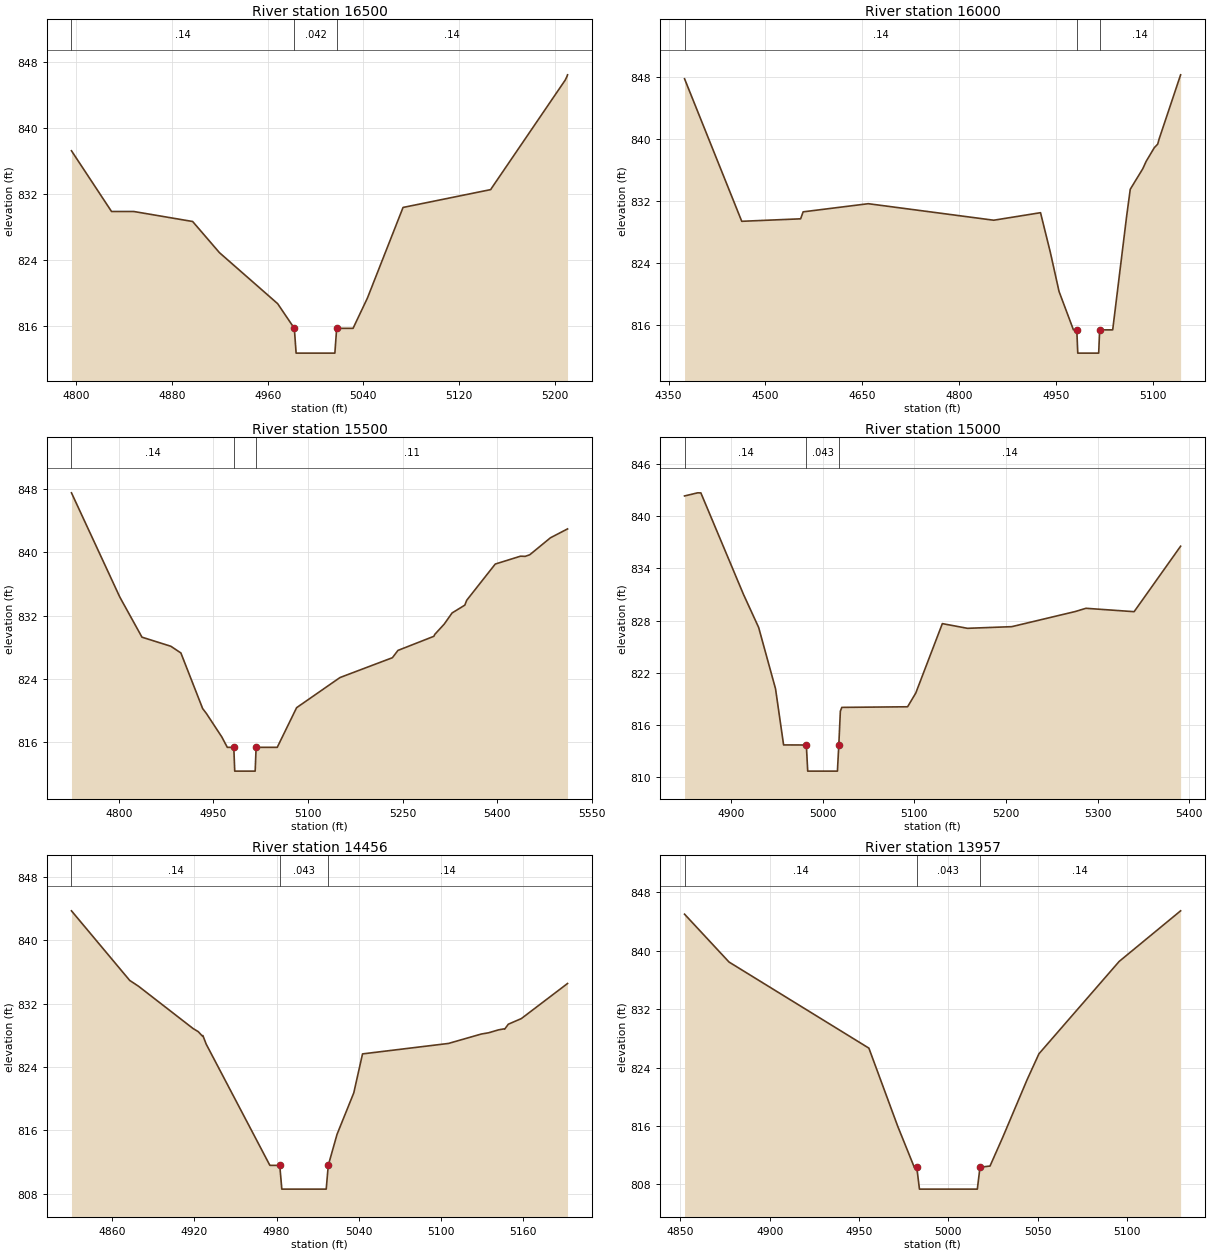
Type RM Length L Ch R = 1 ,16500   ,500,500,500
BEGIN DESCRIPTION:
Georges Creek 33.0
END DESCRIPTION:
XS GIS Cut Line= 3
        1545425.        1100625.      1545404.27      1100422.07
        1545225.        1100225.
#Sta/Elev= 18
    4796  837.21  4829.5  829.86  4848.1  829.86  4897.3  828.65  4919.7  824.88
  4968.4   818.7  4982.3  815.72  4983.8  812.72  5016.2  812.72  5017.7  815.72
  5031.4  815.72  5043.4  819.38  5073.2  830.35  5146.5  832.51  5147.1  832.66
  5208.7  845.75  5210.2  846.19  5210.7   846.4
#Mann= 3 ,-1,0
    4796     .14       0  4982.3    .042       0  5017.7     .14       0
Bank Sta=4982.3,5017.7
XS Rating Curve= 0 ,0
Exp/Cntr=0.3,0.1

Type RM Length L Ch R = 1 ,16000   ,500,500,500
BEGIN DESCRIPTION:
Georges Creek 32.0
END DESCRIPTION:
XS GIS Cut Line= 3
        1546225.        1100425.      1545684.36      1100051.27
        1545625.        1099825.
#Sta/Elev= 23
  4374.7  847.76  4463.3  829.38  4554.5   829.7  4558.4   830.6  4659.3  831.65
  4853.6  829.52  4926.1  830.49  4941.3  825.38  4954.8  820.33  4977.1  815.38
  4982.3  815.38  4983.8  812.38  5016.2  812.38  5017.7  815.38  5037.9  815.38
  5059.5  830.04  5065.1  833.51  5084.5  836.16  5089.7  837.11  5102.4  838.88
  5107.6  839.33  5109.8  839.99  5143.1  848.27
#Mann= 3 ,-1,0
  4374.7     .14       0  4982.3    .042       0  5017.7     .14       0
Bank Sta=4982.3,5017.7
XS Rating Curve= 0 ,0
Exp/Cntr=0.3,0.1

Type RM Length L Ch R = 1 ,15500   ,500,500,500
BEGIN DESCRIPTION:
Georges Creek 31.0
END DESCRIPTION:
XS GIS Cut Line= 3
        1546225.        1100425.      1546174.21      1100114.21
        1546025.        1099625.
#Sta/Elev= 30
  4724.9  847.47  4801.6  834.32  4836.7  829.27  4882.6  828.12  4898.4  827.28
  4932.9  820.27    4939  819.63  4963.3  816.69    4972  815.38  4982.3  815.38
  4983.8  812.38  5016.2  812.38  5017.7  815.38  5051.2  815.38  5081.9  820.38
  5150.7  824.18  5233.8  826.68  5242.6   827.6  5299.6  829.38  5301.1  829.63
  5315.8   830.9  5328.4  832.32  5348.6  833.31  5351.7  833.93  5396.9  838.49
  5436.9  839.48  5444.4  839.46  5451.6  839.66  5484.4   841.8  5511.5  842.92
#Mann= 3 ,-1,0
  4724.9     .14       0  4982.3    .042       0  5017.7     .11       0
Bank Sta=4982.3,5017.7
XS Rating Curve= 0 ,0
Exp/Cntr=0.3,0.1

Type RM Length L Ch R = 1 ,15000   ,544,544,544
BEGIN DESCRIPTION:
Georges Creek 30.0
END DESCRIPTION:
XS GIS Cut Line= 3
      1546615.84      1100053.39      1546580.56      1099907.07
      1546480.86      1099529.58
#Sta/Elev= 23
  4849.5  842.31  4863.8  842.67  4867.3  842.66  4913.7  831.02  4930.3  827.21
  4948.7  820.17  4957.5  813.72  4982.3  813.71  4983.8  810.71  5016.2  810.71
  5017.7  813.71  5019.4  817.59    5021  818.03  5092.7   818.1  5101.6  819.67
  5130.6  827.65    5158  827.11  5206.3   827.3  5275.6  829.04  5275.9  829.05
  5287.2  829.41  5339.7  829.02  5390.4  836.54
#Mann= 3 ,-1,0
  4849.5     .14       0  4982.3    .043       0  5017.7     .14       0
Bank Sta=4982.3,5017.7
XS Rating Curve= 0 ,0
Exp/Cntr=0.3,0.1

Type RM Length L Ch R = 1 ,14456   ,499,499,499
BEGIN DESCRIPTION:
Georges Creek 29.0
END DESCRIPTION:
XS GIS Cut Line= 4
      1547081.23      1099966.76      1547024.82      1099898.26
      1547024.82      1099821.71        1547025.        1099625.
#Sta/Elev= 26
  4830.3  843.72  4872.8  834.93  4879.2   834.2    4919  828.86  4922.8  828.46
  4925.8  827.91  4926.2  827.97  4928.6  826.89    4975   811.6  4975.2  811.57
  4982.3  811.57  4983.8  808.57  5016.2  808.57  5017.7  811.57  5024.1  815.49
  5036.3  820.72  5042.7  825.65  5105.4  826.97  5129.4  828.16  5134.8  828.32
  5141.8  828.68  5145.9  828.81  5146.4  828.77  5149.1   829.4  5158.6  830.11
  5192.3  834.54
#Mann= 3 ,-1,0
  4830.3     .14       0  4982.3    .043       0  5017.7     .14       0
Bank Sta=4982.3,5017.7
XS Rating Curve= 0 ,0
Exp/Cntr=0.3,0.1

Type RM Length L Ch R = 1 ,13957   ,493,493,493
BEGIN DESCRIPTION:
Georges Creek 28.0
END DESCRIPTION:
XS GIS Cut Line= 3
      1547431.79      1099555.77      1547331.05      1099465.11
      1547198.08      1099414.74
#Sta/Elev= 15
  4852.3  844.99  4877.2  838.44  4955.5  826.65  4971.6  815.98  4980.9  810.35
  4982.3  810.35  4983.8  807.35  5016.2  807.35  5017.7  810.35  5023.3  810.51
  5030.4  814.43  5044.1  822.35  5050.7  825.88  5095.6  838.52    5130  845.45
#Mann= 3 ,-1,0
  4852.3     .14       0  4982.3    .043       0  5017.7     .14       0
Bank Sta=4982.3,5017.7
XS Rating Curve= 0 ,0
Exp/Cntr=0.3,0.1