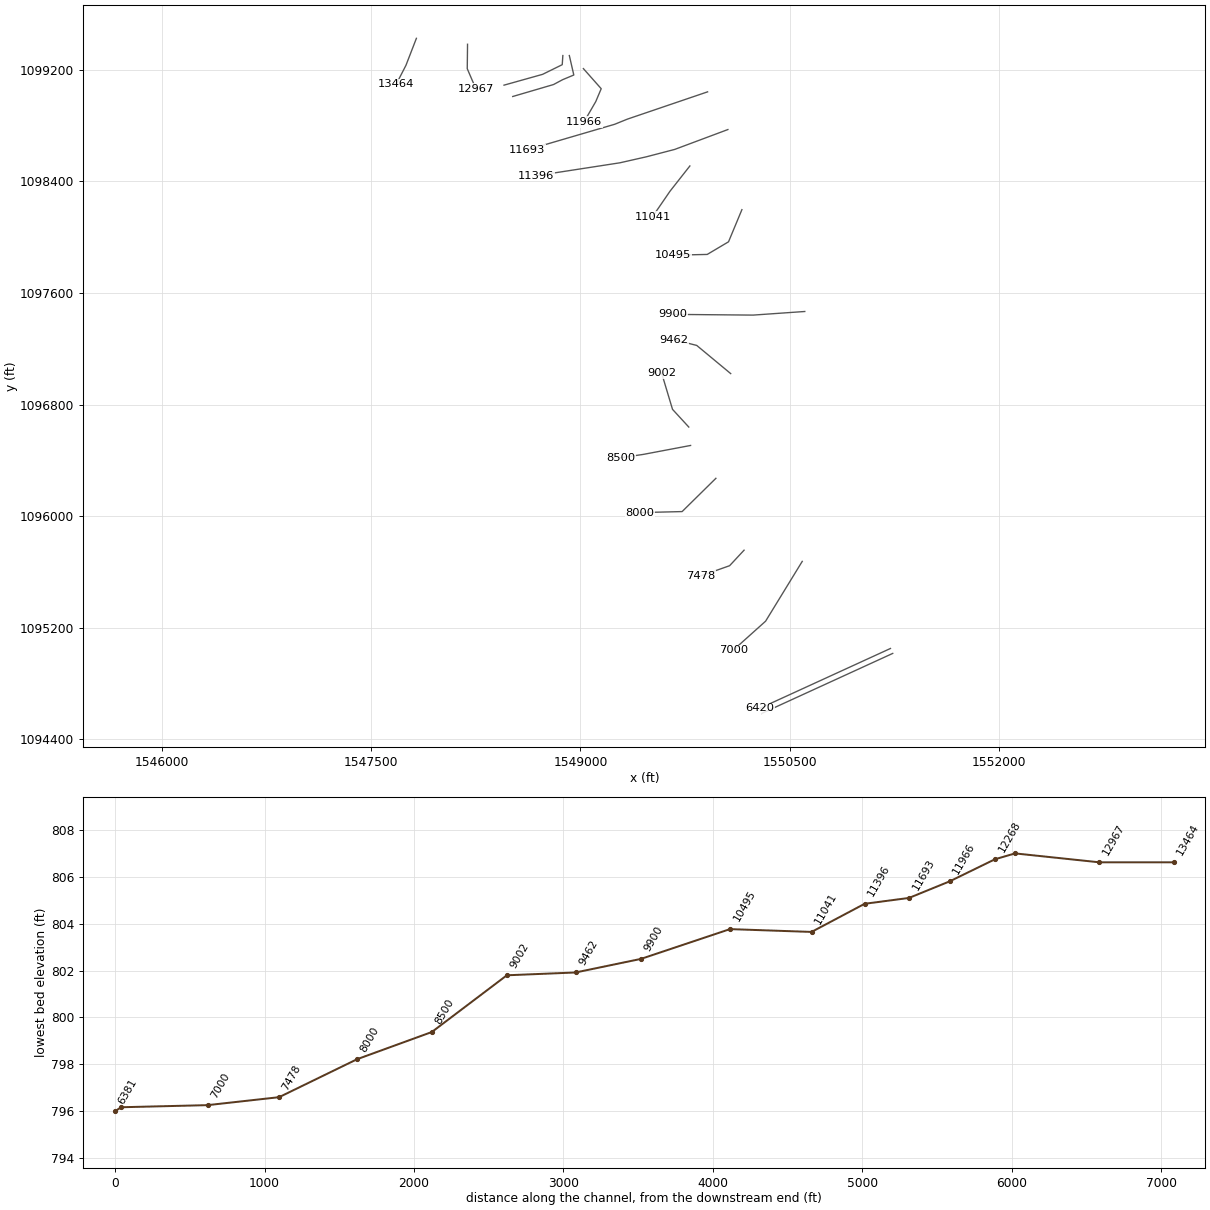
HEC-RAS study GeorgesCreek.prj: Georges Creek Limited Detail Study

--- GeorgesCreek.g06 (geometry) --- (continued)

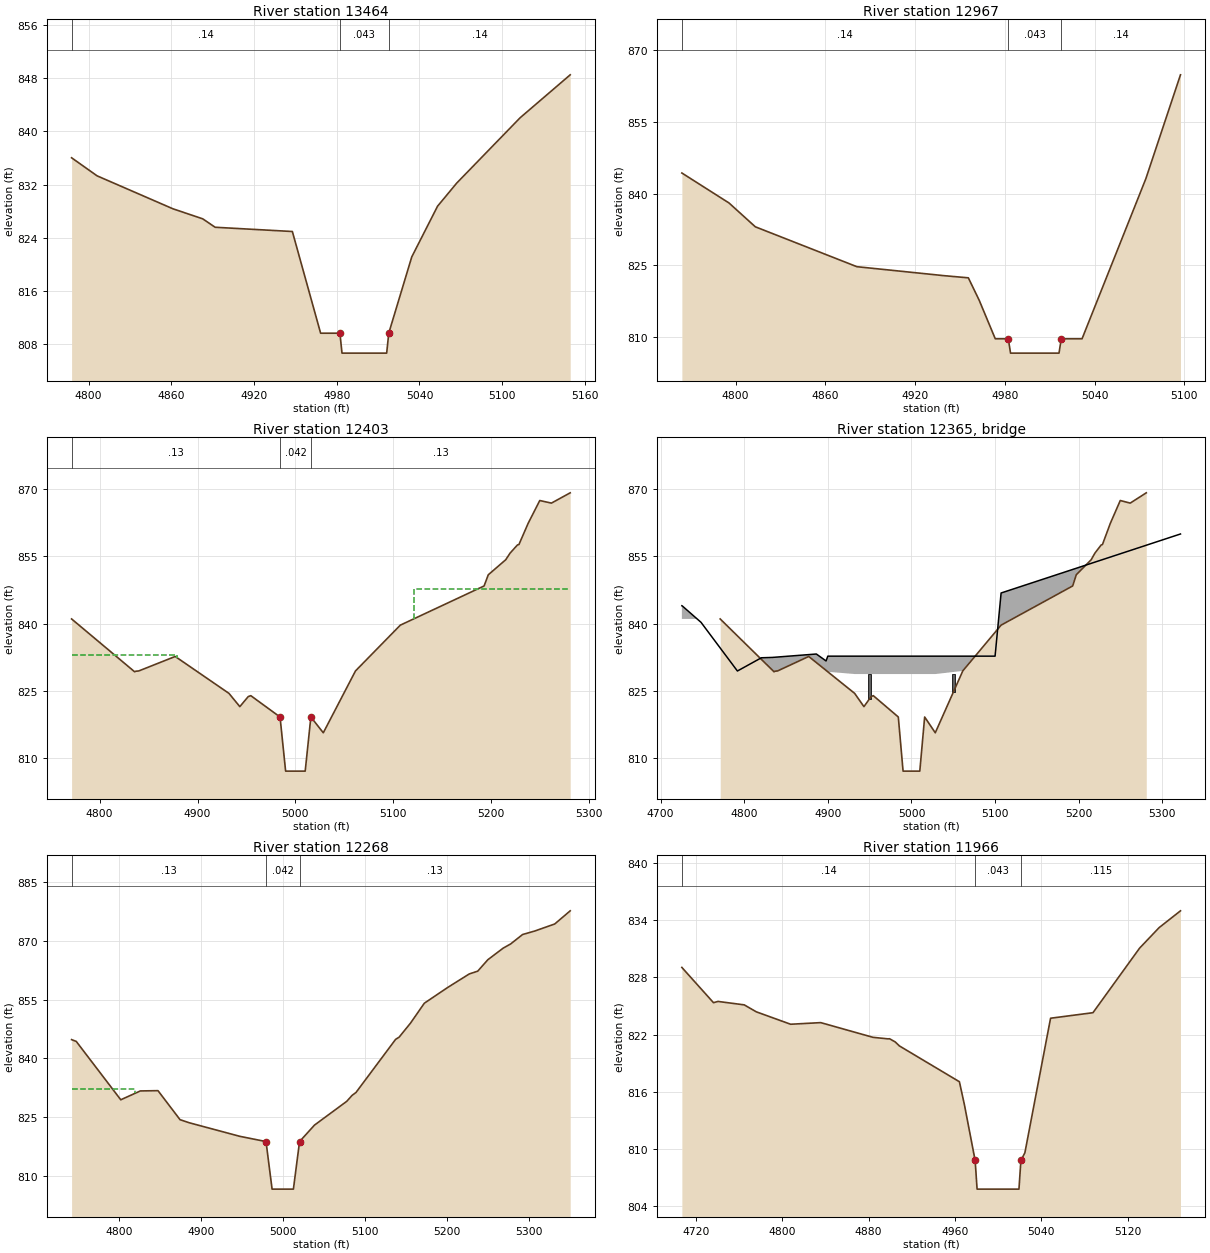
Type RM Length L Ch R = 1 ,13464   ,497,497,497
BEGIN DESCRIPTION:
Georges Creek 27.0
END DESCRIPTION:
XS GIS Cut Line= 3
        1547825.        1099425.       1547750.1      1099231.41
      1547679.59      1099094.41
#Sta/Elev= 16
  4787.7  836.03  4806.2  833.31  4861.2  828.35  4882.8  826.84  4891.8  825.57
  4947.8  824.93  4968.3  809.62  4982.3  809.62  4983.8  806.62  5016.2  806.62
  5017.7  809.62  5034.4  821.11  5053.1  828.74    5067  832.22    5113  842.06
  5149.3  848.52
#Mann= 3 ,-1,0
  4787.7     .14       0  4982.3    .043       0  5017.7     .14       0
Bank Sta=4982.3,5017.7
XS Rating Curve= 0 ,0
Exp/Cntr=0.3,0.1

Type RM Length L Ch R = 1 ,12967   ,564,564,564
BEGIN DESCRIPTION:
Georges Creek 26.0
END DESCRIPTION:
XS GIS Cut Line= 4
      1548191.32      1099382.51       1548189.3      1099207.23
      1548213.48      1099150.82      1548251.76      1099062.17
#Sta/Elev= 15
  4764.1  844.32  4795.6  838.05  4813.2  833.06  4881.1  824.71  4939.4  822.83
  4955.6  822.38  4962.8  817.72  4973.6  809.62  4982.3  809.62  4983.8  806.62
  5016.2  806.62  5017.7  809.62  5031.6  809.62  5074.3  843.17  5097.4  864.87
#Mann= 3 ,-1,0
  4764.1     .14       0  4982.3    .043       0  5017.7     .14       0
Bank Sta=4982.3,5017.7
XS Rating Curve= 0 ,0
Exp/Cntr=0.5,0.3

Type RM Length L Ch R = 1 ,12403   ,135,135,135
BEGIN DESCRIPTION:
Georges Creek 25.0
END DESCRIPTION:
XS GIS Cut Line= 4
      1548874.08      1099301.55      1548869.72      1099236.16
      1548729.24      1099166.94      1548452.64      1099089.38
#Sta/Elev= 26
  4771.3  841.02  4835.7  829.21  4836.9  829.33  4839.9  829.39  4877.2  832.63
  4932.1  824.38  4943.2  821.42  4951.8  823.66  4954.4  823.87  4984.3   819.1
    4990     807    5010     807  5015.8   819.1  5028.5  815.57  5061.4   829.4
  5107.2  839.63  5192.8  848.39  5197.1  850.89  5214.9  854.25  5219.4  855.74
  5226.9  857.56  5228.4  857.65  5237.8  862.38  5249.7  867.49  5261.6  866.91
  5280.8  869.21
#Mann= 3 ,-1,0
  4771.3     .13       0  4984.3    .042       0  5015.8     .13       0
#XS Ineff= 2 , 0
            4879  833.07    5121          847.67
Permanent Ineff=
       F       F
Bank Sta=4984.3,5015.8
XS Rating Curve= 0 ,0
Exp/Cntr=0.5,0.3

Type RM Length L Ch R = 3 ,12365   ,,,
BEGIN DESCRIPTION:
Latham Rd. (Georges Cr.) - TOR
Structure ID: LDS_GC_06
Approximate Survey Structure
END DESCRIPTION:
Bridge Culvert--1,0,-1,-1, 0
Deck Dist Width WeirC Skew NumUp NumDn MinLoCord MaxHiCord MaxSubmerge Is_Ogee
21,34,3,0, 14, 14, , , , 0, 1,1,,
  4725.5  4725.9  4748.4  4791.9  4820.6  4833.9  4886.3  4897.9    4900    4900
    5100    5100  5107.2  5321.7
  843.97  843.94  840.26  829.38  832.34  832.42  833.18  831.63   832.7   832.7
   832.7   832.7  846.82  860.01
     787     787     787     787     787     787     787     787     787   828.7
   828.7     787     787     787
  4725.5  4725.9  4748.4  4791.9  4820.6  4833.9  4886.3  4897.9    4900    4900
    5100    5100  5107.2  5321.7
  843.97  843.94  840.26  829.38  832.34  832.42  833.18  831.63   832.7   832.7
   832.7   832.7  846.82  860.01
     787     787     787     787     787     787     787     787     787   828.7
   828.7     787     787     787
Pier Skew, UpSta & Num, DnSta & Num=  ,4950, 2 ,4950, 2 , 0 , 0 , 0 ,0,0
       4       4
  823.19   828.7
       4       4
  817.34   828.7
Pier Skew, UpSta & Num, DnSta & Num=  ,5050, 2 ,5050, 2 , 0 , 0 , 0 ,0,0
       4       4
  824.61   828.7
       4       4
  824.69   828.7
Abutment Skew #Up #Dn= , 2 , 2
    4900    4910
   828.7   827.7
    4900    4910
   828.7  822.29
Abutment Skew #Up #Dn= , 2 , 2
    5090    5100
  839.88   828.7
    5090    5100
  831.64   828.7
BR Coef=-1 ,-1 , 0 ,1.25, 0 ,,,0.8,0,2,0,
WSPro=,,,, 1 ,,,, 0 ,,,, 0 ,,,,-1 ,-1 ,-1 , 0 , 0 , 0 , 0 , 0
BC Design=,, 0 ,, 0 ,,,,,,
BC HTab HWMax=869.21
BC Use User HTab Curves=0
BC User HTab FreeFlow(D)= 0

Type RM Length L Ch R = 1 ,12268   ,302,302,302
BEGIN DESCRIPTION:
Georges Creek 24.5
END DESCRIPTION:
XS GIS Cut Line= 5
      1548920.58      1099301.55      1548952.55      1099162.04
      1548872.62      1099128.62      1548807.23      1099093.74
      1548515.13        1099008.
#Sta/Elev= 30
  4742.4   844.8  4748.1  844.34  4802.4  829.49  4826.3  831.74  4847.8  831.81
  4874.7  824.43  4885.6  823.66  4947.6  820.19  4979.6  818.85    4987  806.75
    5013  806.75  5020.5  818.85  5038.7  823.04  5078.1   829.1  5084.5  830.59
  5089.4  831.36  5137.7  844.87    5142  845.43  5155.9  849.01  5172.7  854.06
  5201.2  858.07  5227.5  861.51  5237.9  862.23  5250.2  865.13  5268.9  868.08
  5278.1  869.16  5292.6  871.55  5307.6  872.45  5331.8  874.23  5350.7  877.58
#Mann= 3 ,-1,0
  4742.4     .13       0  4979.6    .042       0  5020.5     .13       0
#XS Ineff= 2 , 0
            4820  832.28    5180           851.3
Permanent Ineff=
       F       F
Bank Sta=4979.6,5020.5
XS Rating Curve= 0 ,0
Exp/Cntr=0.5,0.3

Type RM Length L Ch R = 1 ,11966   ,273,273,273
BEGIN DESCRIPTION:
Georges Creek 24.0
END DESCRIPTION:
XS GIS Cut Line= 4
      1549021.24      1099207.96      1549148.85      1099063.89
      1549109.74      1098971.28        1549025.        1098825.
#Sta/Elev= 24
    4707  829.03  4736.3  825.34  4740.5  825.47  4764.8  825.11    4776  824.38
  4807.8  823.08  4835.7  823.25  4884.1  821.71    4898  821.55  4899.5  821.56
  4904.7  821.23  4908.6  820.81  4964.2  817.06  4968.8  814.68  4978.8  808.81
  4980.6  805.81  5019.4  805.81  5021.2  808.81  5024.9  809.62  5048.7  823.71
    5088  824.29  5131.2  831.05  5149.3   833.2  5169.1  834.96
#Mann= 3 ,-1,0
    4707     .14       0  4978.8    .043       0  5021.2    .115       0
Bank Sta=4978.8,5021.2
XS Rating Curve= 0 ,0
Exp/Cntr=0.5,0.3

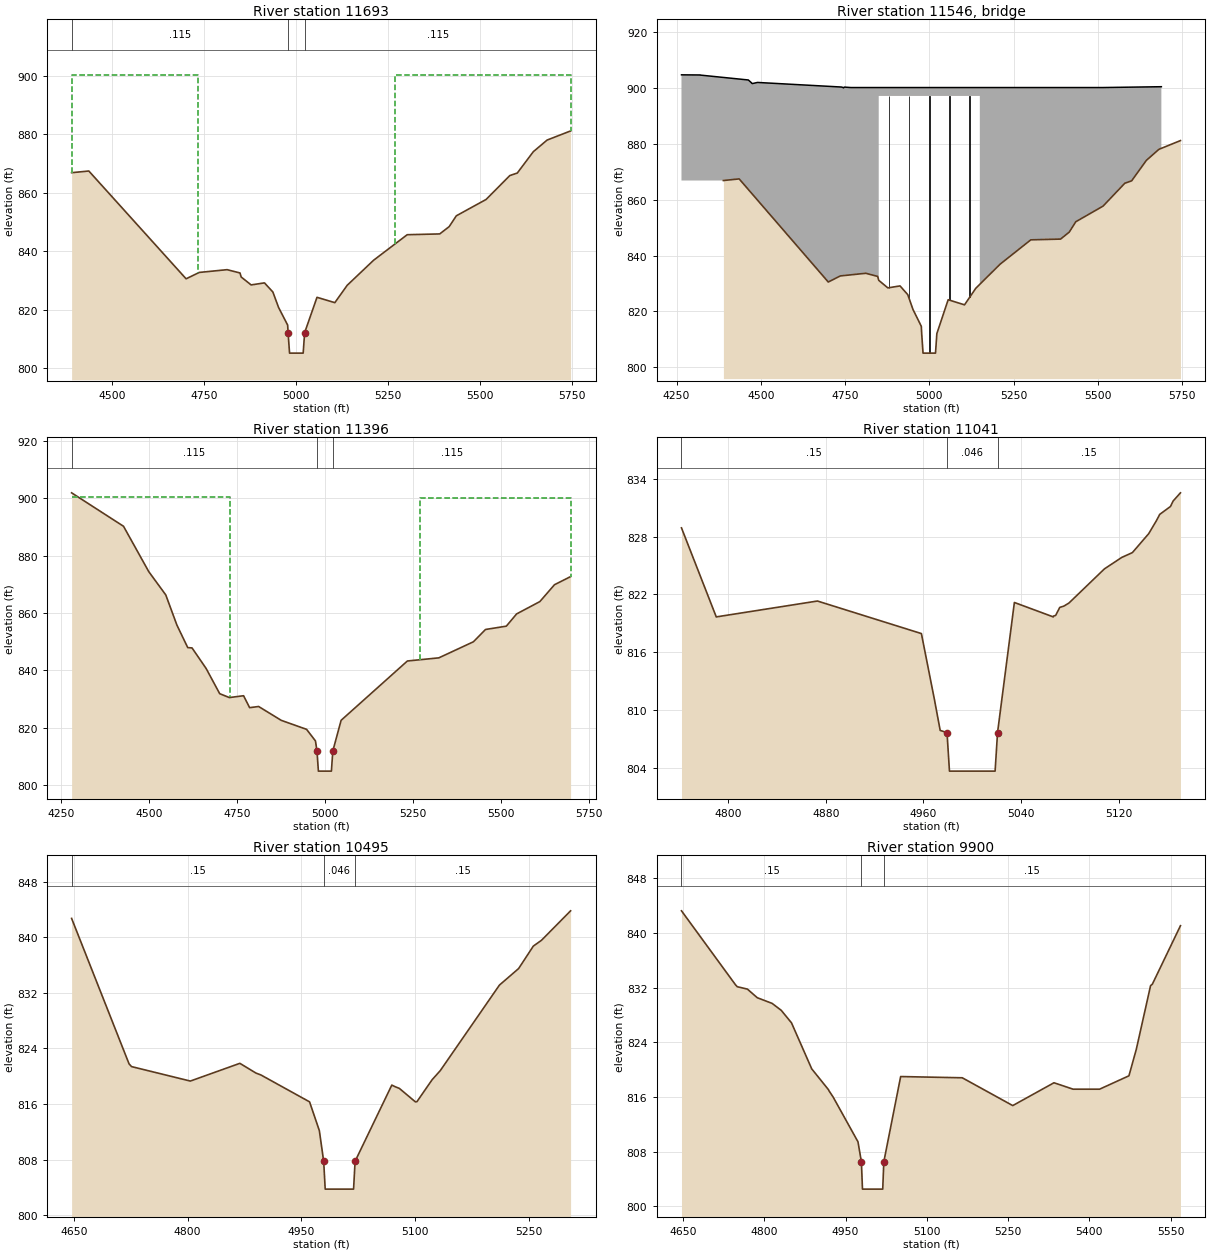
Type RM Length L Ch R = 1 ,11693   ,297,297,297
BEGIN DESCRIPTION:
Georges Creek 23.0
END DESCRIPTION:
XS GIS Cut Line= 4
      1549910.95      1099041.42      1549336.13      1098845.73
      1549245.38      1098808.91      1548620.49       1098625.8
#Sta/Elev= 30
  4389.1  866.84  4435.9  867.42  4700.3  830.53    4736  832.71  4811.7  833.66
  4846.8  832.53  4850.1  831.14  4877.1  828.44  4913.3  829.14  4936.2  826.01
  4951.7  820.71  4976.4  814.68  4977.5   812.1  4981.5   805.1  5018.5   805.1
  5022.5   812.1  5056.1   824.2  5104.6  822.37  5138.1   828.3    5210  836.89
  5301.3  845.62  5389.7  845.89  5415.4  848.39  5434.8  852.09  5515.8  857.69
  5580.2  865.86  5600.5  866.72  5644.1  874.03  5681.6  878.01  5745.4  881.13
#Mann= 3 ,-1,0
  4389.1    .115       0  4977.5     .04       0  5022.5    .115       0
#XS Ineff= 2 , 0
            4733  900.33    5267           900.1
Permanent Ineff=
       F       F
Bank Sta=4977.5,5022.5
XS Rating Curve= 0 ,0
Exp/Cntr=0.5,0.3

Type RM Length L Ch R = 3 ,11546   ,,,
BEGIN DESCRIPTION:
Southern Railway (Georges Cr.) - TOR
Structure ID: Southern Railway (Georges Cr.)
Approximate Survey Structure
END DESCRIPTION:
Bridge Culvert--1,0,-1,-1, 0
Deck Dist Width WeirC Skew NumUp NumDn MinLoCord MaxHiCord MaxSubmerge Is_Ogee
117,60,3,0, 29, 29, , , , 0, 1,1,,
  4264.7  4319.5    4320  4320.2  4320.3  4321.2    4463  4471.2    4472  4472.6
  4473.3    4475  4490.3  4738.7  4743.3  4743.9  4744.1  4744.4  4744.8  4745.2
  4745.5  4748.3  4767.5    4850    4850    5150    5150    5514  5688.7
  904.65   904.6  904.62  904.61  904.59  904.55  902.81  901.93  901.89   901.7
  901.64  901.52  901.93  900.29  900.16  900.07  900.07  900.06  900.02  900.04
  900.01  900.26   900.1   900.1   900.1   900.1   900.1   900.1   900.4
   785.1   785.1   785.1   785.1   785.1   785.1   785.1   785.1   785.1   785.1
   785.1   785.1   785.1   785.1   785.1   785.1   785.1   785.1   785.1   785.1
   785.1   785.1   785.1   785.1   897.1   897.1   785.1   785.1   785.1
  4264.7  4319.5    4320  4320.2  4320.3  4321.2    4463  4471.2    4472  4472.6
  4473.3    4475  4490.3  4738.7  4743.3  4743.9  4744.1  4744.4  4744.8  4745.2
  4745.5  4748.3  4767.5    4850    4850    5150    5150    5514  5688.7
  904.65   904.6  904.62  904.61  904.59  904.55  902.81  901.93  901.89   901.7
  901.64  901.52  901.93  900.29  900.16  900.07  900.07  900.06  900.02  900.04
  900.01  900.26   900.1   900.1   900.1   900.1   900.1   900.1   900.4
   785.1   785.1   785.1   785.1   785.1   785.1   785.1   785.1   785.1   785.1
   785.1   785.1   785.1   785.1   785.1   785.1   785.1   785.1   785.1   785.1
   785.1   785.1   785.1   785.1   897.1   897.1   785.1   785.1   785.1
Pier Skew, UpSta & Num, DnSta & Num=  ,4880, 2 ,4880, 2 , 0 , 0 , 0 ,0,0
       2       2
  828.37   897.1
       2       2
  822.48   897.1
Pier Skew, UpSta & Num, DnSta & Num=  ,4940, 2 ,4940, 2 , 0 , 0 , 0 ,0,0
       2       2
  824.71   897.1
       2       2
   819.7   897.1
Pier Skew, UpSta & Num, DnSta & Num=  ,5000, 2 ,5000, 2 , 0 , 0 , 0 ,0,0
       2       2
   805.1   897.1
       2       2
  804.85   897.1
Pier Skew, UpSta & Num, DnSta & Num=  ,5060, 2 ,5060, 2 , 0 , 0 , 0 ,0,0
       2       2
  824.01   897.1
       2       2
  824.19   897.1
Pier Skew, UpSta & Num, DnSta & Num=  ,5120, 2 ,5120, 2 , 0 , 0 , 0 ,0,0
       2       2
  825.17   897.1
       2       2
  830.97   897.1
Abutment Skew #Up #Dn= , 2 , 2
    4850    4900
   897.1  828.21
    4850    4900
   897.1   822.2
Abutment Skew #Up #Dn= , 2 , 2
    5100    5150
  822.45   897.1
    5100    5150
  828.83   897.1
BR Coef=-1 ,-1 , 0 ,1.25, 0 ,,,0.8,0,2,0,
WSPro=,,,, 1 ,,,, 0 ,,,, 0 ,,,,-1 ,-1 ,-1 , 0 , 0 , 0 , 0 , 0
BC Design=,, 0 ,, 0 ,,,,,,
BC HTab HWMax=881.13
BC Use User HTab Curves=0
BC User HTab FreeFlow(D)= 0

Type RM Length L Ch R = 1 ,11396   ,355,355,355
BEGIN DESCRIPTION:
Georges Creek 22.5
END DESCRIPTION:
XS GIS Cut Line= 5
      1550056.27      1098771.12      1549675.53      1098628.71
      1549474.02      1098576.13      1549283.16       1098532.8
      1548681.53      1098439.79
#Sta/Elev= 30
  4279.6  901.91  4427.2  890.25  4499.1  874.41  4547.5  866.29    4579  855.81
  4609.9  847.93  4622.1  847.82  4662.3  840.63  4700.8  831.86  4728.2  830.51
  4768.7  831.14  4785.9  826.99  4811.5  827.39  4875.9  822.56  4947.9  819.42
  4973.2  815.38  4977.5  811.85  4981.5  804.85  5018.5  804.85  5022.5  811.85
  5046.1  822.57  5234.6  843.26  5324.2  844.36  5422.5  849.97  5456.8  854.25
    5516  855.41  5545.3  859.68  5611.4  863.98    5653  869.86  5698.8  872.69
#Mann= 3 ,-1,0
  4279.6    .115       0  4977.5     .04       0  5022.5    .115       0
#XS Ineff= 2 , 0
            4730  900.35    5270           900.1
Permanent Ineff=
       F       F
Bank Sta=4977.5,5022.5
XS Rating Curve= 0 ,0
Exp/Cntr=0.5,0.3

Type RM Length L Ch R = 1 ,11041   ,546,546,546
BEGIN DESCRIPTION:
Georges Creek 22.0
END DESCRIPTION:
XS GIS Cut Line= 3
      1549783.95      1098510.01      1549641.57       1098328.8
      1549517.32       1098147.6
#Sta/Elev= 26
  4761.7  828.92  4790.2  819.67  4873.1  821.32  4958.3  817.94  4969.1  811.01
  4973.7  807.88  4979.3  807.65  4981.3  803.65  5018.7  803.65  5020.7  807.65
  5034.5  821.17  5066.4  819.67  5066.7  819.77  5068.3  819.82  5071.7  820.66
    5075  820.79  5079.2  821.11  5108.3  824.66  5122.5  825.85  5131.2  826.35
  5144.6  828.32  5150.9  829.67  5153.6  830.32  5162.4  831.14  5164.6  831.71
  5170.6  832.56
#Mann= 3 ,-1,0
  4761.7     .15       0  4979.3    .046       0  5020.7     .15       0
Bank Sta=4979.3,5020.7
XS Rating Curve= 0 ,0
Exp/Cntr=0.3,0.1

Type RM Length L Ch R = 1 ,10495   ,595,595,595
BEGIN DESCRIPTION:
Georges Creek 21.0
END DESCRIPTION:
XS GIS Cut Line= 4
      1550156.71      1098196.78      1550060.93       1097966.4
       1549908.2       1097875.8      1549664.87      1097870.62
#Sta/Elev= 25
    4647   842.7  4722.7  821.79    4726  821.39  4803.5  819.31  4868.8  821.86
    4890  820.46  4896.5  820.19  4960.7  816.32  4973.6  812.18  4979.3  807.77
  4981.3  803.77  5018.7  803.77  5020.7  807.77  5069.1  818.73  5074.1  818.47
    5079  818.26  5100.2  816.32  5102.2  816.34  5122.3  819.51    5133  820.81
    5211  833.11  5236.3  835.49  5255.7  838.72  5266.5  839.56  5304.8  843.79
#Mann= 3 ,-1,0
    4647     .15       0  4979.3    .046       0  5020.7     .15       0
Bank Sta=4979.3,5020.7
XS Rating Curve= 0 ,0
Exp/Cntr=0.3,0.1

Type RM Length L Ch R = 1 ,9900    ,438,438,438
BEGIN DESCRIPTION:
Georges Creek 20.0
END DESCRIPTION:
XS GIS Cut Line= 3
      1550607.12       1097466.8      1550236.95      1097440.91
      1549662.28      1097446.09
#Sta/Elev= 29
  4647.2  843.24  4747.2  832.38  4750.2  832.13  4768.9  831.78  4787.1  830.52
  4814.5  829.69  4831.4  828.67  4850.3  826.84  4887.6  820.11  4918.7  817.04
    4919  816.98  4919.3  816.92    4927     816    4973  809.43  4979.3   806.5
  4981.3   802.5  5018.7   802.5  5020.7   806.5  5051.8  818.98  5165.5   818.8
  5258.7  814.73  5334.8  818.07  5370.2  817.13    5419  817.13  5473.2  819.09
  5486.8  822.97  5513.1  832.28  5516.4   832.5  5568.3  841.06
#Mann= 3 ,-1,0
  4647.2     .15       0  4979.3    .046       0  5020.7     .15       0
Bank Sta=4979.3,5020.7
XS Rating Curve= 0 ,0
Exp/Cntr=0.3,0.1

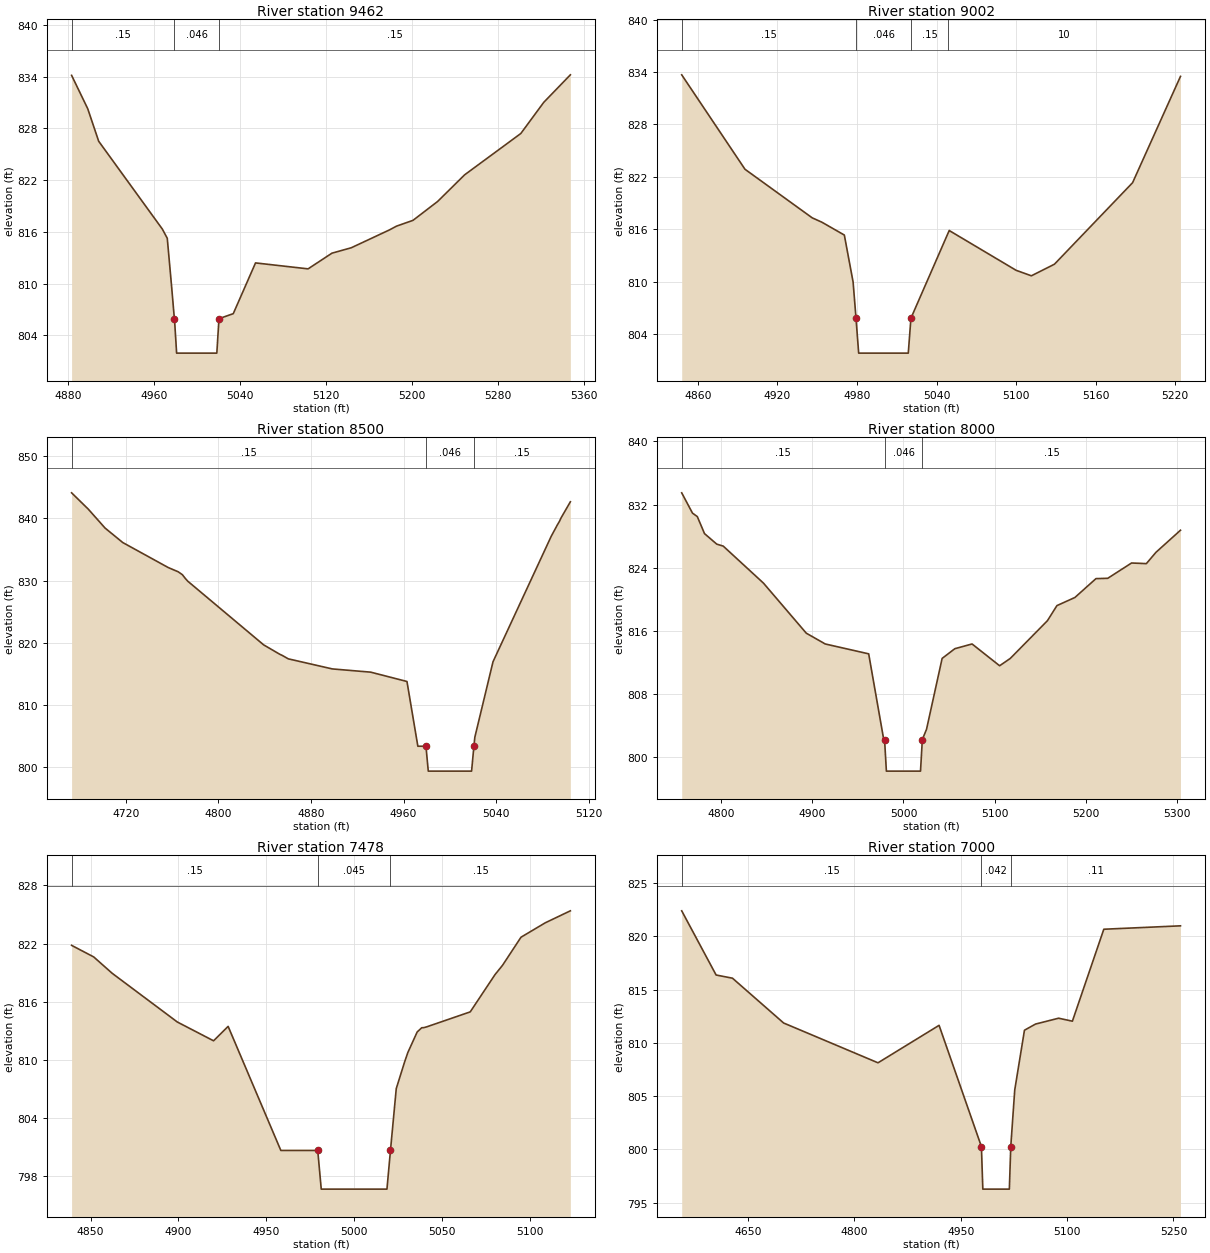
Type RM Length L Ch R = 1 ,9462    ,460,460,460
BEGIN DESCRIPTION:
Georges Creek 19.0
END DESCRIPTION:
XS GIS Cut Line= 3
      1550076.46      1097021.56      1549833.13      1097223.47
      1549670.05      1097264.89
#Sta/Elev= 24
  4883.6  834.16  4898.6  830.29  4908.8  826.51    4968  816.32  4972.6  815.25
  4976.7  809.56  4979.2  805.92  4979.3  805.92  4981.3  801.92  5018.7  801.92
  5020.7  805.92    5034   806.5  5054.7  812.39  5103.6   811.7  5125.8  813.52
  5143.8  814.15  5179.3  816.22  5185.9  816.66  5201.2  817.33  5224.1  819.52
  5249.2  822.61  5301.5  827.41  5322.8  831.02  5347.6  834.22
#Mann= 3 ,-1,0
  4883.6     .15       0  4979.3    .046       0  5020.7     .15       0
Bank Sta=4979.3,5020.7
XS Rating Curve= 0 ,0
Exp/Cntr=0.3,0.1

Type RM Length L Ch R = 1 ,9002    ,502,502,502
BEGIN DESCRIPTION:
Georges Creek 18.0
END DESCRIPTION:
XS GIS Cut Line= 3
      1549776.18      1096638.44      1549659.69      1096765.28
      1549582.04      1097024.15
#Sta/Elev= 18
  4847.9  833.69  4895.6  822.87  4946.3   817.3  4953.6   816.8  4970.5  815.33
  4977.1  809.95  4979.3   805.8  4981.3   801.8  5018.7   801.8  5020.7   805.8
  5048.9  815.62  5049.6  815.86  5050.1   815.8    5100  811.29  5111.5  810.66
  5128.9  811.99  5187.8  821.33  5223.9  833.51
#Mann= 4 ,-1,0
  4847.9     .15       0  4979.3    .046       0  5020.7     .15       0
  5048.9      10       0
Bank Sta=4979.3,5020.7
XS Rating Curve= 0 ,0
Exp/Cntr=0.3,0.1

Type RM Length L Ch R = 1 ,8500    ,500,500,500
BEGIN DESCRIPTION:
Georges Creek 17.0
END DESCRIPTION:
XS GIS Cut Line= 3
      1549789.12      1096506.42      1549449.96      1096442.21
      1549286.93      1096418.41
#Sta/Elev= 28
  4673.3  844.09  4687.7  841.47  4702.2  838.43  4717.5   836.1  4756.6   832.1
  4765.4   831.4    4769  830.93  4771.6  830.31  4773.7  829.88  4839.1  819.67
  4853.2  818.14    4855  817.99  4860.4  817.42  4898.4   815.8  4931.6  815.28
  4962.9  813.78  4972.3  803.38  4979.3  803.38  4981.3  799.38  5018.7  799.38
  5020.7  803.38  5021.5  804.82  5037.2  816.95  5087.5  837.12  5092.8  838.95
  5094.6  839.51  5095.9  840.04    5104  842.65
#Mann= 3 ,-1,0
  4673.3     .15       0  4979.3    .046       0  5020.7     .15       0
Bank Sta=4979.3,5020.7
XS Rating Curve= 0 ,0
Exp/Cntr=0.3,0.1

Type RM Length L Ch R = 1 ,8000    ,522,522,522
BEGIN DESCRIPTION:
Georges Creek 16.0
END DESCRIPTION:
XS GIS Cut Line= 3
      1549970.33      1096270.86      1549728.48      1096032.43
        1549425.        1096025.
#Sta/Elev= 30
    4757  833.48  4768.8  830.91  4774.1  830.47    4782  828.31  4795.4  826.98
  4802.5  826.73  4846.6  822.04  4893.5   815.7  4914.3  814.33  4961.9  813.08
  4978.4  802.22  4979.3  802.22  4981.3  798.22  5018.7  798.22  5020.7  802.22
  5025.3  803.52  5042.4   812.5  5056.3  813.73  5075.2  814.33  5105.4  811.57
  5117.1   812.5  5157.8  817.28  5168.2  819.19  5187.9  820.22    5211  822.61
  5223.9  822.65    5250  824.59  5266.2  824.51  5276.8  825.95  5303.6  828.74
#Mann= 3 ,-1,0
    4757     .15       0  4979.3    .046       0  5020.7     .15       0
Bank Sta=4979.3,5020.7
XS Rating Curve= 0 ,0
Exp/Cntr=0.3,0.1

Type RM Length L Ch R = 1 ,7478    ,478,478,478
BEGIN DESCRIPTION:
Georges Creek 15.0
END DESCRIPTION:
XS GIS Cut Line= 3
      1550172.24      1095755.73      1550068.69      1095644.42
      1549864.19      1095571.94
#Sta/Elev= 24
  4839.2  821.81  4851.8  820.61  4862.3  818.92  4899.4  813.88    4920  811.94
  4928.3  813.43  4958.3   800.6  4979.3   800.6  4981.3   796.6  5018.7   796.6
  5020.7   800.6    5024     807  5028.8  809.78  5030.6  810.73  5035.9  812.85
  5038.5  813.29  5039.7   813.3  5041.3  813.38  5066.1  814.93  5080.2  818.78
  5084.5  819.75    5095  822.65  5108.8  824.14  5123.1  825.38
#Mann= 3 ,-1,0
  4839.2     .15       0  4979.3    .045       0  5020.7     .15       0
Bank Sta=4979.3,5020.7
XS Rating Curve= 0 ,0
Exp/Cntr=0.3,0.1

Type RM Length L Ch R = 1 ,7000    ,580,580,580
BEGIN DESCRIPTION:
Georges Creek 14.0
END DESCRIPTION:
XS GIS Cut Line= 3
        1550589.      1095675.48      1550326.46      1095246.59
      1550094.58      1095038.68
#Sta/Elev= 17
  4556.7  822.41  4605.2  816.38  4628.3  816.08  4700.4  811.87  4833.5  808.13
  4919.6  811.65  4979.3  800.26  4981.3  796.26  5018.7  796.26  5020.7  800.26
  5026.3  805.58    5040  811.19  5055.6  811.77  5088.2  812.32  5107.6  812.04
  5151.9  820.68    5260     821
#Mann= 3 ,-1,0
  4556.7     .15       0  4979.3    .042       0  5020.7     .11       0
Bank Sta=4979.3,5020.7
XS Rating Curve= 0 ,0
Exp/Cntr=0.5,0.3

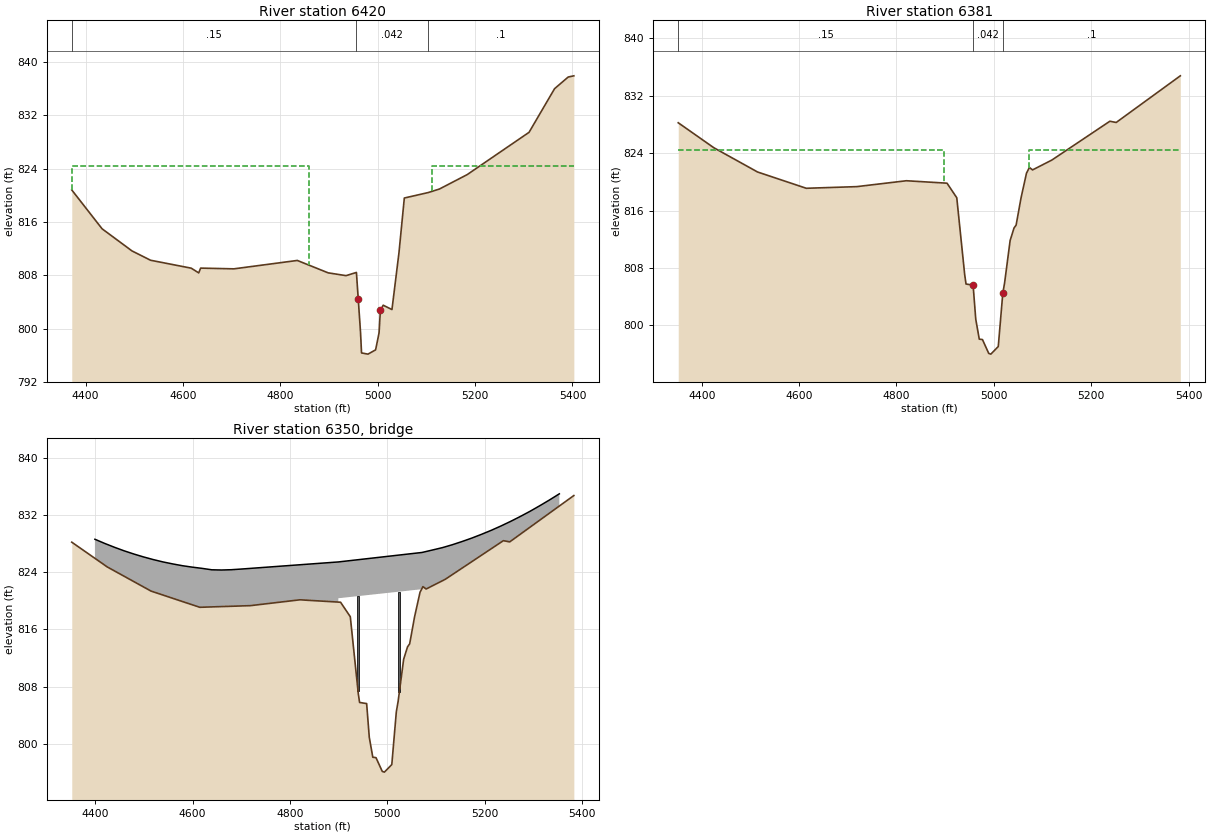
Type RM Length L Ch R = 1 ,6420    ,39,39,39
BEGIN DESCRIPTION:
Georges Creek 13.0
END DESCRIPTION:
XS GIS Cut Line= 2
    1551220.9265    1095051.0574    1550283.4392    1094621.2055
#Sta/Elev= 30
  4371.5  820.81  4433.8  814.98  4495.2  811.66  4533.4  810.26  4616.9  809.07
  4632.3  808.36  4636.2  809.08  4704.6  808.97  4834.8  810.23  4898.1  808.37
  4934.9  807.95  4956.2  808.43    4960 804.386  4964.6  799.49  4966.7  796.35
  4979.9  796.17  4995.6  796.81  5002.7  799.36  5005.4  802.75  5011.2  803.51
  5029.2  802.86  5043.6  811.39  5054.6   819.6  5103.7  820.42  5126.7  820.95
  5183.9  823.12  5310.8  829.46  5363.2  836.01  5391.2  837.76  5402.8  837.94
#Mann= 3 ,-1,0
  4371.5     .15       0  4956.2    .042       0  5103.7      .1       0
#XS Ineff= 2 , 0
       0  4859.3  824.38  5111.3       0  824.38
Permanent Ineff=
       F       F
Bank Sta=4960,5005.4
XS Rating Curve= 0 ,0
Exp/Cntr=0.5,0.3

Type RM Length L Ch R = 1 ,6381    ,86,86,86
BEGIN DESCRIPTION:
Georges Creek 13.0
END DESCRIPTION:
XS GIS Cut Line= 4
    1551237.1813    1095015.6063    1551237.1813    1095015.6063
1550554.584369411094702.62543343     1550299.694    1094585.7544
#Sta/Elev= 30
 4351.75  828.24 4424.85  824.76 4514.65  821.38 4614.78  819.11  4718.6  819.34
 4820.41  820.16  4903.9  819.82 4923.91  817.79 4940.24  807.04 4942.95  805.77
 4957.47  805.61 4962.89  800.88 4970.11  798.09 4976.65  798.03 4989.56   796.1
 4993.89     796 5009.15  797.06 5018.42  804.45 5022.18  805.94 5033.51  811.83
 5041.54  813.58 5045.82  813.98 5055.89  817.76 5067.13  821.22 5073.13  822.01
  5079.6  821.67 5119.15  823.04 5238.34  828.45 5251.38  828.28 5383.09  834.78
#Mann= 3 ,-1,0
 4351.75     .15       0 4957.47    .042       0 5018.42      .1       0
#XS Ineff= 2 , 0
       0 4898.55  824.49 5072.55       0  824.49
Permanent Ineff=
       F       F
Bank Sta=4957.47,5018.42
XS Rating Curve= 0 ,0
Exp/Cntr=0.5,0.3

Type RM Length L Ch R = 3 ,6350    ,,,
BEGIN DESCRIPTION:
Old Easley Hwy. - TOR
Structure ID: LDS_GC_04
Approximate Survey Structure
END DESCRIPTION:
Bridge Culvert--1,0,-1,-1, 0
Deck Dist Width WeirC Skew NumUp NumDn MinLoCord MaxHiCord MaxSubmerge Is_Ogee
1,46.25,3,0, 43, 36, , , , 0, 1,1,,
  4399.3  4419.3  4439.3  4459.3  4479.3  4499.3  4519.3  4539.3  4559.3  4579.3
  4599.3  4619.3  4639.3  4659.3  4679.3  4699.3  4719.3  4739.3  4759.3  4779.3
  4799.3  4819.3  4839.3  4859.3  4879.3  4899.3  4899.3  5071.3  5071.3  5091.3
  5113.3  5133.3  5153.3  5173.3  5193.3  5213.3  5233.3  5253.3  5273.3  5293.3
  5313.3  5333.3  5353.3
  828.65  828.07  827.53  827.03  826.58  826.17   825.8  825.47  825.19  824.94
  824.74  824.57  824.37  824.34  824.38  824.47  824.57  824.67  824.77  824.87
  824.97  825.07  825.17  825.27  825.37  825.47  825.47   826.8   826.8  827.12
  827.48  827.88  828.33  828.81  829.34   829.9  830.51  831.16  831.85  832.58
  833.36  834.17  835.02
                                                                                
                                                                                
                                                  820.38  821.65
                                                                                
                        
  4412.2  4432.2  4452.2  4472.2  4492.2  4512.2  4532.2  4552.2  4572.2  4592.2
  4612.2  4632.2  4652.2  4672.2  4692.2  4712.2  4732.2  4752.2  4772.2  4792.2
  4812.2  4832.2  4852.2  4872.2  4892.2  4912.1  4912.1  5084.1  5084.1  5104.1
  5124.1  5144.1  5164.1  5184.1  5204.1  5224.1
  828.65  828.07  827.53  827.03  826.58  826.17   825.8  825.47  825.19  824.94
  824.74  824.57  824.37  824.34  824.38  824.47  824.57  824.67  824.77  824.87
  824.97  825.07  825.17  825.27  825.37  825.47  825.47   826.8   826.8  827.12
  827.48  827.88  828.33  828.81  829.34   829.9
                                                                                
                                                                                
                                                  820.38  821.65
                                                
Pier Skew, UpSta & Num, DnSta & Num=  ,4939.8, 2 ,4952.6, 2 , 0 , 0 , 0 ,,
       4       4
     800     824
       4       4
     800     824
Pier Skew, UpSta & Num, DnSta & Num=  ,5024.8, 2 ,5037.6, 2 , 0 , 0 , 0 ,,
       4       4
     800     824
       4       4
     800     824
Abutment Skew #Up #Dn= , 3 , 3
 4899.25 4901.25 4921.25
     817     817     807
  4912.1  4914.1  4934.1
     817     817     807
Abutment Skew #Up #Dn= , 3 , 3
  5049.3  5069.3  5071.3
  810.25  820.25  820.25
  5062.1  5082.1  5084.1
  810.25  820.25  820.25
BR Coef=-1 ,-1 , 0 ,1.25, 0 ,,,0.8,0,2,0,
WSPro=,,,, 1 ,,,, 0 ,,,, 0 ,,,,-1 ,-1 ,-1 , 0 , 0 , 0 , 0 , 0
BC Design=,, 0 ,, 0 ,,,,,,
BC HTab HWMax=843.14
BC Use User HTab Curves=0
BC User HTab FreeFlow(D)= 0