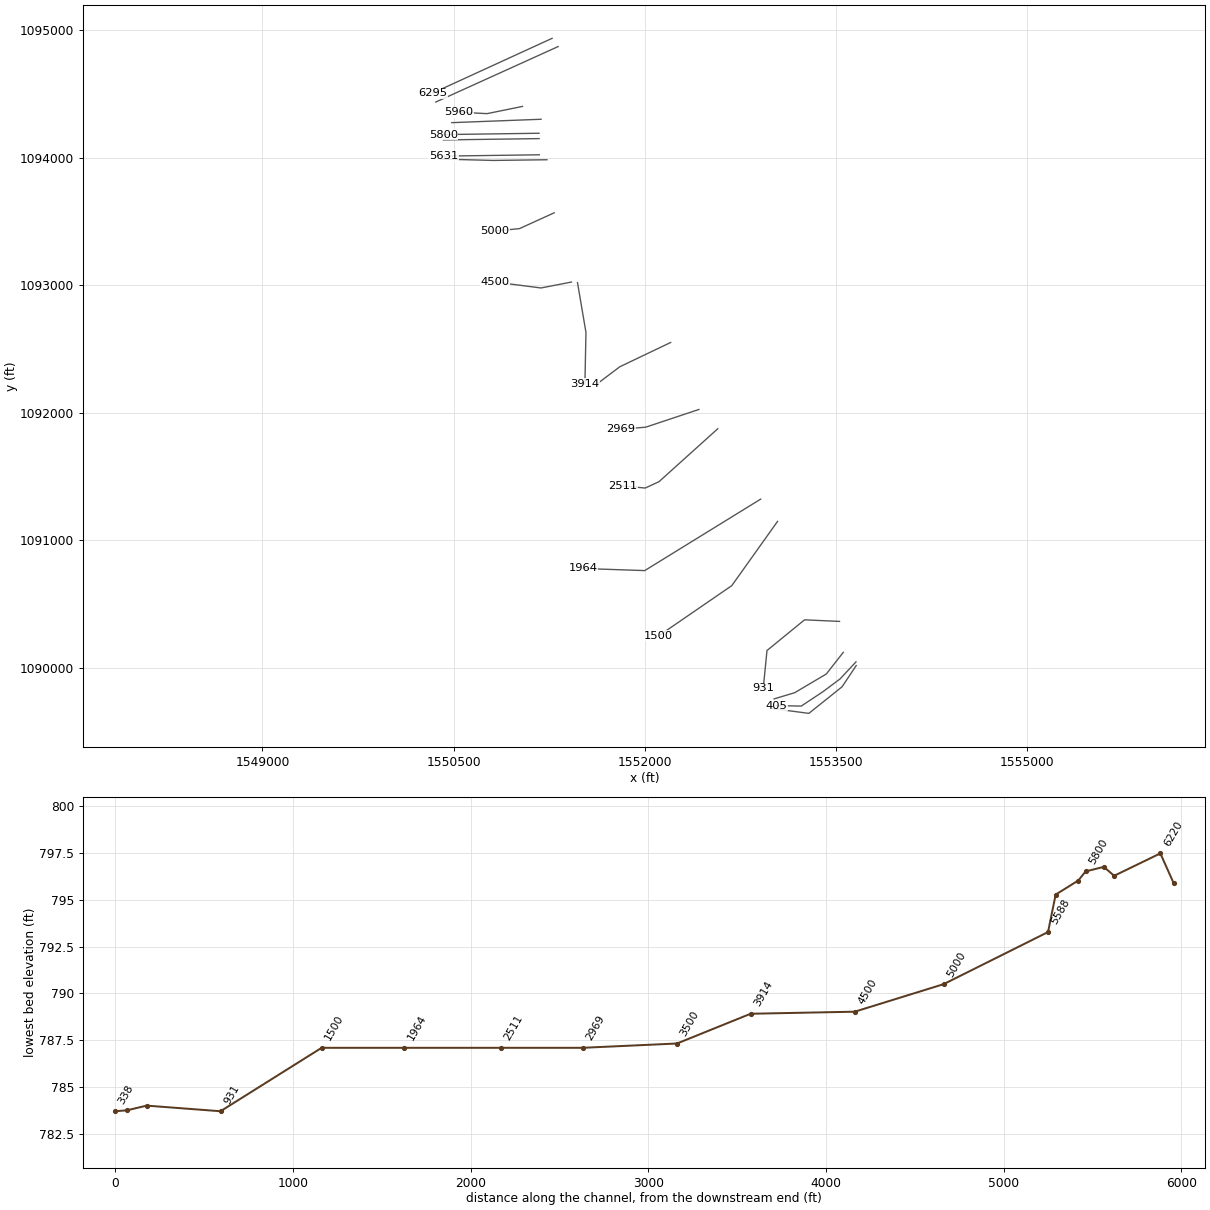
HEC-RAS study GeorgesCreek.prj: Georges Creek Limited Detail Study

--- GeorgesCreek.g06 (geometry) --- (continued)

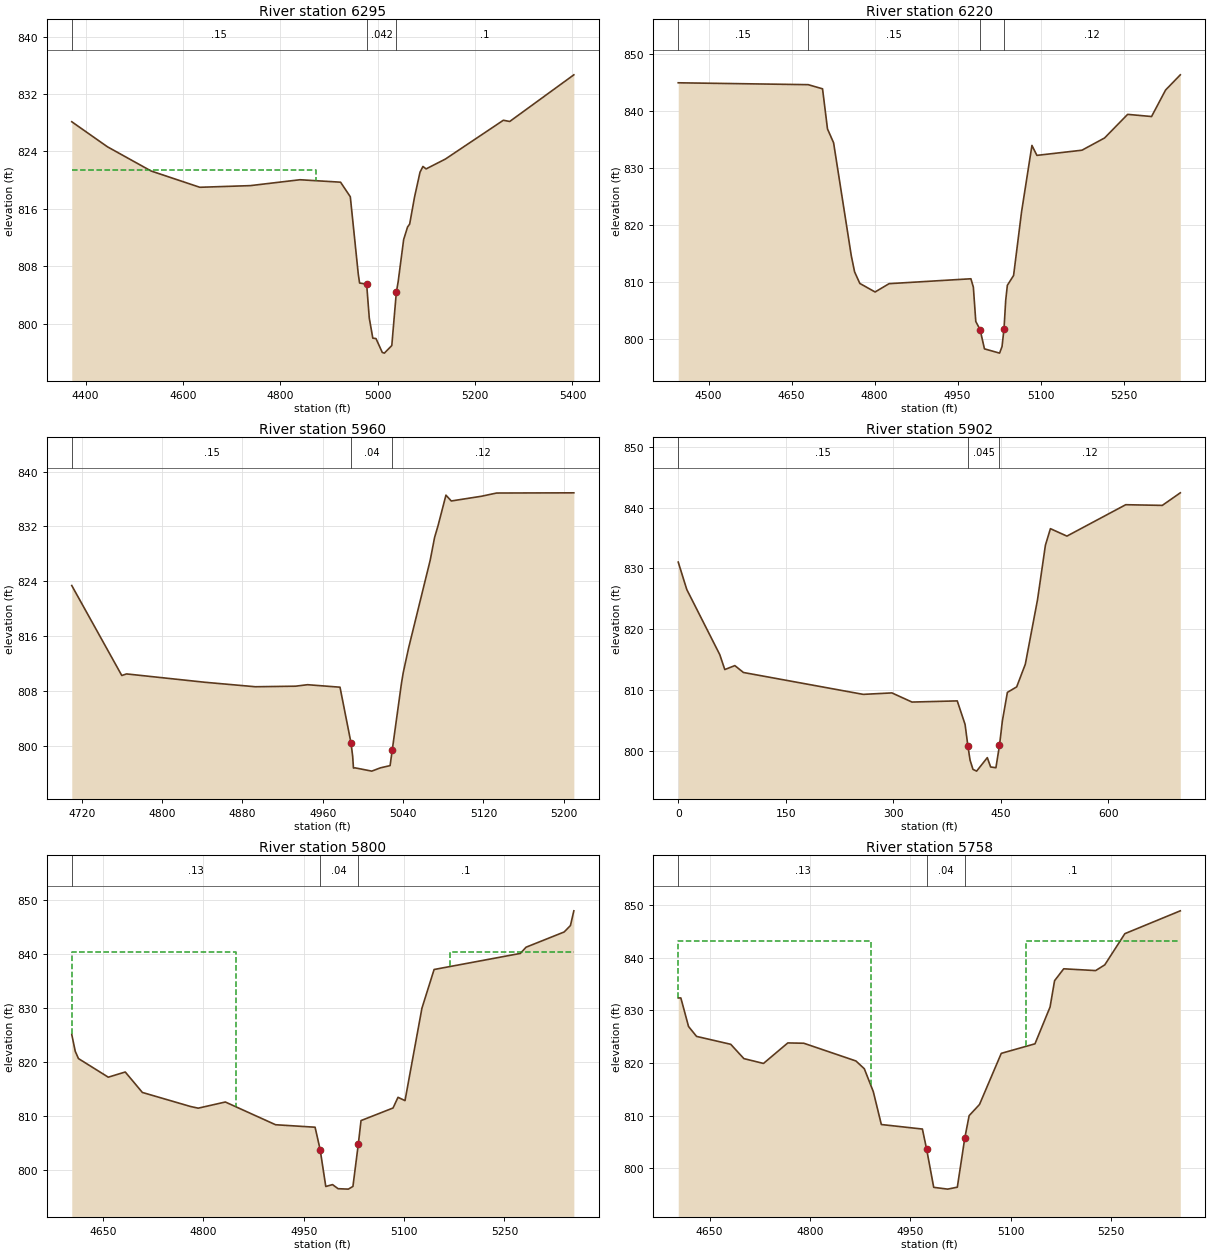
Type RM Length L Ch R = 1 ,6295    ,75,75,75
BEGIN DESCRIPTION:
Georges Creek 13.0
END DESCRIPTION:
XS GIS Cut Line= 2
    1551273.0254    1094937.4321     1550335.538    1094507.5802
#Sta/Elev= 30
  4371.5  828.13  4444.6  824.65  4534.4  821.27 4634.53     819 4738.35  819.23
 4840.16  820.05 4923.65  819.71 4943.66  817.68 4959.99  806.93  4962.7  805.66
 4977.22   805.5 4982.64  800.77 4989.86  797.98  4996.4  797.92 5009.31  795.99
 5013.64  795.89  5028.9  796.95 5038.17  804.34 5041.93  805.83 5053.26  811.72
 5061.29  813.47 5065.57  813.87 5075.64  817.65 5086.88  821.11 5092.88   821.9
 5099.35  821.56  5138.9  822.93 5258.09  828.34 5271.13  828.17 5402.84  834.67
#Mann= 3 ,-1,0
  4371.5     .15       0 4977.22    .042       0 5038.17      .1       0
#XS Ineff= 2 , 0
       0 4873.55   821.4 5132.85       0   821.4
Permanent Ineff=
       F       F
Bank Sta=4977.22,5038.17
XS Rating Curve= 0 ,0
Exp/Cntr=0.5,0.3

Type RM Length L Ch R = 1 ,6220    ,260,260,260
XS GIS Cut Line= 2
    1551320.6064    1094872.9437    1550360.5379    1094437.7468
#Sta/Elev= 30
    4445     845    4680  844.67 4705.89  843.94 4714.84  836.89 4725.87  834.46
 4757.87   814.6 4763.83  811.77 4773.32  809.73  4800.9  808.23 4826.28  809.69
 4974.12  810.55 4978.54  809.08 4982.95  803.04 4990.67  801.63 4998.62  798.23
 5025.98  797.48  5030.4  798.64 5033.98  801.76 5037.02  806.74    5040   809.4
 5051.29  811.13  5065.7  822.32 5084.46  833.99 5093.43  832.24 5174.93  833.15
 5215.76   835.3 5257.48  839.45 5300.72  839.07 5326.09  843.73  5352.7   846.4
#Mann= 4 ,-1,0
    4445     .15       0    4680     .15       0 4990.67    .045       0
 5033.98     .12       0
Bank Sta=4990.67,5033.98
XS Rating Curve= 0 ,0
Exp/Cntr(USF)=0,0
Exp/Cntr=0.5,0.3

Type RM Length L Ch R = 1 ,5960    ,58,58,58
BEGIN DESCRIPTION:
Georges Creek 12.0
END DESCRIPTION:
XS GIS Cut Line= 4
      1551040.87      1094403.23      1550762.74      1094346.52
      1550552.11      1094357.321550540.936689951094357.89290865
#Sta/Elev= 27
  4710.1  823.37  4759.9  810.24  4764.7  810.474842.529 809.2544892.841 808.599
4932.809 808.6794944.874 808.8964977.175 808.5334988.165 800.3794989.785 798.446
4990.566  796.734992.082 796.7645008.815 796.2845017.452 796.7655027.048 797.088
 5029.24 799.4165038.279 809.0145040.111 810.6495045.509 814.2795067.002  827.08
5071.343 830.384 5074.81 832.1195082.657 836.561 5087.96 835.7115117.904 836.397
5133.088  836.87    5210   836.9
#Mann= 3 ,-1,0
  4710.1     .15       04988.165     .04       0 5029.24     .12       0
Bank Sta=4988.165,5029.24
XS Rating Curve= 0 ,0
Exp/Cntr=0.5,0.3

Type RM Length L Ch R = 1 ,5902    ,102,102,102
XS GIS Cut Line= 2
1551186.417496921094302.36684743 1550486.40119381094275.80076382
#Sta/Elev= 30
       0  831.05   11.93  826.55   57.96  815.87   64.96  813.42   78.97  814.07
   90.98  812.94   258.1  809.35  298.13  809.59  326.15  808.09   389.3  808.28
  400.21  804.42  404.21  800.83  407.21  798.55  411.21  797.05   416.3  796.76
  431.23  798.97  435.89  797.44  443.24  797.32  448.24  800.99  452.24  804.99
  459.25  809.68  472.22  810.58  484.27   814.3  501.28  824.87  512.29  833.81
  519.29  836.53  542.31  835.31  624.37  840.46   675.4  840.35  700.52  842.41
#Mann= 3 ,-1,0
       0     .15       0  404.21    .045       0  448.24     .12       0
Bank Sta=404.21,448.24
XS Rating Curve= 0 ,0
Exp/Cntr(USF)=0,0
Exp/Cntr=0.5,0.3

Type RM Length L Ch R = 1 ,5800    ,42,42,42
BEGIN DESCRIPTION:
Georges Creek 11.5
END DESCRIPTION:
XS GIS Cut Line= 2
      1551170.49       1094192.6    1550419.6349    1094182.1911
#Sta/Elev= 30
    4603  825.18    4603  825.16  4608.2  822.06    4613  820.71  4657.6  817.26
    4683  818.22  4708.6  814.43  4780.6  811.83  4792.1  811.52  4832.7  812.66
  4907.8  808.45  4966.9  807.99  4974.5  803.83  4982.9  797.01    4993  797.36
  5001.3   796.6  5016.6  796.52  5023.5  797.02  5031.6   804.9  5035.6  809.22
  5083.5  811.55  5090.9  813.53  5101.4  812.92  5126.7  830.04  5144.9  837.21
  5273.9  840.19  5282.4  841.34  5339.4  844.16  5348.8  845.35  5353.9  848.08
#Mann= 3 ,-1,0
    4603     .13       0  4974.5     .04       0  5031.6      .1       0
#XS Ineff= 2 , 0
       0    4849  840.47    5169       0  840.47
Permanent Ineff=
       F       F
Bank Sta=4974.5,5031.6
XS Rating Curve= 0 ,0
Exp/Cntr=0.5,0.3

Type RM Length L Ch R = 1 ,5758    ,127,127,127
BEGIN DESCRIPTION:
Georges Creek 11.5
END DESCRIPTION:
XS GIS Cut Line= 2
    1551171.0722     1094150.604     1550420.217    1094140.1951
#Sta/Elev= 30
    4603  832.37 4606.91  832.37 4618.43  826.94 4630.42  825.06 4681.53  823.56
 4701.16  820.84 4730.48  819.92 4766.87  823.82 4790.84  823.76 4868.79  820.39
 4881.33  818.91 4894.71  814.58 4906.78  808.31 4968.19  807.45  4974.5 803.625
 4985.11  796.37 5006.02  796.03 5020.42   796.4  5031.6 805.752  5038.1     810
  5053.6  812.12 5086.16  821.84 5136.57  823.65 5159.13  830.65 5165.88  835.65
 5179.53  837.91 5227.28  837.57 5240.96  838.66 5271.01  844.59 5353.93  848.93
#Mann= 3 ,-1,0
    4603     .13       0  4974.5     .04       0  5031.6      .1       0
#XS Ineff= 2 , 0
       0    4891  843.22    5123       0  843.22
Permanent Ineff=
       F       F
Bank Sta=4974.5,5031.6
XS Rating Curve= 0 ,0
Exp/Cntr=0.5,0.3

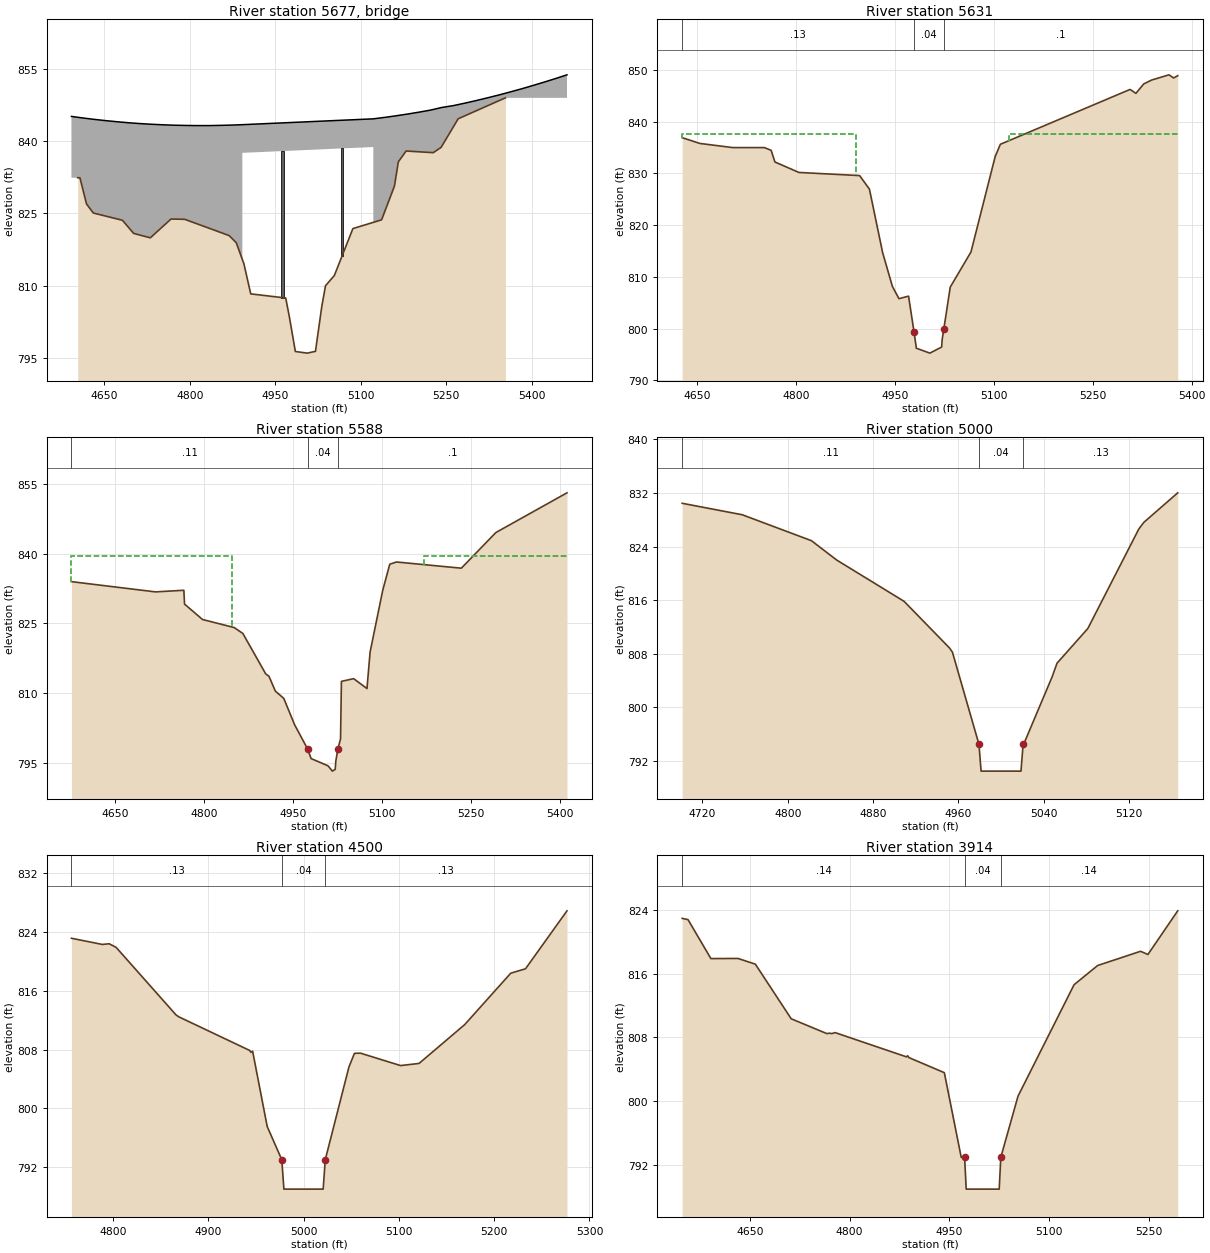
Type RM Length L Ch R = 3 ,5677    ,,,
BEGIN DESCRIPTION:
US Hwy 123 (Georges Cr.) - TOR
Structure ID: LDS_GC_03
Approximate Survey Structure
END DESCRIPTION:
Bridge Culvert--1,0,-1,-1, 0
Deck Dist Width WeirC Skew NumUp NumDn MinLoCord MaxHiCord MaxSubmerge Is_Ogee
1,125,3,0, 36, 36, , , , 0, 1,1,,
    4592    4612    4632    4652    4672    4692    4712    4732    4752    4772
    4792    4812    4832    4852    4872    4892    4892    5122    5122    5142
    5162    5182    5202    5222    5242    5262    5282    5302    5322    5342
    5362    5382    5402    5422    5442    5462
  845.08  844.76  844.47  844.21  843.98  843.77   843.6  843.46  843.35  843.26
  843.21  843.18  843.18  843.22  843.28  843.37  843.37  844.58  844.58  844.88
  845.21  845.57  845.96  846.38  846.93  847.31  847.81  848.35  848.92  849.51
  850.14  850.79  851.48  852.19  852.93   853.7
                                                                                
                                                  837.53  838.74
                                                                                
                                                
    4592    4612    4632    4652    4672    4692    4712    4732    4752    4772
    4792    4812    4832    4852    4872    4892    4892    5122    5122    5142
    5162    5182    5202    5222    5242    5262    5282    5302    5322    5342
    5362    5382    5402    5422    5442    5462
  845.08  844.76  844.47  844.21  843.98  843.77   843.6  843.46  843.35  843.26
  843.21  843.18  843.18  843.22  843.28  843.37  843.37  844.58  844.58  844.88
  845.21  845.57  845.96  846.38  846.93  847.31  847.81  848.35  848.92  849.51
  850.14  850.79  851.48  852.19  852.93   853.7
                                                                                
                                                  837.53  838.74
                                                                                
                                                
Pier Skew, UpSta & Num, DnSta & Num=  ,4962, 2 ,4962, 2 , 0 , 0 , 0 ,,
       5       5
     810     843
       5       5
     810     843
Pier Skew, UpSta & Num, DnSta & Num=  ,5067, 2 ,5067, 2 , 0 , 0 , 0 ,,
       5       5
     810     843
       5       5
     810     843
Abutment Skew #Up #Dn= , 3 , 3
    4892    4894 4965.06
  835.53  835.53     800
    4892    4894 4965.06
  835.53  835.53     800
Abutment Skew #Up #Dn= , 3 , 3
 5057.28    5120    5122
  805.38  836.74  836.74
 5057.28    5120    5122
  805.38  836.74  836.74
BR Coef=-1 ,-1 , 0 ,1.25, 0 ,,,0.8,0,2,0,
WSPro=,,,, 1 ,,,, 0 ,,,, 0 ,,,,-1 ,-1 ,-1 , 0 , 0 , 0 , 0 , 0
BC Design=,, 0 ,, 0 ,,,,,,
BC HTab HWMax=845.29
BC Use User HTab Curves=0
BC User HTab FreeFlow(D)= 0

Type RM Length L Ch R = 1 ,5631    ,43,43,43
BEGIN DESCRIPTION:
Georges Creek 11.5
END DESCRIPTION:
XS GIS Cut Line= 2
    1551172.8326    1094023.6162    1550421.9774    1094013.2073
#Sta/Elev= 30
    4628  836.91 4654.91  835.79  4704.8  834.99 4752.48  834.99  4762.8  834.47
 4768.53  832.21 4804.86  830.19 4896.89  829.58 4911.73  826.97 4931.69  814.73
 4946.53  808.17 4956.48   805.8 4971.03  806.29 4979.42  799.29 4982.84  796.23
 5003.29  795.28  5021.2  796.46 5021.99  797.91 5024.45 799.919 5034.19  808.03
 5065.63  814.83 5102.32  833.27  5110.2  835.63 5306.74  846.23 5315.57  845.47
 5327.31  847.28 5339.32  848.04 5365.62  849.05 5372.73  848.45 5378.93  848.88
#Mann= 3 ,-1,0
    4628     .13       0 4979.42     .04       0 5024.45      .1       0
#XS Ineff= 2 , 0
       0    4891  837.53    5123       0  837.53
Permanent Ineff=
       F       F
Bank Sta=4979.42,5024.45
XS Rating Curve= 0 ,0
Exp/Cntr=0.5,0.3

Type RM Length L Ch R = 1 ,5588    ,588,588,588
BEGIN DESCRIPTION:
Georges Creek 11.0
END DESCRIPTION:
XS GIS Cut Line= 3
       1551232.6      1093984.67      1550811.34      1093979.27
      1550398.19      1093990.08
#Sta/Elev= 30
  4576.8  833.96  4718.4  831.76  4766.1  832.114767.326 829.1354797.576 825.832
4850.913 824.1034865.506 822.8354904.031 814.1534909.492 813.6414920.245 810.455
4934.445 808.8964952.569 803.262  4974.5 798.0444980.428 795.9745008.932 794.421
  5016.3 793.2775021.068 793.6625022.041 795.413  5025.5 797.9675030.013 800.206
5031.502 812.5465052.072 813.1335074.556 811.0115079.796 818.8435101.183  832.15
 5112.93 837.7035124.261  838.18  5233.5  836.85  5291.6   844.5  5411.4  853.03
#Mann= 3 ,-1,0
  4576.8     .11       0  4974.5     .04       0  5025.5      .1       0
#XS Ineff= 2 , 0
       0    4848  839.47    5170       0  839.47
Permanent Ineff=
       F       F
Bank Sta=4974.5,5025.5
XS Rating Curve= 0 ,0
Exp/Cntr=0.5,0.3

Type RM Length L Ch R = 1 ,5000    ,500,500,500
BEGIN DESCRIPTION:
Georges Creek 10.0
END DESCRIPTION:
XS GIS Cut Line= 3
      1551289.64      1093568.36      1551017.53      1093444.36
        1550825.        1093425.
#Sta/Elev= 18
    4701  830.45  4757.3  828.74  4822.2  824.87    4846  821.97  4909.1  815.82
  4951.7  808.86  4954.4  808.25  4979.3  794.49  4981.3  790.49  5018.7  790.49
  5020.7  794.49  5021.2  794.49    5048  804.59  5052.5  806.59  5081.4  811.77
  5129.2  826.61  5133.9   827.6  5165.7  832.01
#Mann= 3 ,-1,0
    4701     .11       0  4979.3     .04       0  5020.7     .13       0
Bank Sta=4979.3,5020.7
XS Rating Curve= 0 ,0
Exp/Cntr=0.3,0.1

Type RM Length L Ch R = 1 ,4500    ,586,586,586
BEGIN DESCRIPTION:
Georges Creek 9.0
END DESCRIPTION:
XS GIS Cut Line= 3
        1551425.        1093025.      1551185.99      1092978.47
        1550825.        1093025.
#Sta/Elev= 23
  4756.5  823.13  4788.9  822.29  4796.1  822.38  4803.4  821.89  4866.2  812.71
  4869.1  812.45  4943.6  807.87  4944.8  807.62  4946.6  807.77  4961.9  797.53
  4977.2  793.02  4979.4  789.02  5020.6  789.02  5022.8  793.02  5047.6  805.61
  5053.4  807.48  5059.7  807.51  5101.8  805.82  5121.2  806.11  5169.1  811.39
  5217.4  818.38  5232.9  818.98  5276.4  826.86
#Mann= 3 ,-1,0
  4756.5     .13       0  4977.2     .04       0  5022.8     .13       0
Bank Sta=4977.2,5022.8
XS Rating Curve= 0 ,0
Exp/Cntr=0.3,0.1

Type RM Length L Ch R = 1 ,3914    ,414,414,414
BEGIN DESCRIPTION:
Georges Creek 8.0
END DESCRIPTION:
XS GIS Cut Line= 3
       1551472.4      1093020.11      1551538.85      1092629.68
      1551530.54       1092226.8
#Sta/Elev= 26
  4548.2  822.97  4556.9  822.82  4591.4  817.91  4632.1  817.93  4658.2  817.21
  4712.1  810.34  4765.8  808.47  4769.1  808.53  4773.1  808.48  4778.1   808.6
  4885.4  805.55  4887.2  805.69    4889  805.46  4942.3  803.56  4944.2  802.77
  4967.7  792.91  4972.8  792.91  4975.2  788.91  5024.8  788.91  5027.2  792.91
  5053.1  800.61  5137.4  814.63  5172.8  817.04  5237.3  818.83  5248.4  818.43
  5293.2  823.92
#Mann= 3 ,-1,0
  4548.2     .14       0  4972.8     .04       0  5027.2     .14       0
Bank Sta=4972.8,5027.2
XS Rating Curve= 0 ,0
Exp/Cntr=0.3,0.1

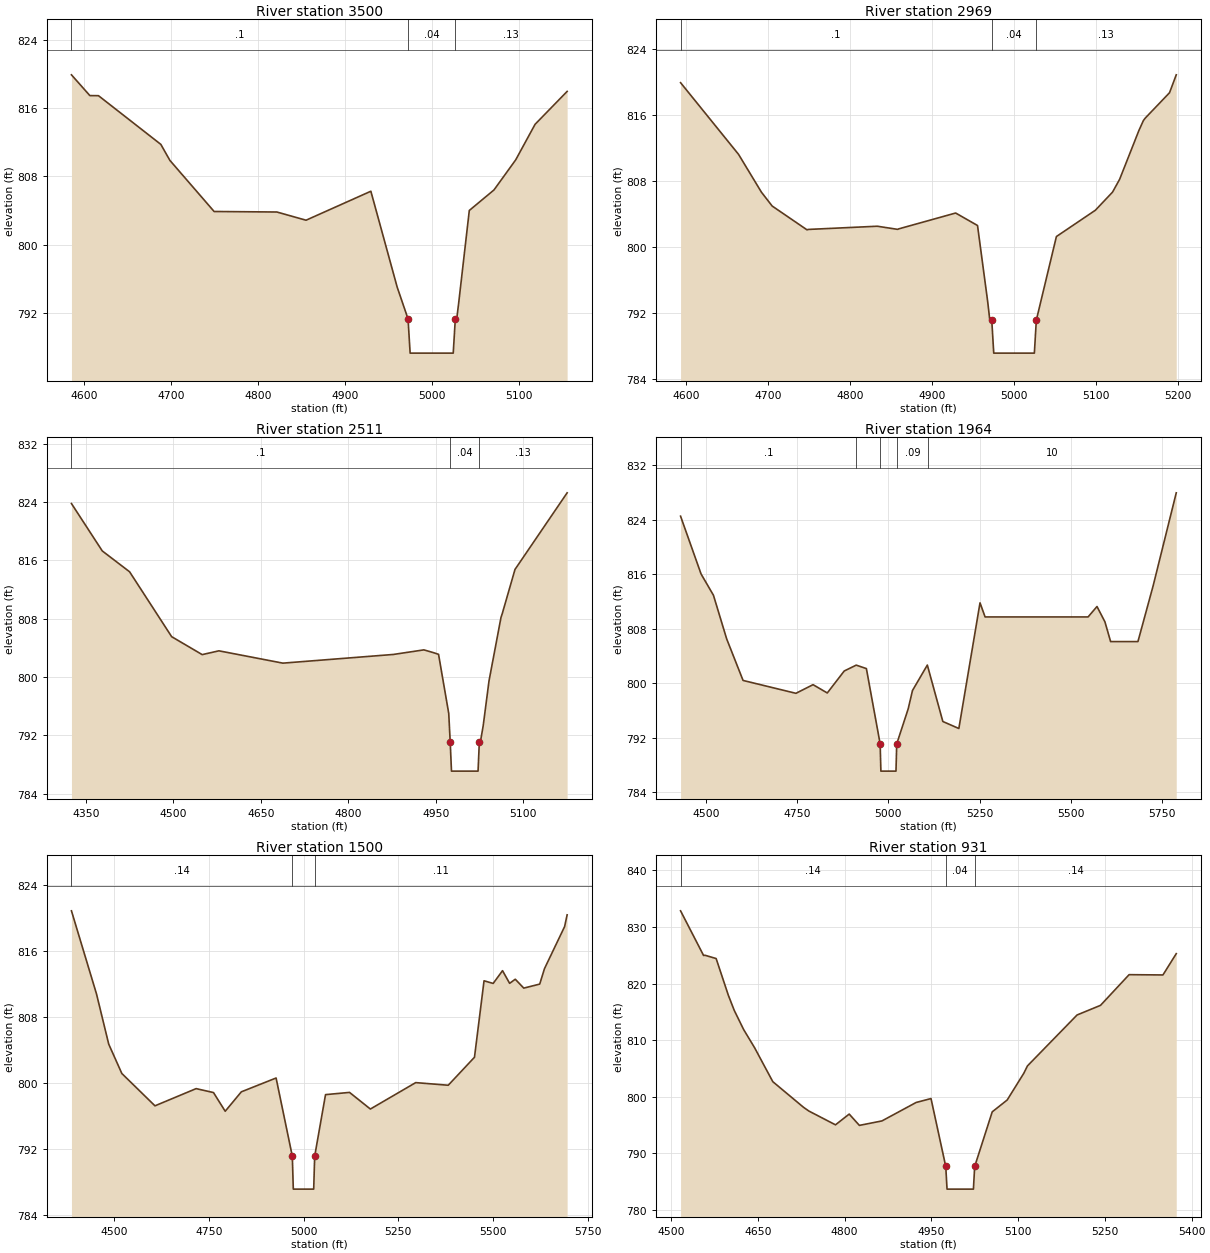
Type RM Length L Ch R = 1 ,3500    ,531,531,531
BEGIN DESCRIPTION:
Georges Creek 7.0
END DESCRIPTION:
XS GIS Cut Line= 3
       1552203.4      1092550.77       1551804.6      1092360.29
        1551625.        1092225.
#Sta/Elev= 21
  4585.4  819.88  4606.6  817.45  4616.5  817.44  4688.3  811.74  4698.7  809.87
  4749.6  803.89  4821.8  803.83  4855.4  802.87    4930  806.26  4960.3  795.04
  4972.8  791.32  4975.2  787.32  5024.8  787.32  5027.2  791.32  5028.8  791.32
  5031.1   793.2  5043.3  804.01  5071.7  806.41  5096.7  809.93    5119  814.09
  5155.9  817.94
#Mann= 3 ,-1,0
  4585.4      .1       0  4972.8     .04       0  5027.2     .13       0
Bank Sta=4972.8,5027.2
XS Rating Curve= 0 ,0
Exp/Cntr=0.3,0.1

Type RM Length L Ch R = 1 ,2969    ,458,458,458
BEGIN DESCRIPTION:
Georges Creek 6.0
END DESCRIPTION:
XS GIS Cut Line= 3
        1552425.        1092025.      1552008.19      1091886.21
      1551812.98       1091869.6
#Sta/Elev= 26
  4592.9  819.87  4663.7  811.18  4691.6   806.6  4704.7  804.92  4747.3  802.03
  4748.5  802.08  4833.1  802.47  4857.9  802.09  4858.9  802.14  4928.7  804.07
  4955.4  802.56  4967.8  793.35  4970.4  791.09  4972.8  791.09  4975.2  787.09
  5024.8  787.09  5027.2  791.09  5051.7  801.22  5099.3  804.41  5120.2   806.6
  5128.9  808.16  5152.4  814.07  5157.9  815.28  5160.2  815.58  5189.8  818.65
    5198  820.82
#Mann= 3 ,-1,0
  4592.9      .1       0  4972.8     .04       0  5027.2     .13       0
Bank Sta=4972.8,5027.2
XS Rating Curve= 0 ,0
Exp/Cntr=0.3,0.1

Type RM Length L Ch R = 1 ,2511    ,547,547,547
BEGIN DESCRIPTION:
Georges Creek 5.0
END DESCRIPTION:
XS GIS Cut Line= 4
      1552573.06      1091873.75      1552112.03      1091458.41
      1552004.04      1091408.56        1551825.        1091425.
#Sta/Elev= 24
  4324.9  823.79  4377.8  817.29  4424.7  814.43  4496.9  805.53  4549.3  803.07
    4578  803.59  4687.8   801.9  4878.8   803.1  4878.9  803.11  4929.8  803.72
  4945.4  803.36    4955  803.11  4972.5     795    4975  791.09  4977.2  787.09
  5022.8  787.09    5025  791.09  5026.8  791.09  5031.6   793.3  5041.6  799.46
  5062.2  808.18  5064.3  808.68  5086.2  814.75  5175.7  825.26
#Mann= 3 ,-1,0
  4324.9      .1       0    4975     .04       0    5025     .13       0
Bank Sta=4975,5025
XS Rating Curve= 0 ,0
Exp/Cntr=0.3,0.1

Type RM Length L Ch R = 1 ,1964    ,464,464,464
BEGIN DESCRIPTION:
Georges Creek 4.0
END DESCRIPTION:
XS GIS Cut Line= 3
      1552909.49      1091321.34      1551999.88      1090760.63
      1551513.93      1090777.24
#Sta/Elev= 30
  4430.3  824.54  4486.5  816.05  4520.4  812.93  4556.7  806.51  4601.6  800.41
  4746.5  798.52  4793.4  799.79  4832.4  798.57  4878.9   801.8  4911.7  802.66
  4939.6  802.15  4977.3  791.09  4979.3  787.09  5020.7  787.09  5022.7  791.09
  5054.1  796.23  5065.9  798.93  5106.6  802.67  5108.4  802.32  5149.1  794.38
    5193  793.35    5251  811.81  5264.9  809.74  5547.2  809.74  5571.6  811.27
  5593.4  809.01  5608.9  806.12  5683.8  806.12  5725.6  814.34  5788.8  827.97
#Mann= 5 ,-1,0
  4430.3      .1       0  4911.7     .14       0  4977.3     .04       0
  5022.7     .09       0  5108.4      10       0
Bank Sta=4977.3,5022.7
XS Rating Curve= 0 ,0
Exp/Cntr=0.3,0.1

Type RM Length L Ch R = 1 ,1500    ,569,569,569
BEGIN DESCRIPTION:
Georges Creek 3.0
END DESCRIPTION:
XS GIS Cut Line= 3
       1553042.4       1091146.9      1552683.25      1090642.64
      1552109.98      1090248.93
#Sta/Elev= 30
  4387.9   820.9    4454   810.8  4486.2  804.71  4520.8  801.14  4608.2  797.21
  4716.8   799.3  4762.6  798.82  4793.5  796.55    4836  798.91  4927.7  800.59
  4970.5  791.09  4973.1  787.09  5026.9  787.09  5029.5  791.09  5058.1  798.57
  5121.4  798.84  5176.4  796.82    5296  800.03  5381.8  799.71    5451  803.11
  5476.2   812.4  5500.3  812.08    5525  813.63  5543.7  812.09  5558.6  812.59
    5581  811.51  5623.1     812  5635.6  813.87  5688.7  818.98  5695.4  820.41
#Mann= 3 ,-1,0
  4387.9     .14       0  4970.5     .04       0  5029.5     .11       0
Bank Sta=4970.5,5029.5
XS Rating Curve= 0 ,0
Exp/Cntr=0.3,0.1

Type RM Length L Ch R = 1 ,931     ,416,416,416
BEGIN DESCRIPTION:
Georges Creek 2.0
END DESCRIPTION:
XS GIS Cut Line= 4
      1553528.36      1090361.89      1553254.23      1090374.35
      1552959.33      1090133.45      1552930.26      1089838.56
#Sta/Elev= 30
  4516.6  832.87  4556.4  824.98  4558.8  825.02  4578.1  824.44  4599.2  817.95
  4609.4  815.28  4625.5  811.92  4644.7  808.66    4676  802.69  4729.1  798.16
  4738.3   797.5  4784.4  795.06  4808.1  796.96  4825.7  794.96  4864.7  795.75
  4923.8  799.01  4949.5   799.7    4975   787.7  4977.2   783.7  5022.8   783.7
    5025   787.7  5055.3  797.35  5081.2  799.45  5109.9  804.17  5116.2  805.47
    5202  814.47  5242.5  816.17  5291.9  821.59  5350.4  821.54  5373.4   825.3
#Mann= 3 ,-1,0
  4516.6     .14       0    4975     .04       0    5025     .14       0
Bank Sta=4975,5025
XS Rating Curve= 0 ,0
Exp/Cntr=0.5,0.3

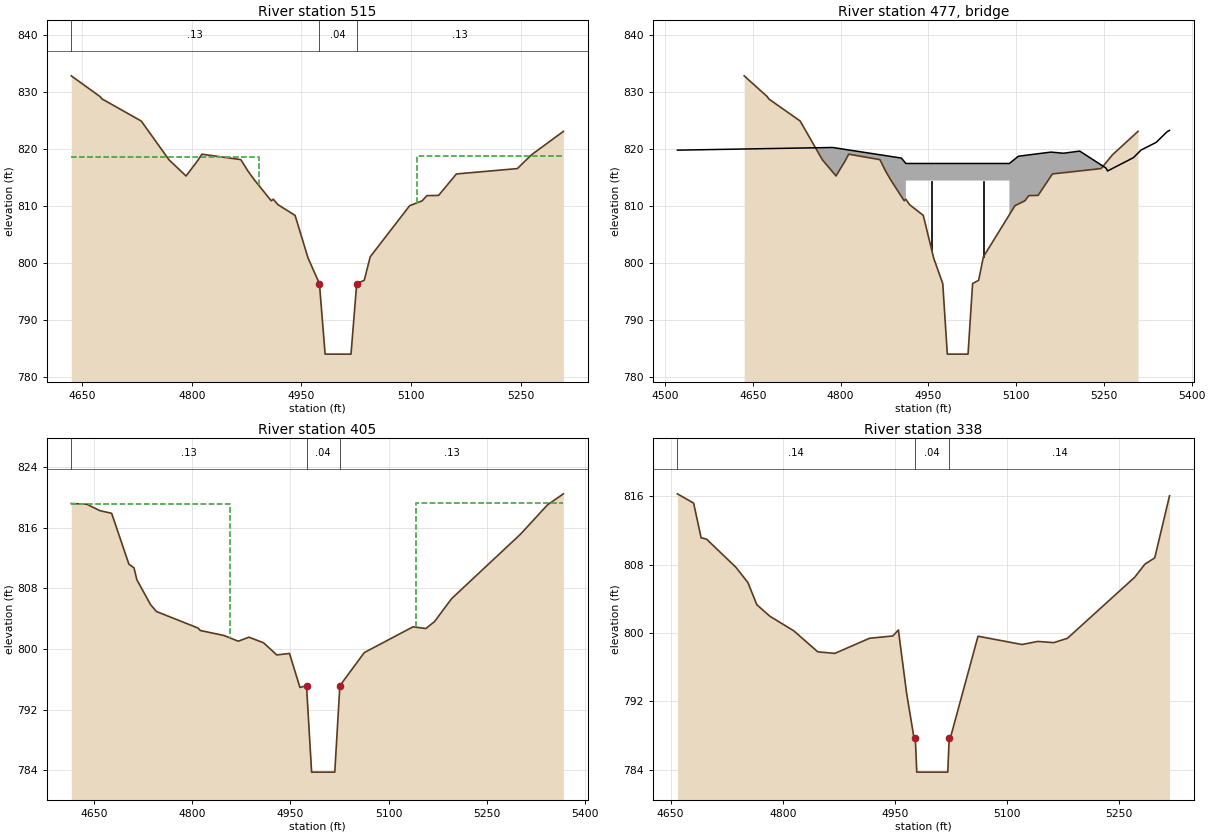
Type RM Length L Ch R = 1 ,515     ,110,110,110
BEGIN DESCRIPTION:
Georges Creek 1.8
END DESCRIPTION:
XS GIS Cut Line= 4
      1553558.25      1090119.36       1553424.7      1089949.13
      1553176.69      1089802.38      1553015.26      1089753.95
#Sta/Elev= 30
  4635.2   832.9  4674.5  829.26  4677.4  828.83  4730.9  824.96  4768.9  818.14
  4792.2   815.3  4808.6  818.09  4813.8  819.13  4867.1  818.18  4876.7   816.2
  4885.5  814.64  4908.7  810.94  4911.5  811.22  4917.9  810.26  4941.3  808.38
  4959.1  800.87  4974.6   796.4  4982.4     784  5017.8     784  5025.6   796.4
  5035.9  796.97  5044.1  801.11    5098  810.08  5115.1  810.94  5121.6  811.85
  5137.6  811.89    5162  815.66  5245.3   816.6  5264.5  819.01  5308.3  823.14
#Mann= 3 ,-1,0
  4635.2     .13       0  4974.6     .04       0  5025.6     .13       0
#XS Ineff= 2 , 0
          4891.5  818.65  5108.5          818.83
Permanent Ineff=
       F       F
Bank Sta=4974.6,5025.6
XS Rating Curve= 0 ,0
Exp/Cntr=0.5,0.3

Type RM Length L Ch R = 3 ,477     ,,,
BEGIN DESCRIPTION:
Old Easley Bridge Rd. - TOR
Structure ID: LDS_GC_01
Approximate Survey Structure
END DESCRIPTION:
Bridge Culvert--1,0,-1,-1, 0
Deck Dist Width WeirC Skew NumUp NumDn MinLoCord MaxHiCord MaxSubmerge Is_Ogee
20,36,3,0, 18, 18, , , , 0, 1,1,,
  4521.1  4786.3  4903.9  4911.5  4911.5  5088.5  5088.5  5103.7  5159.3    5181
  5208.7  5253.6  5256.3  5300.4  5313.4  5339.4  5358.4  5362.2
  819.84  820.31  818.45   817.5   817.5   817.5   817.5  818.77   819.5   819.3
  819.68  816.69  816.18  818.52  819.85  821.21  823.11  823.31
     764     764     764     764   814.5   814.5     764     764     764     764
     764     764     764     764     764     764     764     764
  4521.1  4786.3  4903.9  4911.5  4911.5  5088.5  5088.5  5103.7  5159.3    5181
  5208.7  5253.6  5256.3  5300.4  5313.4  5339.4  5358.4  5362.2
  819.84  820.31  818.45   817.5   817.5   817.5   817.5  818.77   819.5   819.3
  819.68  816.69  816.18  818.52  819.85  821.21  823.11  823.31
     764     764     764     764   814.5   814.5     764     764     764     764
     764     764     764     764     764     764     764     764
Pier Skew, UpSta & Num, DnSta & Num=  ,4955.8, 2 ,4955.8, 2 , 0 , 0 , 0 ,0,0
     2.5     2.5
  802.26   814.5
     2.5     2.5
  797.38   814.5
Pier Skew, UpSta & Num, DnSta & Num=  ,5044.3, 2 ,5044.3, 2 , 0 , 0 , 0 ,0,0
     2.5     2.5
  801.21   814.5
     2.5     2.5
  793.35   814.5
Abutment Skew #Up #Dn= , 2 , 2
  4911.5  4912.5
   814.5  811.07
  4911.5  4912.5
   814.5  800.53
Abutment Skew #Up #Dn= , 2 , 2
  5087.5  5088.5
  810.57   814.5
  5087.5  5088.5
  800.73   814.5
BR Coef=-1 ,-1 , 0 ,1.25, 0 ,,,0.8,0,2,0,
WSPro=,,,, 1 ,,,, 0 ,,,, 0 ,,,,-1 ,-1 ,-1 , 0 , 0 , 0 , 0 , 0
BC Design=,, 0 ,, 0 ,,,,,,
BC HTab HWMax=832.9
BC Use User HTab Curves=0
BC User HTab FreeFlow(D)= 0

Type RM Length L Ch R = 1 ,405     ,67,67,67
BEGIN DESCRIPTION:
Georges Creek 1.5
END DESCRIPTION:
XS GIS Cut Line= 5
      1553658.04      1090044.52       1553533.3      1089910.98
      1553399.75      1089811.18      1553228.33      1089697.53
      1553031.41      1089701.12
#Sta/Elev= 30
  4615.1  819.18  4638.9  819.09  4658.9  818.24  4676.8  817.89  4703.2  811.18
    4711   810.7  4715.3  809.14  4736.2  805.85  4745.4  804.93  4808.5  802.77
  4812.4  802.43  4848.2  801.78  4870.4  801.02  4886.6  801.55    4909  800.81
  4929.1  799.21  4948.6   799.4  4964.6  794.92  4974.6  795.15  4982.4  783.75
  5017.8  783.75  5025.6  795.15  5062.9  799.52  5137.5  802.92    5157  802.69
  5170.3  803.61  5196.3  806.63  5301.8  815.15  5342.8     819  5367.2  820.46
#Mann= 3 ,-1,0
  4615.1     .13       0  4974.6     .04       0  5025.6     .13       0
#XS Ineff= 2 , 0
          4857.5  819.18  5142.5          819.28
Permanent Ineff=
       F       F
Bank Sta=4974.6,5025.6
XS Rating Curve= 0 ,0
Exp/Cntr=0.5,0.3

Type RM Length L Ch R = 1 ,338     ,0,0,0
BEGIN DESCRIPTION:
Georges Creek 1.0
END DESCRIPTION:
XS GIS Cut Line= 4
      1553659.51      1090015.17      1553548.61      1089848.94
      1553287.98      1089640.23      1553006.46      1089677.64
#Sta/Elev= 30
  4659.1   816.3  4680.8  815.21  4690.8  811.15    4698     811  4737.2  807.71
  4753.4  805.91  4765.4   803.3    4783  801.95  4814.8  800.25  4846.9  797.79
  4869.7  797.61  4916.1  799.38  4947.3  799.65  4954.7  800.35  4965.7  792.94
  4975.6   787.7  4977.3   787.7  4979.3   783.7  5020.7   783.7  5022.7   787.7
  5024.2   787.7  5061.2  799.62    5120  798.65    5141  799.01  5162.5  798.87
  5180.7  799.37  5270.8  806.53  5284.4  808.06  5297.6   808.8  5317.4  816.08
#Mann= 3 ,-1,0
  4659.1     .14       0  4977.3     .04       0  5022.7     .14       0
Bank Sta=4977.3,5022.7
XS Rating Curve= 0 ,0
Exp/Cntr=0.3,0.1
LCMann Table=0

Chan Stop Cuts=-1
Use User Specified Reach Order=0
Composite Channel Slope=5

--- GeorgesCreek.g01 (geometry) ---

Geom Title=Existing Conditions (Effective)
Program Version=6.10

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
River Reach=Georges Creek   ,Reach-1

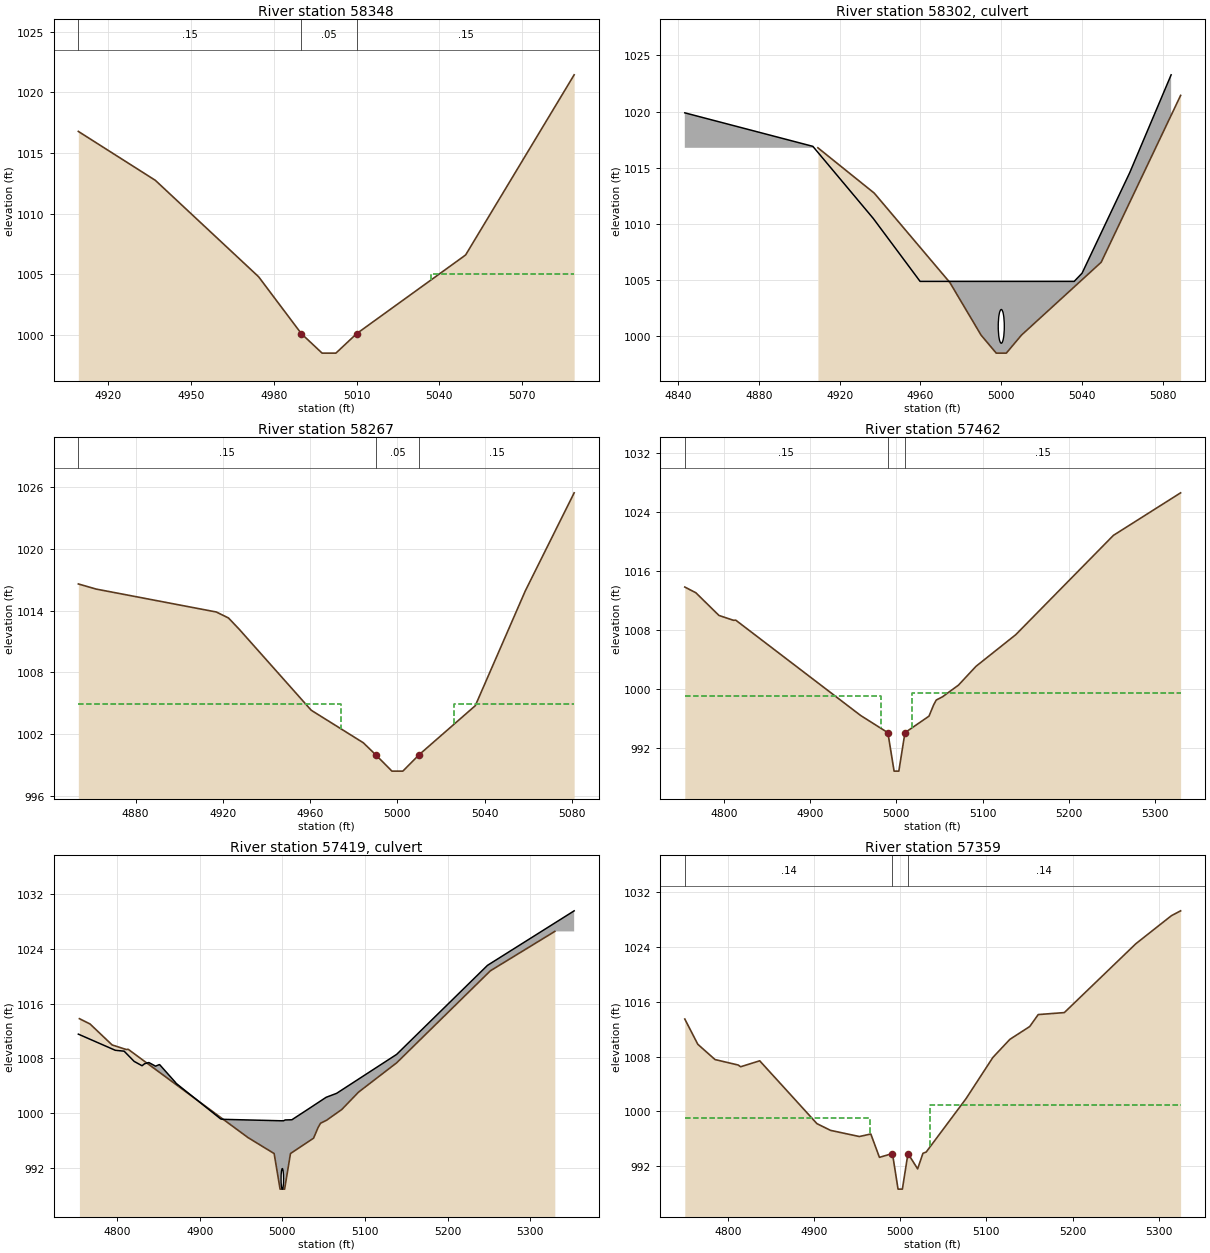
Type RM Length L Ch R = 1 ,58348   ,81,81,81
BEGIN DESCRIPTION:
Georges Creek 117
END DESCRIPTION:
XS GIS Cut Line= 3
       1515149.8      1098152.13      1515064.74      1098105.63
      1514991.02      1098068.21
#Sta/Elev= 10
  4909.2 1016.78  4937.1 1012.75  4974.5 1004.81    4990 1000.12  4997.5  998.52
  5002.5  998.52    5010 1000.12  5048.5 1006.44  5049.5 1006.61  5088.8 1021.44
#Mann= 3 ,-1,0
  4909.2     .15       0    4990     .05       0    5010     .15       0
#XS Ineff= 2 , 0
       0    4963  1004.9    5037       0 1005.07
Permanent Ineff=
       F       F
Bank Sta=4990,5010
XS Rating Curve= 0 ,0
Exp/Cntr=0.5,0.3

Type RM Length L Ch R = 2 ,58302   ,,,
BEGIN DESCRIPTION:
Private Rd. (Georges Cr.) - TOR
Structure ID: LDS_GC_19
Approximate Survey Structure
END DESCRIPTION:
Bridge Culvert--1,0,-1,-1, 0
Deck Dist Width WeirC Skew NumUp NumDn MinLoCord MaxHiCord MaxSubmerge Is_Ogee
35.5,21,3,0, 8, 8, , , , 0, 1,1,,
  4843.3  4906.7  4936.6  4959.8  5036.1    5040  5063.6  5084.1
 1019.89 1016.91  1010.5  1004.9  1004.9 1005.63 1014.57 1023.27
  978.52  978.52  978.52  978.52  978.52  978.52  978.52  978.52
  4843.3  4906.7  4936.6  4959.8  5036.1    5040  5063.6  5084.1
 1019.89 1016.91  1010.5  1004.9  1004.9 1005.63 1014.57 1023.27
  978.42  978.42  978.42  978.42  978.42  978.42  978.42  978.42
Culvert=1,3,,21,0.015,0.2,1,1,3,999.4,5000,999.3,5000,Culvert #1  , 0 ,35.5
    5000    5000
BC Culvert Barrel=1,,0
Culvert Bottom n=0.015
BC Design=,, 0 ,, 0 ,,,,,,
BC HTab HWMax=1021.44
BC Use User HTab Curves=0
BC User HTab FreeFlow(D)= 0

Type RM Length L Ch R = 1 ,58267   ,270,270,270
BEGIN DESCRIPTION:
Georges Creek 116.5
END DESCRIPTION:
XS GIS Cut Line= 3
      1515221.26      1098102.23      1515107.84      1098037.58
      1515018.24      1098001.29
#Sta/Elev= 14
  4853.8 1016.58    4862 1016.08    4917 1013.86  4922.6 1013.28  4927.5 1012.19
  4960.5 1004.33  4984.4 1001.17    4990 1000.02  4997.5  998.42  5002.5  998.42
    5010 1000.02  5035.7 1004.77  5058.6  1015.9    5081 1025.42
#Mann= 3 ,-1,0
  4853.8     .15       0    4990     .05       0    5010     .15       0
#XS Ineff= 2 , 0
       0    4974  1004.9    5026       0  1004.9
Permanent Ineff=
       F       F
Bank Sta=4990,5010
XS Rating Curve= 0 ,0
Exp/Cntr=0.5,0.3

Type RM Length L Ch R = 1 ,57462   ,103,103,103
BEGIN DESCRIPTION:
Georges Creek 115.0
END DESCRIPTION:
XS GIS Cut Line= 3
      1515744.85      1097801.92       1515691.6      1097571.18
      1515580.04       1097251.7
#Sta/Elev= 19
  4754.5 1013.82  4767.3 1013.05  4794.1 1009.98    4811 1009.32  4813.6 1009.34
  4958.5  996.44  4990.1  994.11  4997.3  988.91  5002.8  988.91  5009.9  994.11
  5037.8  996.35  5043.2  997.88  5046.2  998.53  5053.5  998.97    5072 1000.55
  5092.3 1003.09  5138.4 1007.37  5251.7 1020.81  5329.7 1026.57
#Mann= 3 ,-1,0
  4754.5     .15       0  4990.1     .05       0  5009.9     .15       0
#XS Ineff= 2 , 0
       0    4982  999.05    5018       0  999.55
Permanent Ineff=
       F       F
Bank Sta=4990.1,5009.9
XS Rating Curve= 0 ,0
Exp/Cntr=0.5,0.3

Type RM Length L Ch R = 2 ,57419   ,,,
BEGIN DESCRIPTION:
Hamilton St. (Georges Cr.) - TOR
Structure ID: LDS_GC_18
Approximate Survey Structure
END DESCRIPTION:
Bridge Culvert--1,0,-1,-1, 0
Deck Dist Width WeirC Skew NumUp NumDn MinLoCord MaxHiCord MaxSubmerge Is_Ogee
16.5,53,3,0, 25, 25, , , , 0, 1,1,,
  4753.2  4797.9  4808.6  4820.8  4830.3  4833.3  4838.5  4846.6    4851  4851.6
  4870.7  4871.6  4925.1  4926.1  4928.2  4998.5  5001.5  5003.5  5011.6  5031.4
    5053  5065.7  5138.3  5248.2  5353.1
 1011.56  1009.2 1009.07 1007.57 1006.94 1007.23 1007.41 1006.88  1007.1  1007.1
 1004.51 1004.36   999.2  999.14  999.11   998.9   998.9  999.02  999.05 1000.61
 1002.33 1002.91  1008.6 1021.61 1029.58
  968.91  968.91  968.91  968.91  968.91  968.91  968.91  968.91  968.91  968.91
  968.91  968.91  968.91  968.91  968.91  968.91  968.91  968.91  968.91  968.91
  968.91  968.91  968.91  968.91  968.91
  4753.2  4797.9  4808.6  4820.8  4830.3  4833.3  4838.5  4846.6    4851  4851.6
  4870.7  4871.6  4925.1  4926.1  4928.2  4998.5  5001.5  5003.5  5011.6  5031.4
    5053  5065.7  5138.3  5248.2  5353.1
 1011.56  1009.2 1009.07 1007.57 1006.94 1007.23 1007.41 1006.88  1007.1  1007.1
 1004.51 1004.36   999.2  999.14  999.11   998.9   998.9  999.02  999.05 1000.61
 1002.33 1002.91  1008.6 1021.61 1029.58
  968.65  968.65  968.65  968.65  968.65  968.65  968.65  968.65  968.65  968.65
  968.65  968.65  968.65  968.65  968.65  968.65  968.65  968.65  968.65  968.65
  968.65  968.65  968.65  968.65  968.65
Culvert=1,3,,53,0.015,0.2,1,1,3,988.91,5000,988.65,5000,Culvert #1  , 0 ,16.5
    5000    5000
BC Culvert Barrel=1,,0
Culvert Bottom n=0.015
BC Design=,, 0 ,, 0 ,,,,,,
BC HTab HWMax=1026.57
BC Use User HTab Curves=0
BC User HTab FreeFlow(D)= 0

Type RM Length L Ch R = 1 ,57359   ,362,362,362
BEGIN DESCRIPTION:
Georges Creek 114.5
END DESCRIPTION:
XS GIS Cut Line= 3
      1515869.09       1097779.1      1515787.95      1097545.83
      1515671.32      1097239.02
#Sta/Elev= 27
  4750.1 1013.49  4765.2  1009.8  4785.2 1007.57  4812.1 1006.77  4814.9 1006.52
    4837 1007.39  4903.4  998.21  4919.2  997.23  4952.6  996.33  4965.9   996.7
  4975.9  993.29    4991  993.85  4997.5  988.65  5002.5  988.65    5009  993.85
  5020.2  991.61  5026.4  993.89  5030.1  994.06  5076.3 1001.85  5107.5 1007.88
  5127.2 1010.52  5150.2 1012.39  5160.1 1014.14  5190.4 1014.43  5273.4 1024.49
  5314.6 1028.58  5325.3 1029.29
#Mann= 3 ,-1,0
  4750.1     .14       0    4991     .05       0    5009     .14       0
#XS Ineff= 2 , 0
       0    4965  999.07    5035       0  1000.9
Permanent Ineff=
       F       F
Bank Sta=4991,5009
XS Rating Curve= 0 ,0
Exp/Cntr=0.5,0.3