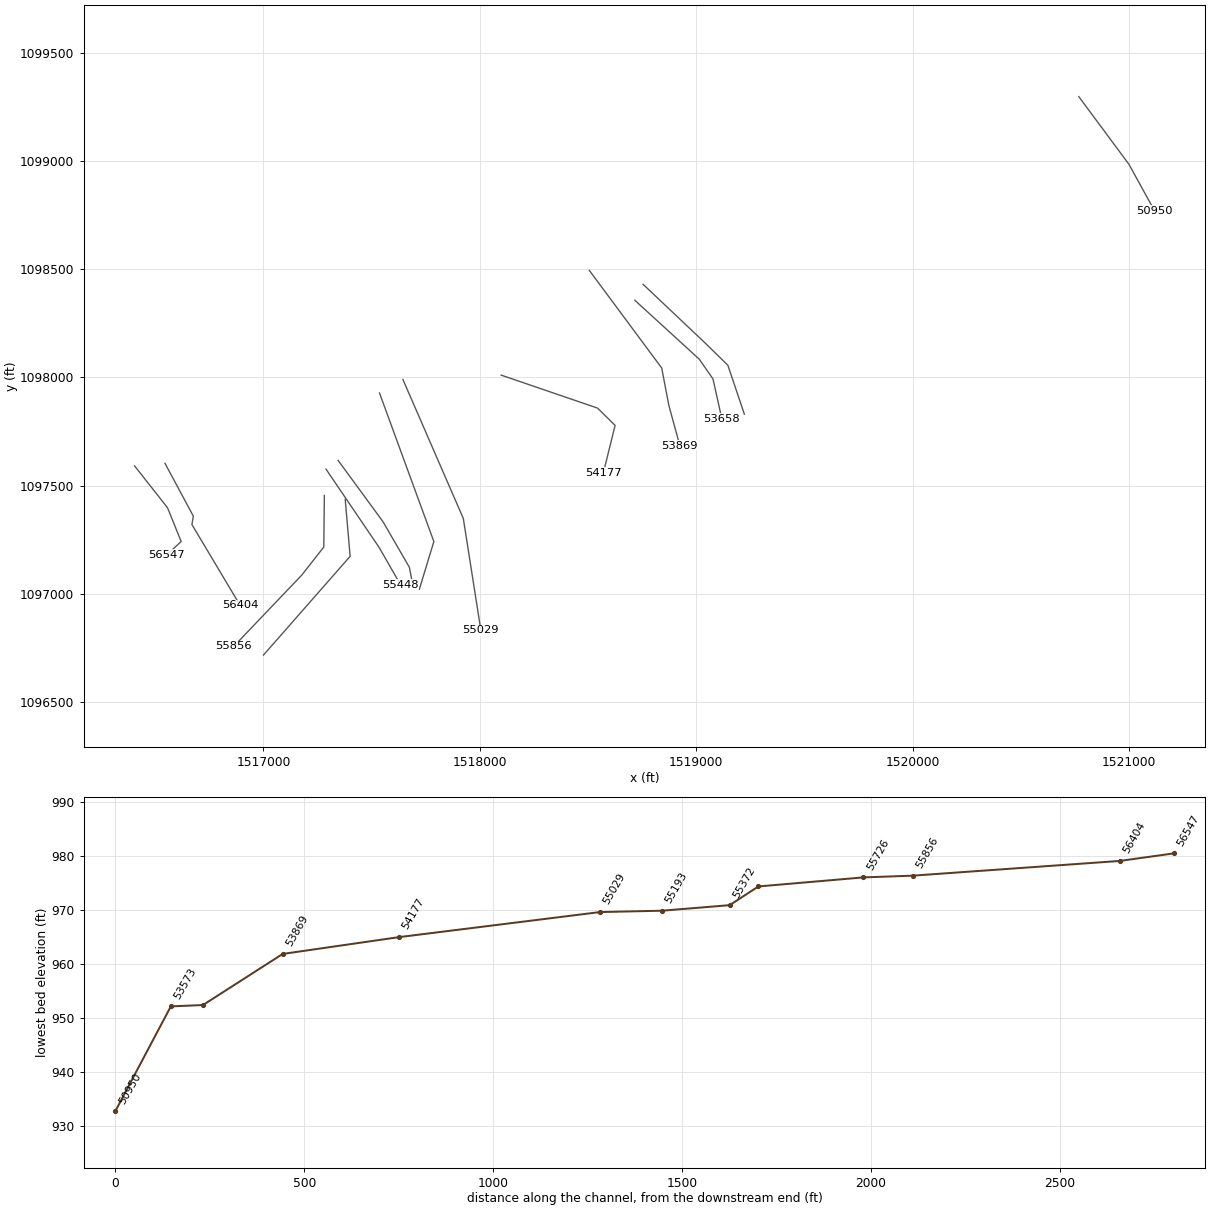
HEC-RAS study GeorgesCreek.prj: Georges Creek Limited Detail Study

--- GeorgesCreek.g01 (geometry) --- (continued)

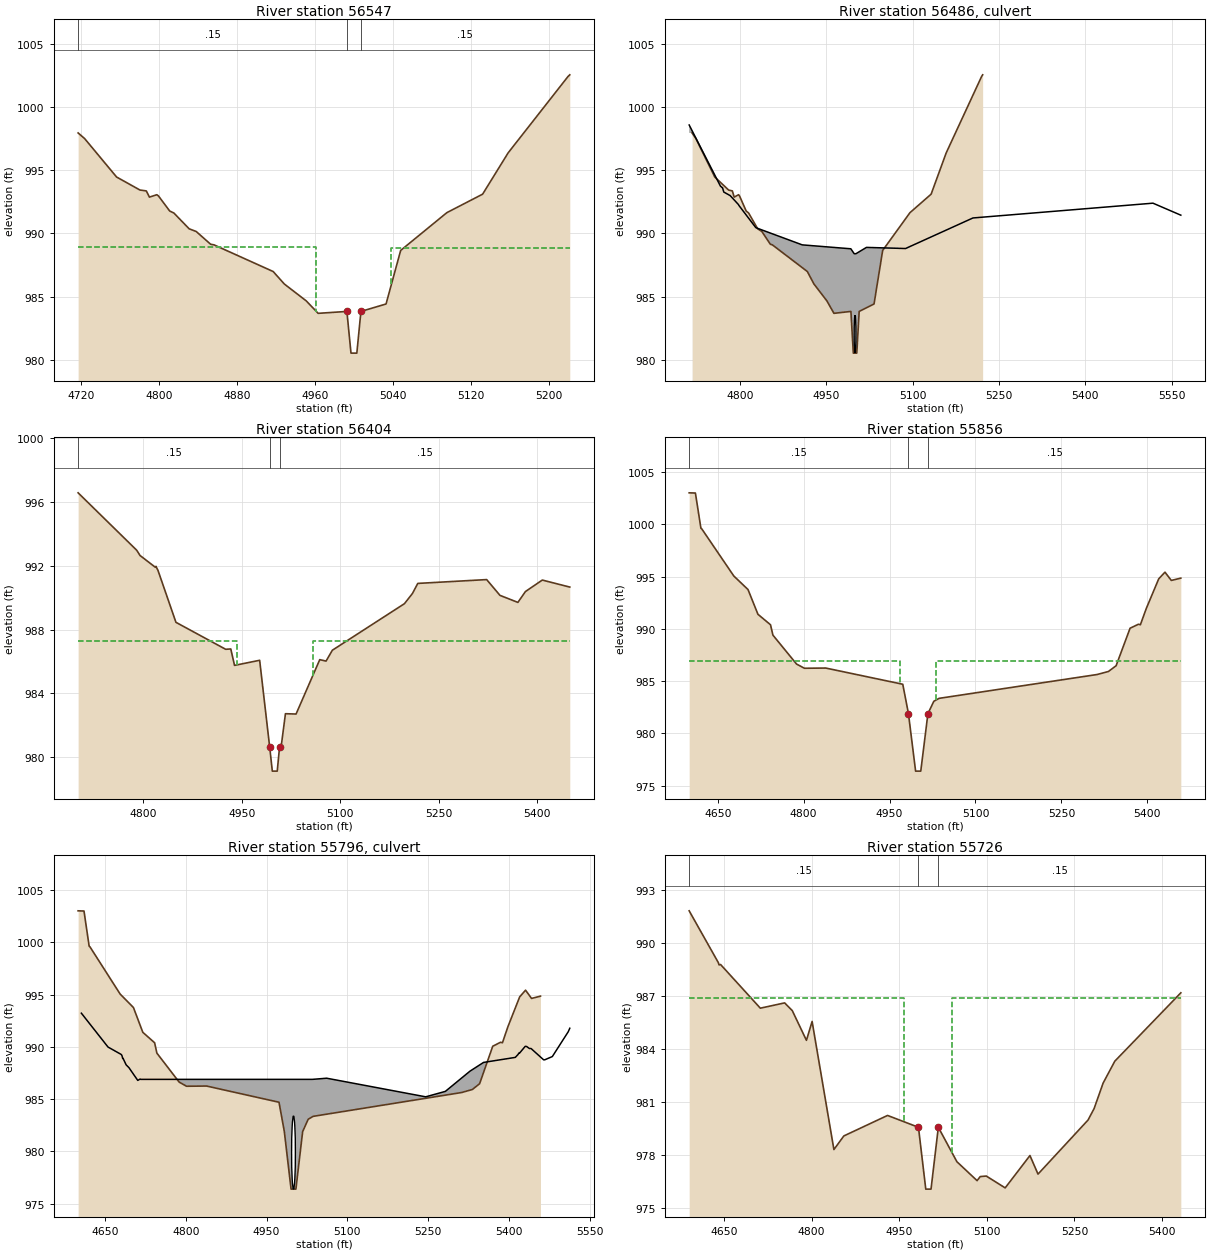
Type RM Length L Ch R = 1 ,56547   ,143,143,143
BEGIN DESCRIPTION:
Georges Creek 113.0
END DESCRIPTION:
XS GIS Cut Line= 4
       1516404.1      1097591.47      1516556.52      1097397.78
      1516619.62      1097241.56       1516553.7      1097180.71
#Sta/Elev= 30
  4716.9  997.96  4723.5  997.52  4756.4  994.47  4780.4  993.44  4786.9  993.37
  4790.1  992.88  4797.7  993.07  4799.4  992.97  4810.9  991.78  4815.2  991.62
  4830.9  990.37  4838.1  990.16  4852.9  989.15  4856.4   989.1  4917.1  986.99
  4928.6     986    4951  984.67  4963.3  983.68  4992.8  983.83    4997  980.53
    5003  980.53  5007.2  983.83    5033  984.42    5048  988.66  5095.4  991.65
  5131.8   993.1  5132.1  993.11  5158.3  996.38  5219.8 1002.43  5221.6 1002.56
#Mann= 3 ,-1,0
  4716.9     .15       0  4992.8     .05       0  5007.2     .15       0
#XS Ineff= 2 , 0
       0  4961.5   988.9  5038.5       0  988.88
Permanent Ineff=
       F       F
Bank Sta=4992.8,5007.2
XS Rating Curve= 0 ,0
Exp/Cntr=0.5,0.3

Type RM Length L Ch R = 2 ,56486   ,,,
BEGIN DESCRIPTION:
Hillcrest Dr. (Georges Cr.) - TOR
Structure ID: LDS_GC_17
Approximate Survey Structure
END DESCRIPTION:
Bridge Culvert--1,0,-1,-1, 0
Deck Dist Width WeirC Skew NumUp NumDn MinLoCord MaxHiCord MaxSubmerge Is_Ogee
37,48,3,0, 19, 19, , , , 0, 1,1,,
  4711.9  4766.2    4769  4769.8    4772  4783.1  4797.3    4798  4798.3  4827.7
  4908.3  4992.7  4998.5  5001.5  5019.8  5087.7  5204.8  5517.4  5565.8
  998.59  993.75  993.64  993.63  993.28     993   992.3  992.25  992.22  990.46
   989.1  988.79   988.4   988.4   988.9  988.81  991.23   992.4  991.45
  960.53  960.53  960.53  960.53  960.53  960.53  960.53  960.53  960.53  960.53
  960.53  960.53  960.53  960.53  960.53  960.53  960.53  960.53  960.53
  4711.9  4766.2    4769  4769.8    4772  4783.1  4797.3    4798  4798.3  4827.7
  4908.3  4992.7  4998.5  5001.5  5019.8  5087.7  5204.8  5517.4  5565.8
  998.59  993.75  993.64  993.63  993.28     993   992.3  992.25  992.22  990.46
   989.1  988.79   988.4   988.4   988.9  988.81  991.23   992.4  991.45
  960.29  960.29  960.29  960.29  960.29  960.29  960.29  960.29  960.29  960.29
  960.29  960.29  960.29  960.29  960.29  960.29  960.29  960.29  960.29
Culvert=1,3,,48,0.015,0.2,1,1,3,980.53,5000,979.13,5000,Culvert #1  , 0 ,37
    5000    5000
BC Culvert Barrel=1,,0
Culvert Bottom n=0.015
BC Design=,, 0 ,, 0 ,,,,,,
BC HTab HWMax=1002.56
BC Use User HTab Curves=0
BC User HTab FreeFlow(D)= 0

Type RM Length L Ch R = 1 ,56404   ,548,548,548
BEGIN DESCRIPTION:
Georges Creek 112.5
END DESCRIPTION:
XS GIS Cut Line= 4
      1516544.98      1097602.71      1516675.84      1097358.83
      1516669.38      1097320.07      1516891.25      1096947.79
#Sta/Elev= 30
  4700.5  996.58  4789.8  992.98  4794.9  992.65  4818.3  991.91  4819.1  991.97
  4822.2  991.72  4849.6  988.46  4925.4  986.77  4933.2  986.79  4938.9  985.76
  4977.2  986.08  4992.5  980.63  4996.5  979.13    5004  979.13  5007.5  980.63
  5010.6  980.87  5016.5  982.73  5032.7  982.71  5068.8  986.12  5078.4  986.03
    5088  986.71  5197.9  989.63  5210.1  990.27  5218.2   990.9  5323.2  991.14
  5343.5  990.15  5370.8  989.71  5382.3  990.39    5408  991.11  5449.9  990.67
#Mann= 3 ,-1,0
  4700.5     .15       0  4992.5     .05       0  5007.5     .15       0
#XS Ineff= 2 , 0
       0    4942   987.3    5058       0   987.3
Permanent Ineff=
       F       F
Bank Sta=4992.5,5007.5
XS Rating Curve= 0 ,0
Exp/Cntr=0.3,0.1

Type RM Length L Ch R = 1 ,55856   ,130,130,130
BEGIN DESCRIPTION:
Georges Creek 112.0
END DESCRIPTION:
XS GIS Cut Line= 4
      1517281.41      1097454.55      1517278.87       1097216.2
      1517177.45      1097086.89      1516863.04      1096757.26
#Sta/Elev= 30
  4600.2 1003.02  4611.1    1003  4620.7  999.63    4622  999.59  4678.2  995.06
  4702.9  993.77  4720.3   991.4  4742.2   990.4  4746.4  989.41  4787.7  986.64
  4801.4  986.24  4838.6  986.26  4973.1  984.71    4983   981.9  4995.5   976.4
  5004.5   976.4    5017   981.9  5027.3  983.08  5036.4  983.36  5312.2  985.64
  5332.1  985.93  5345.5  986.48  5369.9  990.07  5384.5  990.45  5387.9   990.4
    5398  991.93  5419.9  994.79  5430.8  995.43  5441.9  994.64  5458.5  994.86
#Mann= 3 ,-1,0
  4600.2     .15       0    4983     .05       0    5017     .15       0
#XS Ineff= 2 , 0
       0    4969   986.9    5031       0   986.9
Permanent Ineff=
       F       F
Bank Sta=4983,5017
XS Rating Curve= 0 ,0
Exp/Cntr=0.5,0.3

Type RM Length L Ch R = 2 ,55796   ,,,
BEGIN DESCRIPTION:
Fleetwood Dr. (Georges Cr.) - TOR
Structure ID: LDS_GC_16
Approximate Survey Structure
END DESCRIPTION:
Bridge Culvert--1,0,-1,-1, 0
Deck Dist Width WeirC Skew NumUp NumDn MinLoCord MaxHiCord MaxSubmerge Is_Ogee
27.5,65,3,0, 31, 31, , , , 0, 1,1,,
  4606.2  4655.7  4679.9  4680.7  4681.7  4682.9  4683.7  4689.3  4694.5  4710.9
  4715.3  4715.8  5035.3  5061.6  5245.4  5281.9  5327.5  5352.8  5411.7  5416.5
  5418.6  5419.3  5430.2  5432.9    5438    5441  5464.3  5466.4  5480.5  5510.1
  5512.9
  993.23  989.99  989.29  989.25  989.15   988.9   988.9  988.29  988.02   986.8
  986.93   986.9   986.9  987.01  985.23  985.75  987.68  988.52     989  989.26
  989.42  989.39  990.06  990.04  989.85  989.85  988.77  988.77  989.08  991.46
  991.79
   956.4   956.4   956.4   956.4   956.4   956.4   956.4   956.4   956.4   956.4
   956.4   956.4   956.4   956.4   956.4   956.4   956.4   956.4   956.4   956.4
   956.4   956.4   956.4   956.4   956.4   956.4   956.4   956.4   956.4   956.4
   956.4
  4606.2  4655.7  4679.9  4680.7  4681.7  4682.9  4683.7  4689.3  4694.5  4710.9
  4715.3  4715.8  5035.3  5061.6  5245.4  5281.9  5327.5  5352.8  5411.7  5416.5
  5418.6  5419.3  5430.2  5432.9    5438    5441  5464.3  5466.4  5480.5  5510.1
  5512.9
  993.23  989.99  989.29  989.25  989.15   988.9   988.9  988.29  988.02   986.8
  986.93   986.9   986.9  987.01  985.23  985.75  987.68  988.52     989  989.26
  989.42  989.39  990.06  990.04  989.85  989.85  988.77  988.77  989.08  991.46
  991.79
  956.08  956.08  956.08  956.08  956.08  956.08  956.08  956.08  956.08  956.08
  956.08  956.08  956.08  956.08  956.08  956.08  956.08  956.08  956.08  956.08
  956.08  956.08  956.08  956.08  956.08  956.08  956.08  956.08  956.08  956.08
  956.08
Culvert=1,7,,65,0.015,0.4,1,1,3,976.4,5000,976.08,5000,Culvert #1  , 0 ,27.5
    5000    5000
BC Culvert Barrel=1,,0
Culvert Bottom n=0.015
BC Design=,, 0 ,, 0 ,,,,,,
BC HTab HWMax=1003.02
BC Use User HTab Curves=0
BC User HTab FreeFlow(D)= 0

Type RM Length L Ch R = 1 ,55726   ,278,278,278
BEGIN DESCRIPTION:
Georges Creek 111.5
END DESCRIPTION:
XS GIS Cut Line= 3
      1517377.76       1097436.8      1517400.58       1097173.1
      1516999.96       1096716.7
#Sta/Elev= 28
  4590.6  991.83  4640.5   988.9  4641.8  988.77  4644.4  988.79  4712.4  986.32
    4754  986.62  4767.1  986.18  4791.3   984.5    4801  985.57  4838.3  978.32
  4855.3  979.09  4930.1  980.25    4983  979.58  4995.5  976.08  5004.5  976.08
    5017  979.58  5048.8  977.63  5083.3  976.56  5088.7  976.79  5099.1  976.82
  5131.4  976.15  5173.8  977.98  5187.6  976.93  5273.2  979.99  5283.6  980.64
    5299  982.08    5319  983.32    5432  987.19
#Mann= 3 ,-1,0
  4590.6     .15       0    4983     .05       0    5017     .15       0
#XS Ineff= 2 , 0
       0    4959   986.9    5041       0  986.92
Permanent Ineff=
       F       F
Bank Sta=4983,5017
XS Rating Curve= 0 ,0
Exp/Cntr=0.5,0.3

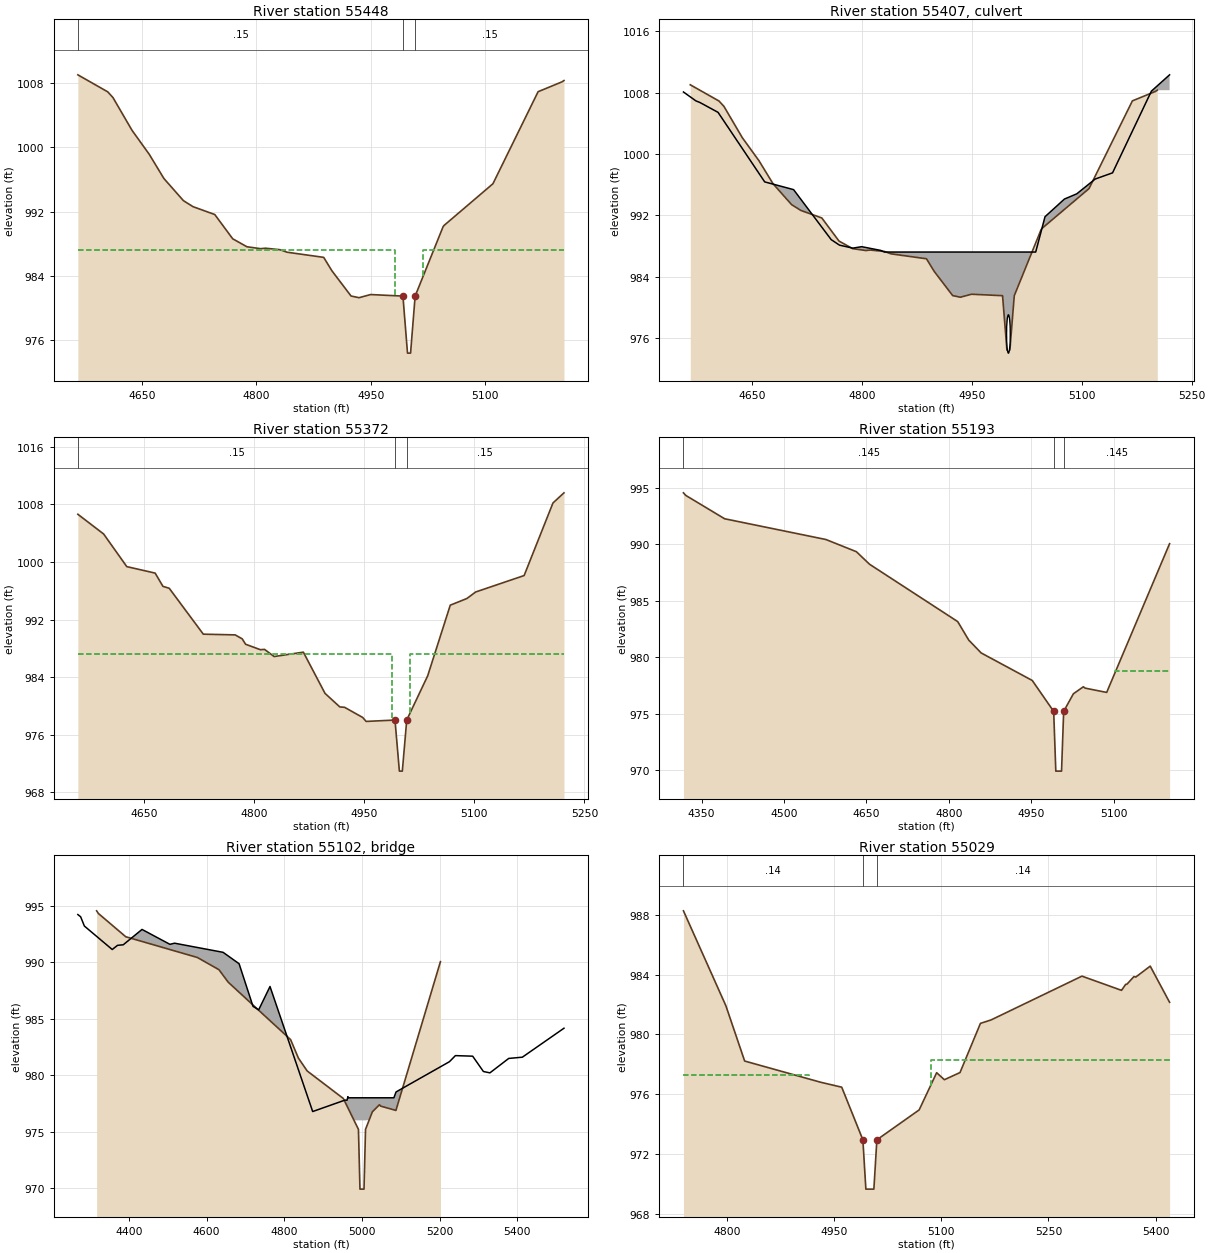
Type RM Length L Ch R = 1 ,55448   ,76,76,76
BEGIN DESCRIPTION:
Georges Creek 111.0
END DESCRIPTION:
XS GIS Cut Line= 3
      1517289.01      1097576.26      1517534.97      1097213.67
      1517633.85      1097041.25
#Sta/Elev= 30
  4566.1 1009.04  4605.3 1006.92  4612.1 1006.21  4637.1 1002.13  4659.7  999.14
  4678.9  996.13  4704.4  993.38    4717  992.63  4745.5  991.65    4769  988.63
  4787.6  987.64  4805.6   987.4  4811.9  987.46  4831.1  987.27  4840.2  986.96
  4888.2  986.32  4898.8  984.67    4924  981.51  4934.5   981.3  4949.6  981.69
    4992   981.5    4998   974.4    5002   974.4    5008   981.5  5044.6  990.13
  5046.1  990.31  5109.9  995.48  5169.1 1006.94  5200.5 1008.17    5203 1008.33
#Mann= 3 ,-1,0
  4566.1     .15       0    4992     .05       0    5008     .15       0
#XS Ineff= 2 , 0
       0  4981.5   987.2  5018.5       0   987.2
Permanent Ineff=
       F       F
Bank Sta=4992,5008
XS Rating Curve= 0 ,0
Exp/Cntr=0.5,0.3

Type RM Length L Ch R = 2 ,55407   ,,,
BEGIN DESCRIPTION:
Ann Drive - TOR
Structure ID: LDS_GC_15A
Approximate Survey Structure
END DESCRIPTION:
Bridge Culvert--1,0,-1,-1, 0
Deck Dist Width WeirC Skew NumUp NumDn MinLoCord MaxHiCord MaxSubmerge Is_Ogee
16,50,3,0, 20, 20, , , , 0, 1,1,,
  4556.8  4573.7  4579.4    4604  4667.6    4707  4758.3  4769.6  4787.7  4799.9
    4826    4831  5037.2  5049.9  5076.4  5093.2  5118.3    5142    5195  5219.8
  1008.1 1006.94 1006.72 1005.44  996.36  995.35  988.82   988.1  987.71   987.9
  987.41   987.2   987.2  991.81  994.12   994.8  996.73  997.54 1008.21 1010.34
  952.18  952.18  952.18  952.18  952.18  952.18  952.18  952.18  952.18  952.18
  952.18  952.18  952.18  952.18  952.18  952.18  952.18  952.18  952.18  952.18
  4556.8  4573.7  4579.4    4604  4667.6    4707  4758.3  4769.6  4787.7  4799.9
    4826    4831  5037.2  5049.9  5076.4  5093.2  5118.3    5142    5195  5219.8
  1008.1 1006.94 1006.72 1005.44  996.36  995.35  988.82   988.1  987.71   987.9
  987.41   987.2   987.2  991.81  994.12   994.8  996.73  997.54 1008.21 1010.34
  951.93  951.93  951.93  951.93  951.93  951.93  951.93  951.93  951.93  951.93
  951.93  951.93  951.93  951.93  951.93  951.93  951.93  951.93  951.93  951.93
Culvert=1,5,,50,0.015,0.2,1,1,3,974,5000,973.75,5000,Culvert #1  , 0 ,16
    5000    5000
BC Culvert Barrel=1,,0
Culvert Bottom n=0.015
BC Design=,, 0 ,, 0 ,,,,,,
BC HTab HWMax=1009.04
BC Use User HTab Curves=0
BC User HTab FreeFlow(D)= 0

Type RM Length L Ch R = 1 ,55372   ,179,179,179
BEGIN DESCRIPTION:
Georges Creek 110.5
END DESCRIPTION:
XS GIS Cut Line= 4
       1517344.8      1097616.83      1517552.71      1097332.84
      1517674.42      1097122.39       1517687.1      1097056.46
#Sta/Elev= 30
    4560 1006.64  4595.1  1003.9  4626.7  999.36  4665.3  998.46  4675.9  996.62
  4684.5  996.35  4730.9  989.97  4774.3  989.87  4783.9  989.32  4788.5  988.57
  4808.7  987.81  4814.2  987.86  4827.4  986.86  4867.2  987.47  4896.7  981.74
  4916.8  979.86  4923.4   979.8    4948  978.39  4952.7  977.84    4992  978.03
    4998  970.93    5002  970.93    5008  978.03  5036.5  984.17  5067.3     994
    5090  994.93  5101.8  995.83  5167.9  998.12  5207.2 1008.21  5222.2 1009.62
#Mann= 3 ,-1,0
    4560     .15       0    4992     .05       0    5008     .15       0
#XS Ineff= 2 , 0
       0  4987.5   987.2  5012.5       0   987.2
Permanent Ineff=
       F       F
Bank Sta=4992,5008
XS Rating Curve= 0 ,0
Exp/Cntr=0.5,0.3

Type RM Length L Ch R = 1 ,55193   ,164,164,164
BEGIN DESCRIPTION:
Georges Creek 110.0
END DESCRIPTION:
XS GIS Cut Line= 3
      1517536.27      1097928.13      1517787.49      1097241.47
       1517720.5      1097020.96
#Sta/Elev= 19
  4316.9  994.58  4321.2  994.35  4391.9  992.28  4576.3  990.44  4631.7  989.36
  4655.6  988.25  4816.2  983.16  4836.3  981.52  4858.9  980.38  4951.9  977.94
  4990.9   975.2  4994.8   969.9  5005.2   969.9  5009.1   975.2  5026.8  976.76
  5044.9  977.38  5048.1  977.26  5087.4  976.88  5201.9  990.07
#Mann= 3 ,-1,0
  4316.9    .145       0  4990.9    .049       0  5009.1    .145       0
#XS Ineff= 2 , 0
       0    4897  977.07    5103       0  978.81
Permanent Ineff=
       F       F
Bank Sta=4990.9,5009.1
XS Rating Curve= 0 ,0
Exp/Cntr=0.5,0.3

Type RM Length L Ch R = 3 ,55102   ,,,
BEGIN DESCRIPTION:
N. Gray Haven Lane - TOR
Structure ID: LDS_GC_15
Approximate Survey Structure
END DESCRIPTION:
Bridge Culvert--1,0,-1,-1, 0
Deck Dist Width WeirC Skew NumUp NumDn MinLoCord MaxHiCord MaxSubmerge Is_Ogee
84.5,13,3,0, 34, 34, , , , 0, 1,1,,
  4268.5  4275.7  4285.3    4357  4370.7  4385.4  4433.7  4505.5  4517.6  4642.4
  4683.6  4719.4    4734  4763.2  4868.4    4873  4956.7  4961.4  4963.8  4964.2
  4981.5  4981.5  5018.5  5018.5  5082.1  5087.7  5225.1  5240.5  5284.9  5312.6
  5329.3  5377.7  5412.8    5520
  994.25  994.05  993.23  991.15  991.52  991.57  992.93  991.61  991.71   990.9
  989.89  986.11   985.8  987.87  977.25  976.78   977.8  977.78   978.1     978
     978     978     978     978     978  978.52   981.2  981.74  981.69  980.33
  980.21  981.49   981.6  984.17
   949.9   949.9   949.9   949.9   949.9   949.9   949.9   949.9   949.9   949.9
   949.9   949.9   949.9   949.9   949.9   949.9   949.9   949.9   949.9   949.9
   949.9     976     976   949.9   949.9   949.9   949.9   949.9   949.9   949.9
   949.9   949.9   949.9   949.9
  4268.5  4275.7  4285.3    4357  4370.7  4385.4  4433.7  4505.5  4517.6  4642.4
  4683.6  4719.4    4734  4763.2  4868.4    4873  4956.7  4961.4  4963.8  4964.2
  4981.5  4981.5  5018.5  5018.5  5082.1  5087.7  5225.1  5240.5  5284.9  5312.6
  5329.3  5377.7  5412.8    5520
  994.25  994.05  993.23  991.15  991.52  991.57  992.93  991.61  991.71   990.9
  989.89  986.11   985.8  987.87  977.25  976.78   977.8  977.78   978.1     978
     978     978     978     978     978  978.52   981.2  981.74  981.69  980.33
  980.21  981.49   981.6  984.17
   949.9   949.9   949.9   949.9   949.9   949.9   949.9   949.9   949.9   949.9
   949.9   949.9   949.9   949.9   949.9   949.9   949.9   949.9   949.9   949.9
   949.9     976     976   949.9   949.9   949.9   949.9   949.9   949.9   949.9
   949.9   949.9   949.9   949.9
Abutment Skew #Up #Dn= , 2 , 2
  4981.5  4982.5
     976  976.29
  4981.5  4982.5
     976  975.44
Abutment Skew #Up #Dn= , 2 , 2
  5017.5  5018.5
  976.82     976
  5017.5  5018.5
  971.88     976
BR Coef= 1 , 1 , 0 ,1.25, 0 ,,,0.8,0,2,0,
WSPro=,,,, 1 ,,,, 0 ,,,, 0 ,,,,-1 ,-1 ,-1 , 0 , 0 , 0 , 0 , 0
BC Design=,, 0 ,, 0 ,,,,,,
BC HTab HWMax=994.58
BC Use User HTab Curves=0
BC User HTab FreeFlow(D)= 0

Type RM Length L Ch R = 1 ,55029   ,532,532,532
BEGIN DESCRIPTION:
Georges Creek 109.5
END DESCRIPTION:
XS GIS Cut Line= 3
      1517644.46      1097990.65      1517923.68      1097348.14
      1518004.74      1096831.74
#Sta/Elev= 24
    4739  988.27  4798.4  981.92  4824.7  978.22  4931.2   976.8  4960.6  976.47
  4990.2  972.95  4994.4  969.65  5005.6  969.65  5009.8  972.95    5069  974.95
  5093.5  977.44  5104.3  976.97  5126.2  977.45  5154.8  980.74  5169.7  980.97
  5296.9   983.9  5352.3  982.95  5352.8  982.98  5358.1  983.35  5359.9  983.36
  5369.7  983.87  5372.3  983.84  5392.5  984.57  5419.6  982.15
#Mann= 3 ,-1,0
    4739     .14       0  4990.2    .048       0  5009.8     .14       0
#XS Ineff= 2 , 0
       0    4915  977.29    5085       0  978.27
Permanent Ineff=
       F       F
Bank Sta=4990.2,5009.8
XS Rating Curve= 0 ,0
Exp/Cntr=0.5,0.3

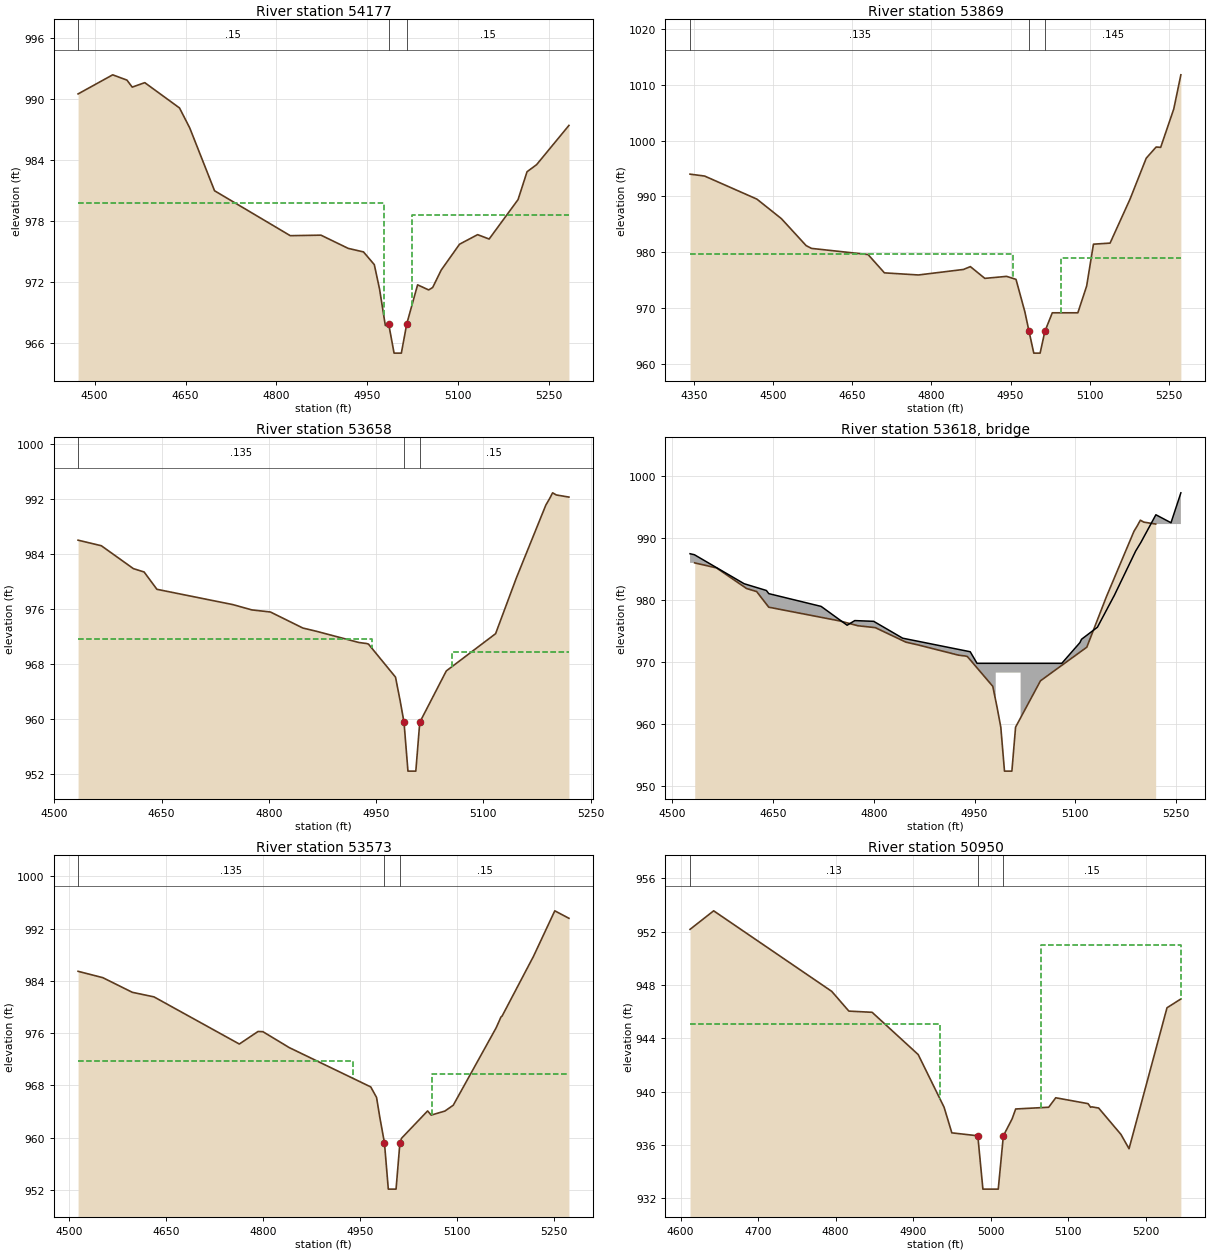
Type RM Length L Ch R = 1 ,54177   ,308,308,308
BEGIN DESCRIPTION:
Georges Creek 108.0
END DESCRIPTION:
XS GIS Cut Line= 4
      1518098.47      1098010.81      1518543.93      1097858.39
      1518625.26       1097778.4      1518571.28      1097560.32
#Sta/Elev= 30
  4472.8  990.51  4529.9  992.39  4553.4  991.87  4562.1  991.18  4582.8  991.62
  4640.1  989.13    4657  987.16  4697.9  980.98  4822.8  976.56  4873.4  976.61
  4918.3  975.31  4943.6  974.96  4961.4  973.71  4970.1  971.29  4979.6  967.71
    4985   967.9    4994     965    5006     965    5015   967.9  5032.8  971.72
  5051.1  971.22  5057.7  971.46  5071.7  973.17    5102  975.72  5131.8  976.66
  5150.8  976.23  5198.5  980.11  5213.3  982.85  5229.1  983.55  5282.4  987.41
#Mann= 3 ,-1,0
  4472.8     .15       0    4985     .05       0    5015     .15       0
#XS Ineff= 2 , 0
       0    4977  979.81    5023       0  978.59
Permanent Ineff=
       F       F
Bank Sta=4985,5015
XS Rating Curve= 0 ,0
Exp/Cntr=0.5,0.3

Type RM Length L Ch R = 1 ,53869   ,211,211,211
BEGIN DESCRIPTION:
Georges Creek 107.9
END DESCRIPTION:
XS GIS Cut Line= 4
      1518506.19      1098494.64      1518840.58      1098043.69
      1518873.58      1097871.06       1518924.5      1097684.66
#Sta/Elev= 30
  4342.4  994.01    4370  993.67  4469.1  989.53  4515.5  986.03  4562.6  981.17
  4572.8  980.68  4679.9  979.58  4710.9  976.29  4775.3  975.91  4860.7   976.9
  4873.8  977.41  4901.2   975.3  4942.5  975.66  4960.3  975.12  4977.1  969.29
    4985  965.78    4994  961.88    5006  961.88    5015  965.78  5029.1  969.12
  5077.5  969.12  5094.2  973.92  5107.1  981.44  5138.6  981.63  5176.5  989.54
  5207.1  996.87  5225.9  998.88  5234.5  998.82  5259.3  1005.7  5272.8 1011.84
#Mann= 3 ,-1,0
  4342.4    .135       0    4985     .05       0    5015    .145       0
#XS Ineff= 2 , 0
       0    4955  979.69    5045       0  978.92
Permanent Ineff=
       F       F
Bank Sta=4985,5015
XS Rating Curve= 0 ,0
Exp/Cntr=0.5,0.3

Type RM Length L Ch R = 1 ,53658   ,85,85,85
BEGIN DESCRIPTION:
Georges Creek 107.7
END DESCRIPTION:
XS GIS Cut Line= 4
      1518716.49       1098356.7      1519014.06      1098084.56
      1519077.65        1097993.      1519118.34      1097809.88
#Sta/Elev= 27
  4533.4  986.01  4565.9   985.2  4610.7  981.87  4625.7  981.38  4643.6  978.86
  4749.9  976.63  4776.4  975.86  4802.2  975.56  4847.7  973.22  4865.9  972.77
  4925.9  971.12  4936.7  970.97  4939.3  970.89  4977.1  966.08  4983.6  962.63
    4989   959.5  4994.5   952.4  5005.5   952.4    5011   959.5  5048.1  966.98
    5117   972.4  5146.1  980.53  5187.2  991.11  5192.5  992.06  5196.7   992.9
  5201.9  992.59  5219.5  992.28
#Mann= 3 ,-1,0
  4533.4    .135       0    4989     .05       0    5011     .15       0
#XS Ineff= 2 , 0
       0    4944  971.58    5056       0   969.8
Permanent Ineff=
       F       F
Bank Sta=4989,5011
XS Rating Curve= 0 ,0
Exp/Cntr=0.5,0.3

Type RM Length L Ch R = 3 ,53618   ,,,
BEGIN DESCRIPTION:
Footbridge (Georges Cr.) - TOR
Structure ID: Footbridge (Georges Cr.)
Approximate Survey Structure
END DESCRIPTION:
Bridge Culvert--1,0,-1,-1, 0
Deck Dist Width WeirC Skew NumUp NumDn MinLoCord MaxHiCord MaxSubmerge Is_Ogee
37.5,5,3,0, 26, 26, , , , 0, 1,1,,
  4526.5    4533    4607  4640.1  4643.7  4721.6  4760.3  4771.7  4799.8  4842.9
  4943.5  4953.6  4981.5  4981.5  5018.5  5018.5  5079.8  5106.8  5109.1  5132.8
  5158.2  5189.8  5197.6  5219.8  5242.3    5257
  987.49  987.33  982.65  981.56  981.05  978.99  975.95   976.7  976.58  973.86
  971.67   969.8   969.8   969.8   969.8   969.8   969.8  973.15  973.68  975.63
  980.82  987.94  989.34  993.78  992.49  997.32
   932.4   932.4   932.4   932.4   932.4   932.4   932.4   932.4   932.4   932.4
   932.4   932.4   932.4   968.3   968.3   932.4   932.4   932.4   932.4   932.4
   932.4   932.4   932.4   932.4   932.4   932.4
  4526.5    4533    4607  4640.1  4643.7  4721.6  4760.3  4771.7  4799.8  4842.9
  4943.5  4953.6  4981.5  4981.5  5018.5  5018.5  5079.8  5106.8  5109.1  5132.8
  5158.2  5189.8  5197.6  5219.8  5242.3    5257
  987.49  987.33  982.65  981.56  981.05  978.99  975.95   976.7  976.58  973.86
  971.67   969.8   969.8   969.8   969.8   969.8   969.8  973.15  973.68  975.63
  980.82  987.94  989.34  993.78  992.49  997.32
   932.4   932.4   932.4   932.4   932.4   932.4   932.4   932.4   932.4   932.4
   932.4   932.4   932.4   968.3   968.3   932.4   932.4   932.4   932.4   932.4
   932.4   932.4   932.4   932.4   932.4   932.4
Abutment Skew #Up #Dn= , 2 , 2
  4981.5  4982.5
   968.3  963.43
  4981.5  4982.5
   968.3  963.28
Abutment Skew #Up #Dn= , 2 , 2
  5017.5  5018.5
  969.24   968.3
  5017.5  5018.5
   961.4   968.3
BR Coef= 1 , 1 , 0 ,1.25, 0 ,,,0.8,0,2,0,
WSPro=,,,, 1 ,,,, 0 ,,,, 0 ,,,,-1 ,-1 ,-1 , 0 , 0 , 0 , 0 , 0
BC Design=,, 0 ,, 0 ,,,,,,
BC HTab HWMax=992.9
BC Use User HTab Curves=0
BC User HTab FreeFlow(D)= 0

Type RM Length L Ch R = 1 ,53573   ,147,147,147
BEGIN DESCRIPTION:
Gedorges Creek 107.5
END DESCRIPTION:
XS GIS Cut Line= 4
      1518754.64      1098430.45      1519036.95       1098163.4
      1519146.32      1098056.59      1519222.61      1097830.23
#Sta/Elev= 27
  4513.4  985.46  4551.7  984.49  4597.4  982.25    4631  981.55  4763.2  974.34
  4792.2  976.26  4799.7  976.23  4840.6  973.79  4966.8  967.78  4975.8  966.17
  4980.7  963.21    4988  959.25    4994  952.15    5006  952.15    5012  959.25
  5014.5  959.93  5054.9  964.11  5060.4  963.47  5081.7  964.09  5094.6  964.98
  5160.9  976.79  5165.9  977.88  5168.4  978.46  5170.3  978.62    5219  987.77
  5251.9  994.71  5273.8  993.57
#Mann= 3 ,-1,0
  4513.4    .135       0    4988     .05       0    5012     .15       0
#XS Ineff= 2 , 0
       0    4939  971.77    5061       0   969.8
Permanent Ineff=
       F       F
Bank Sta=4988,5012
XS Rating Curve= 0 ,0
Exp/Cntr=0.5,0.3

Type RM Length L Ch R = 1 ,50950   ,111,111,111
BEGIN DESCRIPTION:
Georges Creek 102.0
END DESCRIPTION:
XS GIS Cut Line= 4
      1520768.34      1099298.05      1520939.25      1099067.47
      1521000.45       1098984.7      1521117.89      1098771.37
#Sta/Elev= 24
  4612.1  952.18  4642.6  953.57    4795  947.53  4817.1  946.05  4847.1  945.96
  4906.6  942.79    4940  938.84    4950  936.92  4983.5   936.7  4990.1   932.7
  5009.9   932.7  5016.5   936.7  5027.8  937.97  5032.4  938.71    5075  938.84
  5084.1  939.55  5125.8  939.11  5129.1  938.84  5130.7  938.87  5139.5  938.78
  5168.3   936.8  5178.7  935.73  5227.7   946.3  5245.6  946.96
#Mann= 3 ,-1,0
  4612.1     .13       0  4983.5     .05       0  5016.5     .15       0
#XS Ineff= 2 , 0
       0  4934.5  945.07  5065.5       0  951.02
Permanent Ineff=
       F       F
Bank Sta=4983.5,5016.5
XS Rating Curve= 0 ,0
Exp/Cntr=0.5,0.3