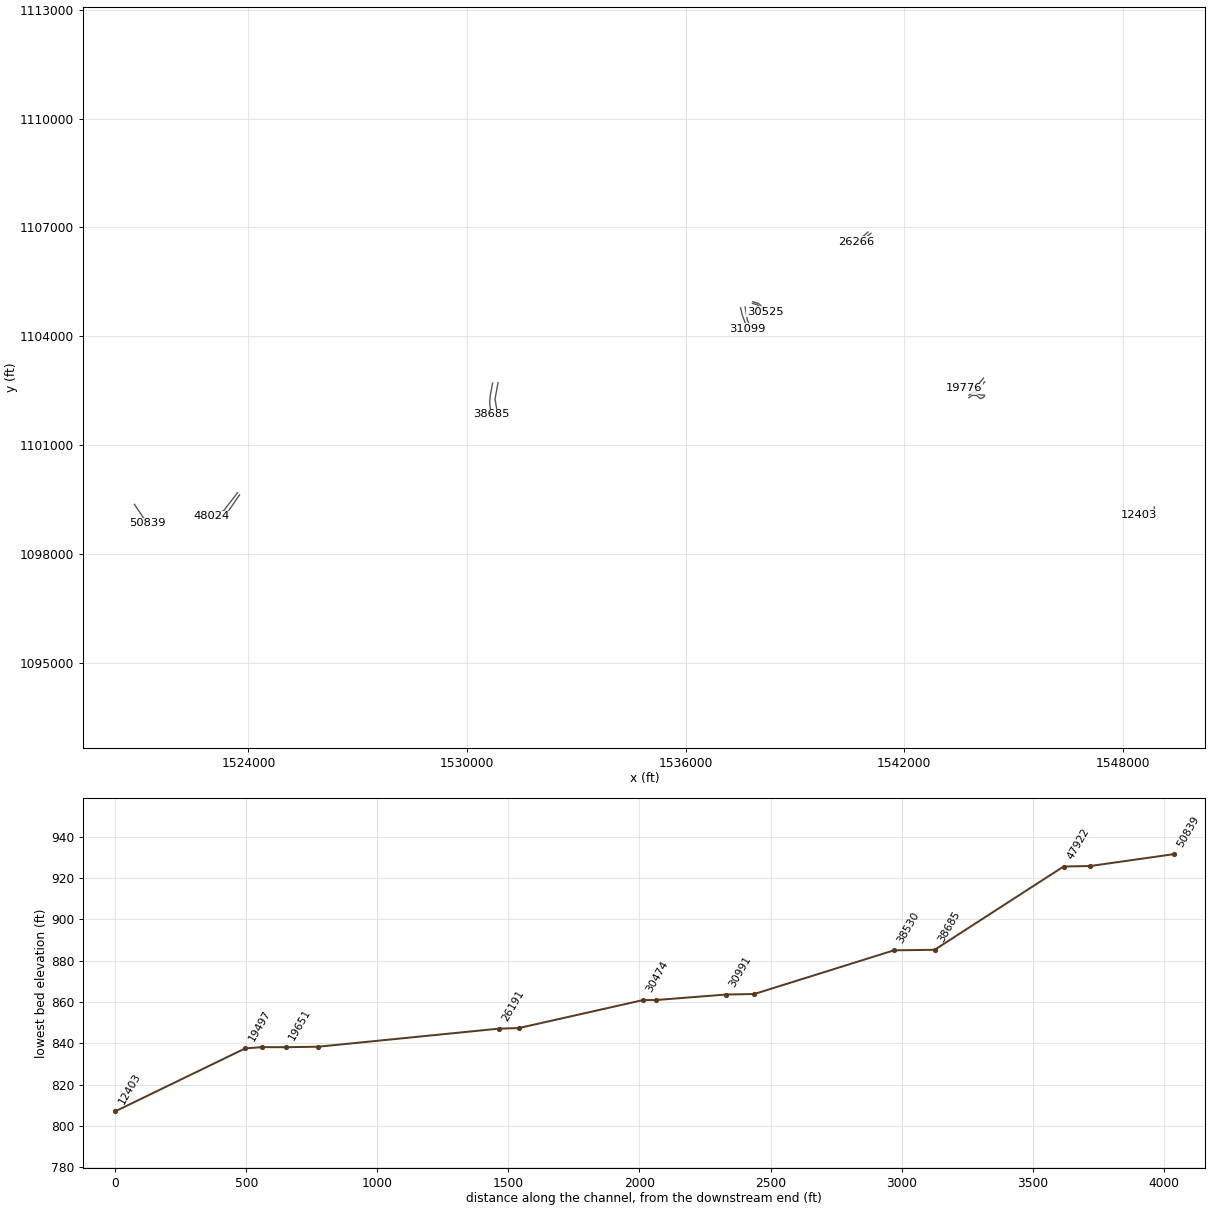
HEC-RAS study GeorgesCreek.prj: Georges Creek Limited Detail Study

--- GeorgesCreek.g01 (geometry) --- (continued)

Type RM Length L Ch R = 3 ,50901   ,,,
BEGIN DESCRIPTION:
Glenwood Rd. (Georges Cr.) - TOR
Structure ID: LDS_GC_12
Approximate Survey Structure
END DESCRIPTION:
Bridge Culvert--1,0,-1,-1, 0
Deck Dist Width WeirC Skew NumUp NumDn MinLoCord MaxHiCord MaxSubmerge Is_Ogee
35.5,27,3,0, 9, 9, , , , 0, 1,1,,
    4635  4766.8  4812.1    4970    4970    5030    5030  5065.6  5291.8
   956.2  949.01  947.72   944.3   944.3   944.3   944.3  951.02  964.88
   912.7   912.7   912.7   912.7   943.3   943.3   912.7   912.7   912.7
    4635  4766.8  4812.1    4970    4970    5030    5030  5065.6  5291.8
   956.2  949.01  947.72   944.3   944.3   944.3   944.3  951.02  964.88
   912.7   912.7   912.7   912.7   943.3   943.3   912.7   912.7   912.7
Pier Skew, UpSta & Num, DnSta & Num=  ,4985, 2 ,4985, 2 , 0 , 0 , 0 ,0,0
       1       1
   939.7   943.3
       1       1
  939.45   943.3
Pier Skew, UpSta & Num, DnSta & Num=  ,5015, 2 ,5015, 2 , 0 , 0 , 0 ,0,0
       1       1
   939.7   943.3
       1       1
  939.45   943.3
Abutment Skew #Up #Dn= , 2 , 2
    4970  4971.5
   943.3  934.28
    4970  4971.5
   943.3  933.51
Abutment Skew #Up #Dn= , 2 , 2
  5028.5    5030
  938.08   943.3
  5028.5    5030
  936.57   943.3
BR Coef= 1 , 1 , 0 ,1.25, 0 ,,,0.8,0,2,0,
WSPro=,,,, 1 ,,,, 0 ,,,, 0 ,,,,-1 ,-1 ,-1 , 0 , 0 , 0 , 0 , 0
BC Design=,, 0 ,, 0 ,,,,,,
BC HTab HWMax=953.57
BC Use User HTab Curves=0
BC User HTab FreeFlow(D)= 0

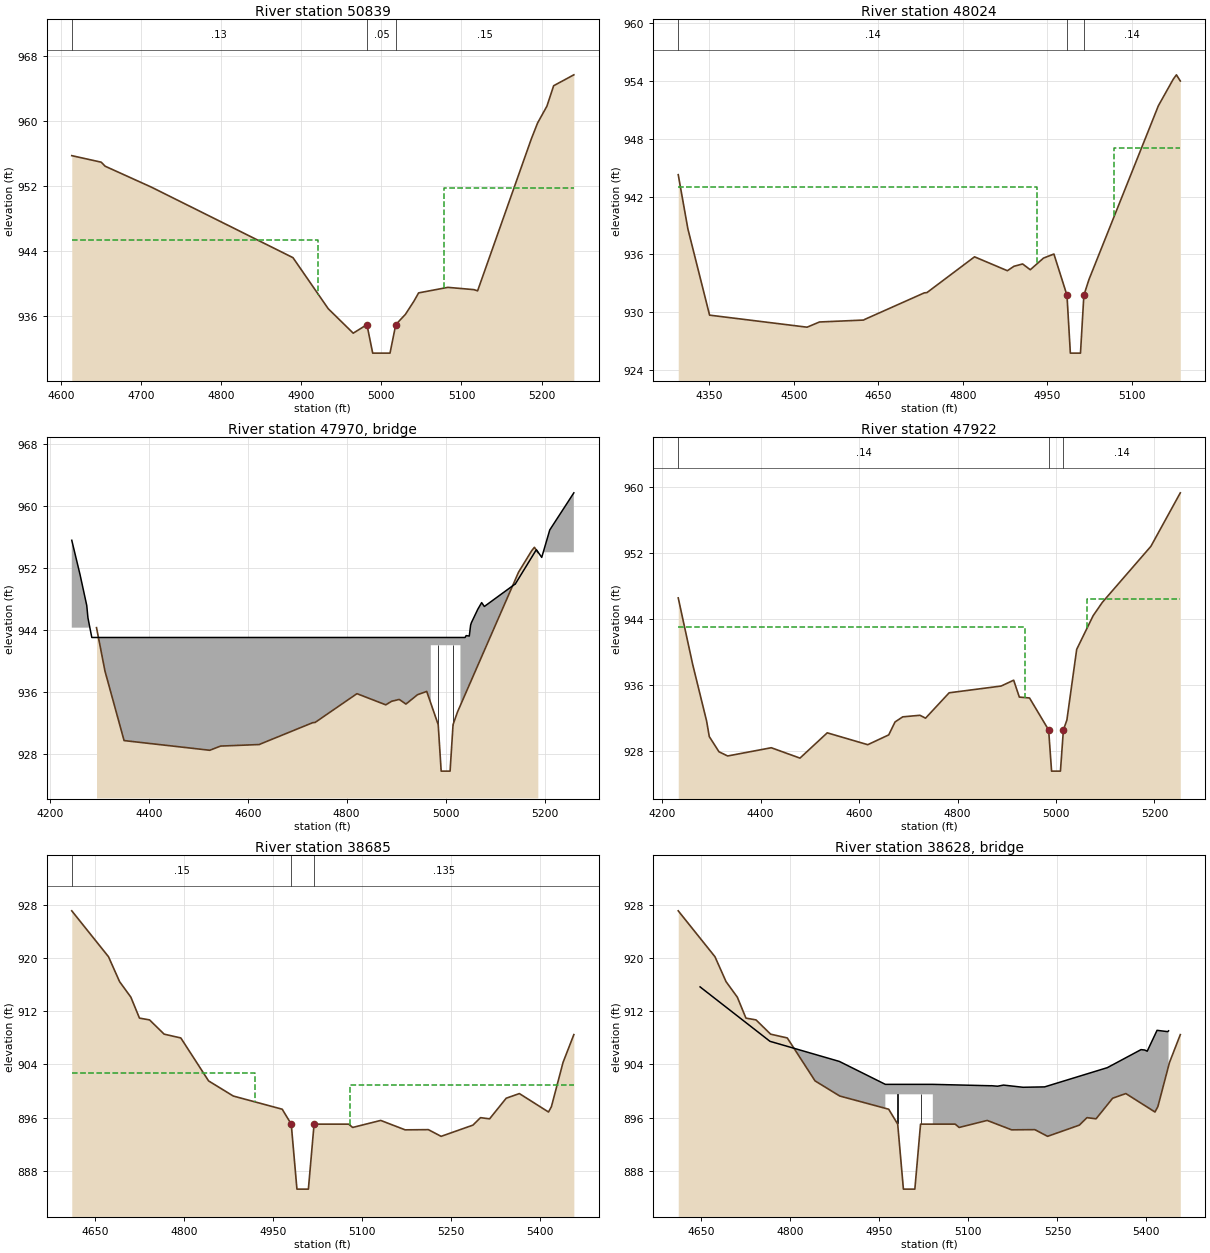
Type RM Length L Ch R = 1 ,50839   ,318,318,318
BEGIN DESCRIPTION:
Georges Creek 101.5
END DESCRIPTION:
XS GIS Cut Line= 3
      1520868.69      1099372.46      1521084.33      1099052.67
      1521214.32      1098849.99
#Sta/Elev= 22
  4613.7  955.75  4650.4  954.95  4655.4  954.45  4712.9  951.89  4889.7  943.22
  4933.7  936.95  4964.9  933.94    4982  934.99  4989.2  931.49  5010.8  931.49
    5018  934.99    5030  936.25  5040.7  937.88  5046.5  938.89    5083  939.57
  5115.5  939.29  5120.1  939.14  5187.3  957.85    5195  959.77  5206.6  961.83
    5215  964.34  5240.2  965.68
#Mann= 3 ,-1,0
  4613.7     .13       0    4982     .05       0    5018     .15       0
#XS Ineff= 2 , 0
       0  4921.5  945.35  5078.5       0  951.81
Permanent Ineff=
       F       F
Bank Sta=4982,5018
XS Rating Curve= 0 ,0
Exp/Cntr=0.5,0.3

Type RM Length L Ch R = 1 ,48024   ,102,102,102
BEGIN DESCRIPTION:
Georges Creek 96.0
END DESCRIPTION:
XS GIS Cut Line= 3
      1523702.06      1099693.97      1523320.26      1099199.64
      1522994.72       1099042.9
#Sta/Elev= 25
  4294.5  944.27  4311.6  938.66  4350.2   929.7  4523.4  928.45  4545.3  928.99
  4623.8  929.19  4625.8  929.26  4731.5  932.01  4736.3  932.04  4820.8  935.75
  4879.1  934.31  4890.9  934.77  4906.2  935.01  4919.8  934.41  4943.3  935.62
  4961.8  936.04    4985  931.76    4991  925.76    5009  925.76    5015  931.76
    5024  933.39  5147.4  951.43  5173.8  954.18  5179.4  954.63  5186.3  953.99
#Mann= 3 ,-1,0
  4294.5     .14       0    4985    .049       0    5015     .14       0
#XS Ineff= 2 , 0
       0    4931     943    5069       0  947.08
Permanent Ineff=
       F       F
Bank Sta=4985,5015
XS Rating Curve= 0 ,0
Exp/Cntr=0.5,0.3

Type RM Length L Ch R = 3 ,47970   ,,,
BEGIN DESCRIPTION:
Jordan Rd. (Georges Cr.) - TOR
Structure ID: Jordan Rd. (Georges Cr.)
Approximate Survey Structure
END DESCRIPTION:
Bridge Culvert--1,0,-1,-1, 0
Deck Dist Width WeirC Skew NumUp NumDn MinLoCord MaxHiCord MaxSubmerge Is_Ogee
39,30,3,0, 24, 24, , , , 0, 1,1,,
  4244.5  4261.3  4274.8  4277.2    4285    4970    4970    5030    5030  5039.2
  5041.5  5047.8  5050.5    5052  5064.9  5072.8  5078.2  5140.1  5140.5  5181.9
  5183.5  5194.2  5210.4  5259.1
  955.54  951.09  947.12  945.53     943     943     943     943     943     943
  943.24  943.19   944.6   944.9  946.63   947.5     947  949.88  949.87  954.18
  954.31  953.33  956.87  961.66
  905.76  905.76  905.76  905.76  905.76  905.76     942     942  905.76  905.76
  905.76  905.76  905.76  905.76  905.76  905.76  905.76  905.76  905.76  905.76
  905.76  905.76  905.76  905.76
  4244.5  4261.3  4274.8  4277.2    4285    4970    4970    5030    5030  5039.2
  5041.5  5047.8  5050.5    5052  5064.9  5072.8  5078.2  5140.1  5140.5  5181.9
  5183.5  5194.2  5210.4  5259.1
  955.54  951.09  947.12  945.53     943     943     943     943     943     943
  943.24  943.19   944.6   944.9  946.63   947.5     947  949.88  949.87  954.18
  954.31  953.33  956.87  961.66
  905.76  905.76  905.76  905.76  905.76  905.76     942     942  905.76  905.76
  905.76  905.76  905.76  905.76  905.76  905.76  905.76  905.76  905.76  905.76
  905.76  905.76  905.76  905.76
Pier Skew, UpSta & Num, DnSta & Num=  ,4985, 2 ,4985, 2 , 0 , 0 , 0 ,0,0
       1       1
     938     942
       1       1
  937.75     942
Pier Skew, UpSta & Num, DnSta & Num=  ,5015, 2 ,5015, 2 , 0 , 0 , 0 ,0,0
       1       1
     938     942
       1       1
  937.75     942
Abutment Skew #Up #Dn= , 2 , 2
    4970  4972.5
     942  936.94
    4970  4972.5
     942  931.59
Abutment Skew #Up #Dn= , 2 , 2
  5027.5    5030
  934.85     942
  5027.5    5030
  934.04     942
BR Coef= 1 , 1 , 0 ,1.25, 0 ,,,0.8,0,2,0,
WSPro=,,,, 1 ,,,, 0 ,,,, 0 ,,,,-1 ,-1 ,-1 , 0 , 0 , 0 , 0 , 0
BC Design=,, 0 ,, 0 ,,,,,,
BC HTab HWMax=954.63
BC Use User HTab Curves=0
BC User HTab FreeFlow(D)= 0

Type RM Length L Ch R = 1 ,47922   ,492,492,492
BEGIN DESCRIPTION:
Georges Creek 95.5
END DESCRIPTION:
XS GIS Cut Line= 3
      1523754.31      1099633.69      1523396.62      1099111.22
      1523034.91      1098974.58
#Sta/Elev= 30
  4232.6  946.54  4261.9  938.48  4290.2   931.6  4295.7   929.7  4315.4  927.86
    4333  927.35  4421.6  928.35  4479.9  927.09  4535.3  930.16  4617.6  928.72
  4660.2  929.91    4673  931.48  4688.6   932.1  4723.6  932.29    4735  931.94
  4782.9  935.02  4888.5  935.84    4914  936.55  4925.5   934.5  4946.2  934.39
    4985  930.51    4991  925.51    5009  925.51    5015  930.51  5022.1  931.71
    5042  940.29  5075.4  944.38  5094.2  946.01  5192.7   952.8  5252.5   959.3
#Mann= 3 ,-1,0
  4232.6     .14       0    4985    .049       0    5015     .14       0
#XS Ineff= 2 , 0
       0    4937     943    5063       0  946.38
Permanent Ineff=
       F       F
Bank Sta=4985,5015
XS Rating Curve= 0 ,0
Exp/Cntr=0.5,0.3

Type RM Length L Ch R = 1 ,38685   ,155,155,155
BEGIN DESCRIPTION:
Georges Creek 78.0
END DESCRIPTION:
XS GIS Cut Line= 4
       1530702.8      1102712.46      1530639.02      1102374.97
      1530623.08      1102157.06       1530665.6      1101859.43
#Sta/Elev= 30
  4610.9  927.17  4672.8  920.25  4691.5  916.49  4710.5  914.15    4725  910.99
    4742  910.72  4766.6  908.57  4794.7     908  4841.5  901.52  4883.1  899.24
  4965.6  897.25  4980.8     895  4990.4   885.2  5009.7   885.2  5019.3     895
  5077.7     895  5084.3   894.5  5131.6  895.56  5172.8  894.14  5211.9  894.17
  5233.4  893.16    5287  894.85  5299.8  895.98  5315.1   895.8  5343.1  898.91
  5365.3  899.61  5414.4  896.83  5419.3  897.64  5438.9  904.31  5457.1   908.5
#Mann= 3 ,-1,0
  4610.9     .15       0  4980.8    .048       0  5019.3    .135       0
#XS Ineff= 2 , 0
       0  4920.5  902.76  5079.5       0  900.92
Permanent Ineff=
       F       F
Bank Sta=4980.8,5019.3
XS Rating Curve= 0 ,0
Exp/Cntr=0.5,0.3

Type RM Length L Ch R = 3 ,38628   ,,,
BEGIN DESCRIPTION:
Grant Valley Rd. - TOR
Structure ID: LDS_GC_11
Approximate Survey Structure
END DESCRIPTION:
Bridge Culvert--1,0,-1,-1, 0
Deck Dist Width WeirC Skew NumUp NumDn MinLoCord MaxHiCord MaxSubmerge Is_Ogee
39.5,35,3,0, 20, 20, , , , 0, 1,1,,
  4647.7  4765.5  4882.4    4960    4960    5040    5040  5137.6  5138.4    5149
  5159.2    5192  5228.4  5334.1  5390.9  5397.1  5401.3  5417.9  5435.8  5437.3
   915.7  907.49  904.46     901     901     901     901  900.79   900.8  900.72
  900.89  900.56  900.62  903.52  906.24  906.18     906  909.15  908.95  909.07
   865.2   865.2   865.2   865.2   899.5   899.5   865.2   865.2   865.2   865.2
   865.2   865.2   865.2   865.2   865.2   865.2   865.2   865.2   865.2   865.2
  4647.7  4765.5  4882.4    4960    4960    5040    5040  5137.6  5138.4    5149
  5159.2    5192  5228.4  5334.1  5390.9  5397.1  5401.3  5417.9  5435.8  5437.3
   915.7  907.49  904.46     901     901     901     901  900.79   900.8  900.72
  900.89  900.56  900.62  903.52  906.24  906.18     906  909.15  908.95  909.07
   865.2   865.2   865.2   865.2   899.5   899.5   865.2   865.2   865.2   865.2
   865.2   865.2   865.2   865.2   865.2   865.2   865.2   865.2   865.2   865.2
Pier Skew, UpSta & Num, DnSta & Num=  ,4980, 2 ,4980, 2 , 0 , 0 , 0 ,0,0
       1       1
  894.37   899.5
       1       1
  889.84   899.5
Pier Skew, UpSta & Num, DnSta & Num=  ,5020, 2 ,5020, 2 , 0 , 0 , 0 ,0,0
       1       1
  896.14   899.5
       1       1
  895.68   899.5
Abutment Skew #Up #Dn= , 2 , 2
    4960    4963
   899.5  897.28
    4960    4963
   899.5  892.74
Abutment Skew #Up #Dn= , 2 , 2
    5037    5040
  895.08   899.5
    5037    5040
  895.04   899.5
BR Coef= 1 , 1 , 0 ,1.25, 0 ,,,0.8,0,2,0,
WSPro=,,,, 1 ,,,, 0 ,,,, 0 ,,,,-1 ,-1 ,-1 , 0 , 0 , 0 , 0 , 0
BC Design=,, 0 ,, 0 ,,,,,,
BC HTab HWMax=927.17
BC Use User HTab Curves=0
BC User HTab FreeFlow(D)= 0

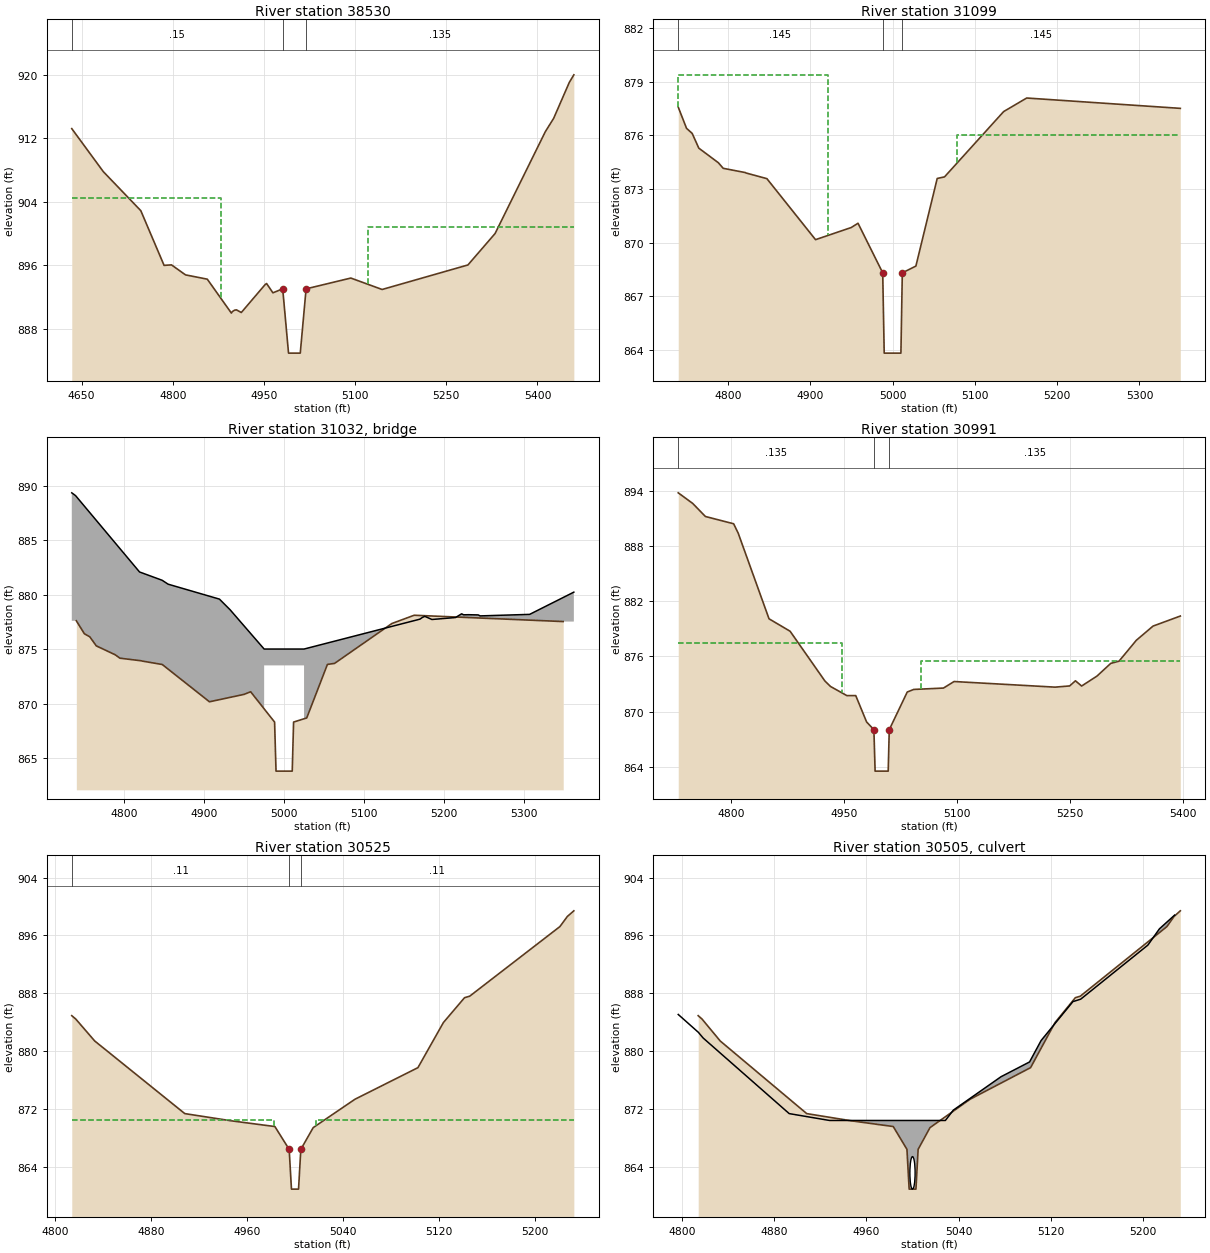
Type RM Length L Ch R = 1 ,38530   ,533,533,533
BEGIN DESCRIPTION:
Georges Creek 77.0
END DESCRIPTION:
XS GIS Cut Line= 3
      1530851.61      1102720.43      1530769.23      1102268.67
      1530833.01      1101907.27
#Sta/Elev= 27
  4633.7  913.24  4685.6  907.82  4747.3   902.9  4785.6  896.01  4797.8  896.07
  4820.9  894.81  4856.7  894.27  4896.3     890  4898.1  890.19  4901.5  890.36
  4904.8   890.4  4912.7  890.07  4951.7  893.57  4954.3  893.72  4964.7  892.55
  4980.8  893.05  4990.4  884.95  5009.7  884.95  5019.3  893.05  5092.9  894.41
  5144.4  892.97  5285.6  896.06  5330.3  900.02    5413  912.86  5426.7  914.54
  5452.4  919.06  5459.9  920.02
#Mann= 3 ,-1,0
  4633.7     .15       0  4980.8    .048       0  5019.3    .135       0
#XS Ineff= 2 , 0
       0  4879.5  904.54  5120.5       0  900.83
Permanent Ineff=
       F       F
Bank Sta=4980.8,5019.3
XS Rating Curve= 0 ,0
Exp/Cntr=0.5,0.3

Type RM Length L Ch R = 1 ,31099   ,108,108,108
BEGIN DESCRIPTION:
Georges Creek 62.5
END DESCRIPTION:
XS GIS Cut Line= 4
      1537511.44      1104787.33      1537558.12      1104582.46
      1537617.76      1104432.05      1537685.18      1104203.85
#Sta/Elev= 22
  4739.7  877.59  4749.8   876.4  4756.6  876.12  4764.7  875.29  4788.5  874.47
  4794.3  874.16  4821.3  873.92  4821.9   873.9  4847.4  873.58  4906.5  870.16
  4949.8  870.84  4958.1  871.08  4988.1   868.3  4989.9   863.8  5010.2   863.8
  5011.9   868.3  5028.4  868.68  5054.3  873.59  5063.2  873.68    5135  877.34
    5163   878.1  5349.6  877.52
#Mann= 3 ,-1,0
  4739.7    .145       0  4988.1    .043       0  5011.9    .145       0
#XS Ineff= 2 , 0
       0  4921.5   879.4  5078.5       0  876.01
Permanent Ineff=
       F       F
Bank Sta=4988.1,5011.9
XS Rating Curve= 0 ,0
Exp/Cntr=0.5,0.3

Type RM Length L Ch R = 3 ,31032   ,,,
BEGIN DESCRIPTION:
Lenhardt Rd. (Georges Cr.) - TOR
Structure ID: LDS_GC_10
Approximate Survey Structure
END DESCRIPTION:
Bridge Culvert--1,0,-1,-1, 0
Deck Dist Width WeirC Skew NumUp NumDn MinLoCord MaxHiCord MaxSubmerge Is_Ogee
53.5,27,3,0, 23, 23, , , , 0, 1,1,,
    4734  4738.8  4818.9  4847.2  4854.7    4919  4932.4    4975    4975    5025
    5025  5170.1  5173.3  5176.3  5185.2  5214.7  5222.4  5224.9  5230.9  5243.2
  5245.6  5307.6    5363
  889.33  889.07  882.07  881.31  880.95  879.58   878.6     875     875     875
     875  877.74   877.9     878  877.71  877.89  878.23  878.14  878.15  878.13
  878.04  878.18  880.22
   843.8   843.8   843.8   843.8   843.8   843.8   843.8   843.8   873.5   873.5
   843.8   843.8   843.8   843.8   843.8   843.8   843.8   843.8   843.8   843.8
   843.8   843.8   843.8
    4734  4738.8  4818.9  4847.2  4854.7    4919  4932.4    4975    4975    5025
    5025  5170.1  5173.3  5176.3  5185.2  5214.7  5222.4  5224.9  5230.9  5243.2
  5245.6  5307.6    5363
  889.33  889.07  882.07  881.31  880.95  879.58   878.6     875     875     875
     875  877.74   877.9     878  877.71  877.89  878.23  878.14  878.15  878.13
  878.04  878.18  880.22
   843.8   843.8   843.8   843.8   843.8   843.8   843.8   843.8   873.5   873.5
   843.8   843.8   843.8   843.8   843.8   843.8   843.8   843.8   843.8   843.8
   843.8   843.8   843.8
Abutment Skew #Up #Dn= , 2 , 2
    4975    4976
   873.5  868.34
    4975    4976
   873.5   869.7
Abutment Skew #Up #Dn= , 2 , 2
    5024    5025
  869.26   873.5
    5024    5025
  869.02   873.5
BR Coef= 1 , 1 , 0 ,1.25, 0 ,,,0.8,0,2,0,
WSPro=,,,, 1 ,,,, 0 ,,,, 0 ,,,,-1 ,-1 ,-1 , 0 , 0 , 0 , 0 , 0
BC Design=,, 0 ,, 0 ,,,,,,
BC HTab HWMax=878.1
BC Use User HTab Curves=0
BC User HTab FreeFlow(D)= 0

Type RM Length L Ch R = 1 ,30991   ,266,266,266
BEGIN DESCRIPTION:
Georges Creek 62.0
END DESCRIPTION:
XS GIS Cut Line= 5
      1537635.91      1104808.08      1537685.18      1104538.38
      1537695.56      1104457.99      1537752.61      1104325.73
      1537858.93      1104196.07
#Sta/Elev= 30
  4729.9  893.77  4749.1  892.62    4766   891.2  4803.5  890.41  4809.6  889.38
  4850.5  880.09  4878.5  878.74  4924.8  873.33  4932.2  872.74  4953.9  871.75
  4965.7  871.75  4980.1  868.89  4989.8  868.05  4991.4  863.55  5008.8  863.55
  5010.2  868.05  5034.1  872.14  5042.7  872.42  5082.2  872.57  5096.3  873.28
  5230.4  872.67  5249.8   872.8  5257.5  873.36  5265.7  872.79  5286.1  873.87
  5304.4  875.25  5315.4  875.49  5338.4  877.76  5360.6   879.3  5396.8  880.39
#Mann= 3 ,-1,0
  4729.9    .135       0  4989.8    .043       0  5010.2    .135       0
#XS Ineff= 2 , 0
       0  4947.5  877.43  5052.5       0  875.52
Permanent Ineff=
       F       F
Bank Sta=4989.8,5010.2
XS Rating Curve= 0 ,0
Exp/Cntr=0.5,0.3

Type RM Length L Ch R = 1 ,30525   ,51,51,51
BEGIN DESCRIPTION:
Georges Creek 61.0
END DESCRIPTION:
XS GIS Cut Line= 3
      1537836.79      1104908.74      1537964.57      1104870.75
      1538179.25      1104683.78
#Sta/Elev= 19
  4814.2   884.9  4817.5  884.44  4833.3   881.4  4908.3  871.35  4947.5  870.34
  4983.3  869.56  4995.2   866.4  4997.1   860.9    5003   860.9  5004.9   866.4
  5015.2  869.41    5050  873.34  5102.4  877.71  5123.6  883.95  5141.2  887.39
  5145.5   887.6  5220.6  897.23  5226.8  898.63  5232.2  899.41
#Mann= 3 ,-1,0
  4814.2     .11       0  4995.2    .041       0  5004.9     .11       0
#XS Ineff= 2 , 0
       0  4982.8   870.4  5017.3       0   870.4
Permanent Ineff=
       F       F
Bank Sta=4995.2,5004.9
XS Rating Curve= 0 ,0
Exp/Cntr=0.5,0.3

Type RM Length L Ch R = 2 ,30505   ,,,
BEGIN DESCRIPTION:
Unnamed Trail (Georges Cr.) - TOR
Structure ID: Unnamed Trail (Georges Cr.)
Approximate Survey Structure
END DESCRIPTION:
Bridge Culvert--1,0,-1,-1, 0
Deck Dist Width WeirC Skew NumUp NumDn MinLoCord MaxHiCord MaxSubmerge Is_Ogee
15,10,3,0, 15, 15, , , , 0, 1,1,,
  4796.9  4814.4  4818.5  4893.1  4928.1  5028.5  5035.4  5076.7  5101.5  5111.5
  5139.1  5145.8  5204.1  5214.1  5227.3
  885.07  882.59  881.81  871.35   870.4   870.4  871.83  876.45   878.5  881.46
  886.85  887.18  894.67  896.92  898.82
   840.9   840.9   840.9   840.9   840.9   840.9   840.9   840.9   840.9   840.9
   840.9   840.9   840.9   840.9   840.9
  4796.9  4814.4  4818.5  4893.1  4928.1  5028.5  5035.4  5076.7  5101.5  5111.5
  5139.1  5145.8  5204.1  5214.1  5227.3
  885.07  882.59  881.81  871.35   870.4   870.4  871.83  876.45   878.5  881.46
  886.85  887.18  894.67  896.92  898.82
  840.85  840.85  840.85  840.85  840.85  840.85  840.85  840.85  840.85  840.85
  840.85  840.85  840.85  840.85  840.85
Culvert=1,4.5,,10,0.015,0.4,1,1,3,860.9,5000,860.85,5000,Culvert #1  , 0 ,15
    5000    5000
BC Culvert Barrel=1,,0
Culvert Bottom n=0.015
BC Design=,, 0 ,, 0 ,,,,,,
BC HTab HWMax=899.41
BC Use User HTab Curves=0
BC User HTab FreeFlow(D)= 0

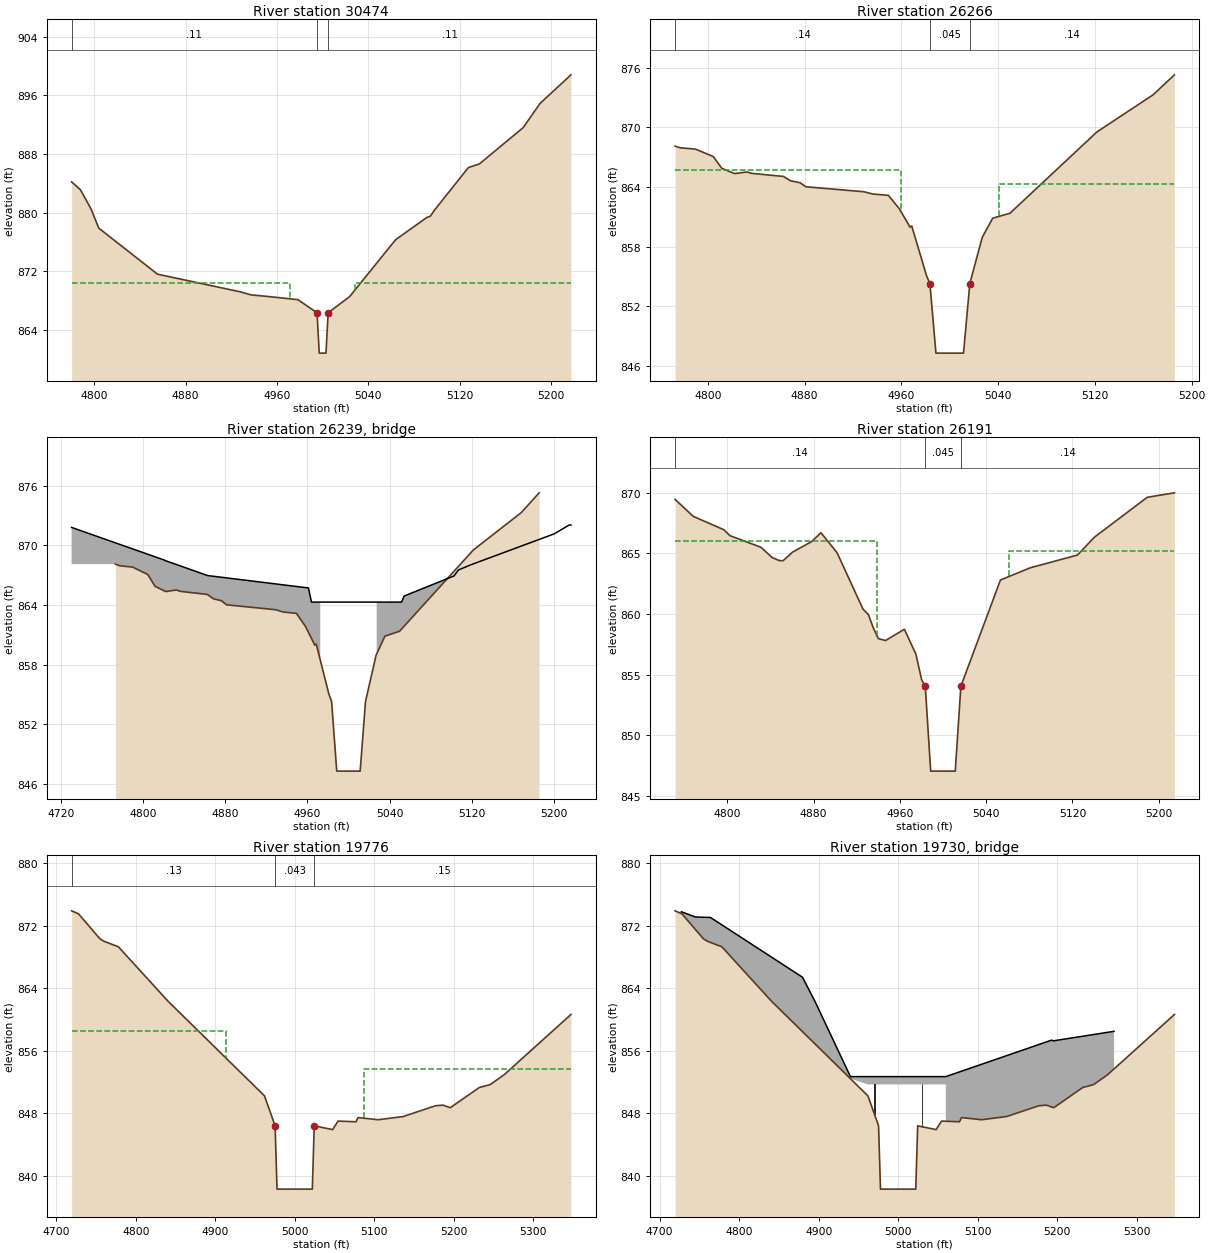
Type RM Length L Ch R = 1 ,30474   ,474,474,474
BEGIN DESCRIPTION:
Georges Creek 60.5
END DESCRIPTION:
XS GIS Cut Line= 3
      1537848.87      1104955.36      1538006.01      1104901.83
       1538204.6      1104717.06
#Sta/Elev= 25
  4780.3  884.21    4788  883.14  4797.2  880.55  4804.1   877.9  4855.5  871.62
  4926.9  869.25  4927.3  869.25  4937.4  868.79  4946.3  868.67  4978.4  868.15
  4995.2  866.35  4997.1  860.85    5003  860.85  5004.9  866.35  5023.7  868.56
    5064  876.33  5091.4  879.37  5094.1   879.5  5096.3  879.95  5097.5  880.26
  5127.7  886.17  5137.3  886.66  5175.7  891.62  5190.4  894.91  5217.5  898.82
#Mann= 3 ,-1,0
  4780.3     .11       0  4995.2    .042       0  5004.9     .11       0
#XS Ineff= 2 , 0
       0  4971.8   870.4  5028.3       0   870.4
Permanent Ineff=
       F       F
Bank Sta=4995.2,5004.9
XS Rating Curve= 0 ,0
Exp/Cntr=0.5,0.3

Type RM Length L Ch R = 1 ,26266   ,75,75,75
BEGIN DESCRIPTION:
Georges Creek 52.5
END DESCRIPTION:
XS GIS Cut Line= 4
       1541012.9      1106874.98      1540838.95      1106725.88
      1540761.64      1106665.14      1540696.16      1106610.43
#Sta/Elev= 29
    4773  868.12  4777.3  867.95  4789.8  867.82  4804.6  867.07  4811.6  865.89
  4822.1  865.36  4832.5  865.52  4836.2  865.38  4862.6  865.07  4868.5  864.63
  4876.3  864.44  4881.2  864.03  4929.2  863.53  4936.5   863.3  4949.3  863.17
  4958.4  861.81  4967.2  859.97  4968.6  860.09  4980.9  855.06  4983.6   854.3
  4988.6   847.3  5011.4   847.3  5016.6   854.3  5026.9  858.95  5035.5  860.87
  5049.8  861.37  5121.7  869.55  5168.2  873.29  5185.7  875.29
#Mann= 3 ,-1,0
    4773     .14       0  4983.6    .045       0  5016.6     .14       0
#XS Ineff= 2 , 0
       0  4959.5  865.75  5040.5       0   864.3
Permanent Ineff=
       F       F
Bank Sta=4983.6,5016.6
XS Rating Curve= 0 ,0
Exp/Cntr=0.5,0.3

Type RM Length L Ch R = 3 ,26239   ,,,
BEGIN DESCRIPTION:
Norman Dr. (Georges Cr.) - TOR
Structure ID: LDS_GC_09
Approximate Survey Structure
END DESCRIPTION:
Bridge Culvert--1,0,-1,-1, 0
Deck Dist Width WeirC Skew NumUp NumDn MinLoCord MaxHiCord MaxSubmerge Is_Ogee
13,28,3,0, 19, 19, , , , 0, 1,1,,
  4730.4  4820.9  4821.2  4862.8  4958.1    4961    4964  4972.5  4972.5  5027.5
  5027.5  5051.7  5054.2  5102.8    5107  5118.6  5200.3  5215.1  5216.7
  871.81  868.52  868.49  866.97  865.76  865.73   864.3   864.3   864.3   864.3
   864.3   864.3  864.91  866.93  867.52  868.03  871.16  872.06  872.05
   827.3   827.3   827.3   827.3   827.3   827.3   827.3   827.3   864.3   864.3
   827.3   827.3   827.3   827.3   827.3   827.3   827.3   827.3   827.3
  4730.4  4820.9  4821.2  4862.8  4958.1    4961    4964  4972.5  4972.5  5027.5
  5027.5  5051.7  5054.2  5102.8    5107  5118.6  5200.3  5215.1  5216.7
  871.81  868.52  868.49  866.97  865.76  865.73   864.3   864.3   864.3   864.3
   864.3   864.3  864.91  866.93  867.52  868.03  871.16  872.06  872.05
   827.3   827.3   827.3   827.3   827.3   827.3   827.3   827.3   864.3   864.3
   827.3   827.3   827.3   827.3   827.3   827.3   827.3   827.3   827.3
Abutment Skew #Up #Dn= , 2 , 2
  4972.5  4974.5
   864.3  857.68
  4972.5  4974.5
   864.3  856.78
Abutment Skew #Up #Dn= , 2 , 2
  5025.5  5027.5
  859.09   864.3
  5025.5  5027.5
  857.65   864.3
BR Coef= 1 , 1 , 0 ,1.25, 0 ,,,0.8,0,2,0,
WSPro=,,,, 1 ,,,, 0 ,,,, 0 ,,,,-1 ,-1 ,-1 , 0 , 0 , 0 , 0 , 0
BC Design=,, 0 ,, 0 ,,,,,,
BC HTab HWMax=875.29
BC Use User HTab Curves=0
BC User HTab FreeFlow(D)= 0

Type RM Length L Ch R = 1 ,26191   ,689,689,689
BEGIN DESCRIPTION:
Georges Creek 52.0
END DESCRIPTION:
XS GIS Cut Line= 4
      1541090.77      1106838.05      1540946.04      1106715.58
       1540834.7      1106631.46      1540741.93      1106534.98
#Sta/Elev= 30
  4751.6  869.46  4768.4  868.06  4796.8  866.96  4802.4  866.47  4831.2  865.51
  4841.7  864.66    4848  864.42  4851.7   864.4  4860.5  865.11  4878.2  865.98
  4886.9  866.71  4901.8  865.06  4925.8  860.42  4930.9  859.95  4935.2  858.91
    4940  857.98  4946.8  857.82  4964.2  858.75  4974.9   856.7  4980.2  854.59
  4983.6  854.05  4988.6  847.05  5011.4  847.05  5016.6  854.05  5053.3  862.81
  5080.7  863.81  5124.7  864.87  5140.4  866.34  5189.4  869.63  5214.6     870
#Mann= 3 ,-1,0
  4751.6     .14       0  4983.6    .045       0  5016.6     .14       0
#XS Ineff= 2 , 0
       0  4938.5  866.01  5061.5       0  865.21
Permanent Ineff=
       F       F
Bank Sta=4983.6,5016.6
XS Rating Curve= 0 ,0
Exp/Cntr=0.5,0.3

Type RM Length L Ch R = 1 ,19776   ,125,125,125
BEGIN DESCRIPTION:
Georges Creek 39.9
END DESCRIPTION:
XS GIS Cut Line= 4
       1544180.9      1102851.99      1544029.03      1102662.86
      1543920.04      1102613.45      1543658.46      1102565.49
#Sta/Elev= 25
  4719.4  873.92    4728  873.54  4755.1  870.33  4760.6     870  4778.2  869.32
  4840.7  862.35    4962  850.24  4975.4   846.4  4977.8   838.3  5022.2   838.3
  5024.6   846.4  5047.8  845.92  5054.6  847.01  5077.2  846.92  5079.7  847.44
  5081.6  847.44    5105  847.18  5136.5  847.59  5177.1  848.97  5186.5  849.05
  5195.8  848.72  5232.2   851.3    5246  851.68  5263.4  852.93  5347.6  860.65
#Mann= 3 ,-1,0
  4719.4     .13       0  4975.4    .043       0  5024.6     .15       0
#XS Ineff= 2 , 0
       0    4913  858.53    5087       0  853.65
Permanent Ineff=
       F       F
Bank Sta=4975.4,5024.6
XS Rating Curve= 0 ,0
Exp/Cntr=0.5,0.3

Type RM Length L Ch R = 3 ,19730   ,,,
BEGIN DESCRIPTION:
Saluda Dam Rd. - TOR
Structure ID: LDS_GC_08
Approximate Survey Structure
END DESCRIPTION:
Bridge Culvert--1,0,-1,-1, 0
Deck Dist Width WeirC Skew NumUp NumDn MinLoCord MaxHiCord MaxSubmerge Is_Ogee
27,38,3,0, 13, 13, , , , 0, 1,1,,
  4727.3    4745  4763.9  4879.7    4894  4895.4    4940    4940    5060    5060
  5193.1  5195.4  5271.7
   873.8  873.13  873.07  865.42   862.6  862.33   852.7   852.7   852.7   852.7
  857.37  857.28   858.5
   818.3   818.3   818.3   818.3   818.3   818.3   818.3   851.7   851.7   818.3
   818.3   818.3   818.3
  4727.3    4745  4763.9  4879.7    4894  4895.4    4940    4940    5060    5060
  5193.1  5195.4  5271.7
   873.8  873.13  873.07  865.42   862.6  862.33   852.7   852.7   852.7   852.7
  857.37  857.28   858.5
   818.3   818.3   818.3   818.3   818.3   818.3   818.3   851.7   851.7   818.3
   818.3   818.3   818.3
Pier Skew, UpSta & Num, DnSta & Num=  ,4970, 2 ,4970, 2 , 0 , 0 , 0 ,0,0
       1       1
  850.77   851.7
       1       1
   839.9   851.7
Pier Skew, UpSta & Num, DnSta & Num=  ,5030, 2 ,5030, 2 , 0 , 0 , 0 ,0,0
       1       1
  849.49   851.7
       1       1
  848.87   851.7
Abutment Skew #Up #Dn= , 2 , 2
    4940    4941
   851.7  854.79
    4940    4941
   851.7  844.04
Abutment Skew #Up #Dn= , 2 , 2
    5059    5060
  846.99   851.7
    5059    5060
  846.33   851.7
BR Coef= 1 , 1 , 0 ,1.25, 0 ,,,0.8,0,2,0,
WSPro=,,,, 1 ,,,, 0 ,,,, 0 ,,,,-1 ,-1 ,-1 , 0 , 0 , 0 , 0 , 0
BC Design=,, 0 ,, 0 ,,,,,,
BC HTab HWMax=873.92
BC Use User HTab Curves=0
BC User HTab FreeFlow(D)= 0

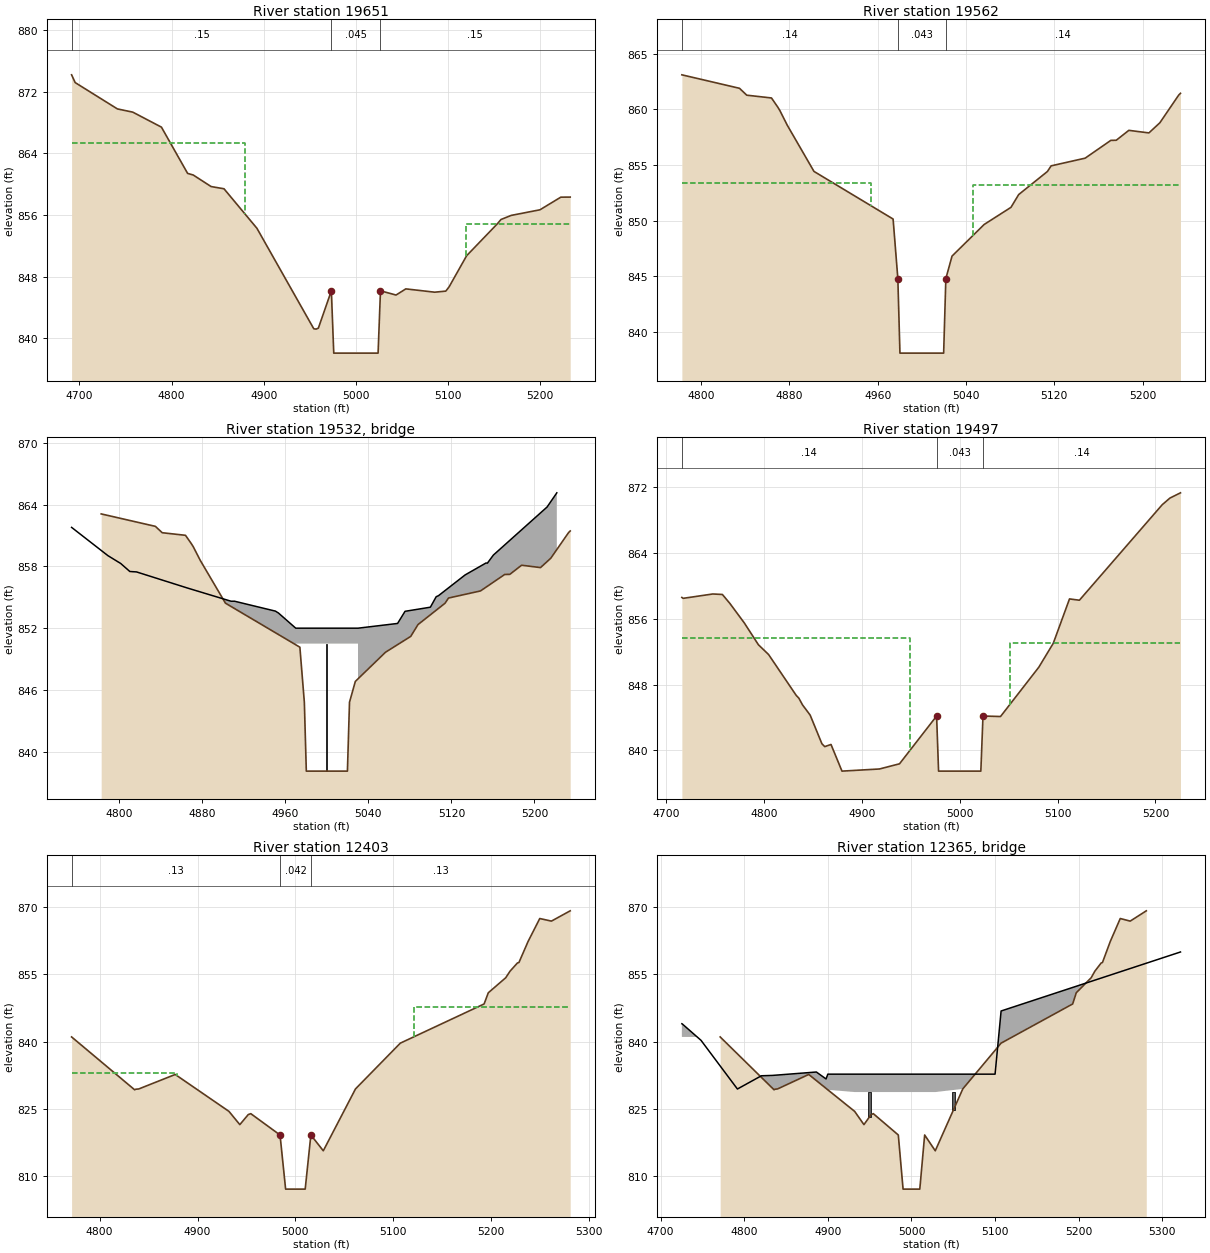
Type RM Length L Ch R = 1 ,19651   ,89,89,89
BEGIN DESCRIPTION:
Georges Creek 39.6
END DESCRIPTION:
XS GIS Cut Line= 5
      1544216.64      1102750.74       1544127.3      1102643.53
      1544029.02      1102536.32      1543939.68      1102473.78
       1543802.7      1102420.18
#Sta/Elev= 29
  4691.5  874.22  4695.4  873.21  4741.2  869.79  4757.9  869.37    4789  867.42
  4817.4  861.41  4823.5   861.2  4842.9   859.7  4856.9  859.41  4892.6  854.28
  4954.3  841.22  4956.8  841.17  4959.3   841.3  4973.4  846.15    4976  838.05
  5024.1  838.05  5026.7  846.15  5043.6   845.6  5054.2   846.4  5085.5  845.97
  5097.6  846.11  5101.2  846.67  5120.2  850.71  5153.7  854.88  5157.5  855.42
  5168.6  855.95  5199.8  856.68  5222.4  858.32  5232.6  858.33
#Mann= 3 ,-1,0
  4691.5     .15       0  4973.4    .045       0  5026.7     .15       0
#XS Ineff= 2 , 0
       0    4880  865.36    5120       0  854.81
Permanent Ineff=
       F       F
Bank Sta=4973.4,5026.7
XS Rating Curve= 0 ,0
Exp/Cntr=0.5,0.3

Type RM Length L Ch R = 1 ,19562   ,65,65,65
BEGIN DESCRIPTION:
Georges Creek 39.3
END DESCRIPTION:
XS GIS Cut Line= 6
      1544201.75      1102381.47      1544106.45      1102384.44
      1544023.07      1102420.18      1543972.44      1102449.96
      1543886.08      1102446.98      1543784.83      1102381.47
#Sta/Elev= 27
  4782.6  863.11  4834.8   861.9  4841.4  861.28  4863.8  861.03  4869.5  860.21
  4871.4   859.9    4878   858.6  4902.3  854.43    4974  850.15  4978.3   844.8
  4980.2   838.1  5019.8   838.1  5021.8   844.8  5027.4  846.82  5056.5  849.66
  5080.8   851.2  5087.8  852.35  5113.8  854.42  5117.2  854.93    5148  855.62
  5171.3  857.22  5176.2  857.23  5187.6  858.12  5205.8  857.89  5215.7   858.8
  5232.8  861.29  5234.4  861.45
#Mann= 3 ,-1,0
  4782.6     .14       0  4978.3    .043       0  5021.8     .14       0
#XS Ineff= 2 , 0
       0    4954  853.42    5046       0   853.2
Permanent Ineff=
       F       F
Bank Sta=4978.3,5021.8
XS Rating Curve= 0 ,0
Exp/Cntr=0.5,0.3

Type RM Length L Ch R = 3 ,19532   ,,,
BEGIN DESCRIPTION:
Old Saluda Dam Rd. - TOR
Structure ID: LDS_GC_07
Approximate Survey Structure
END DESCRIPTION:
Bridge Culvert--1,0,-1,-1, 0
Deck Dist Width WeirC Skew NumUp NumDn MinLoCord MaxHiCord MaxSubmerge Is_Ogee
16,28,3,0, 25, 25, , , , 0, 1,1,,
  4754.1  4789.1  4801.4  4810.2  4816.6  4865.8  4907.7  4911.1  4950.4  4953.3
    4970    4970    5030    5030  5068.1  5075.3  5099.7  5105.3  5107.5  5133.2
  5153.3  5154.6  5160.4  5212.1  5221.5
   861.8  859.05  858.29  857.51  857.47   855.9  854.62  854.62  853.66  853.48
     852     852     852     852  852.46  853.64  854.04  855.06  855.16  857.18
  858.34  858.32  859.11  863.78  865.16
   818.1   818.1   818.1   818.1   818.1   818.1   818.1   818.1   818.1   818.1
   818.1   850.5   850.5   818.1   818.1   818.1   818.1   818.1   818.1   818.1
   818.1   818.1   818.1   818.1   818.1
  4754.1  4789.1  4801.4  4810.2  4816.6  4865.8  4907.7  4911.1  4950.4  4953.3
    4970    4970    5030    5030  5068.1  5075.3  5099.7  5105.3  5107.5  5133.2
  5153.3  5154.6  5160.4  5212.1  5221.5
   861.8  859.05  858.29  857.51  857.47   855.9  854.62  854.62  853.66  853.48
     852     852     852     852  852.46  853.64  854.04  855.06  855.16  857.18
  858.34  858.32  859.11  863.78  865.16
   818.1   818.1   818.1   818.1   818.1   818.1   818.1   818.1   818.1   818.1
   818.1   850.5   850.5   818.1   818.1   818.1   818.1   818.1   818.1   818.1
   818.1   818.1   818.1   818.1   818.1
Pier Skew, UpSta & Num, DnSta & Num=  ,5000, 2 ,5000, 2 , 0 , 0 , 0 ,0,0
       1       1
   838.1   850.5
       1       1
  837.85   850.5
Abutment Skew #Up #Dn= , 2 , 2
    4970    4971
   850.5  852.14
    4970    4971
   850.5  846.04
Abutment Skew #Up #Dn= , 2 , 2
    5029    5030
  846.98   850.5
    5029    5030
  844.37   850.5
BR Coef= 1 , 1 , 0 ,1.25, 0 ,,,0.8,0,2,0,
WSPro=,,,, 1 ,,,, 0 ,,,, 0 ,,,,-1 ,-1 ,-1 , 0 , 0 , 0 , 0 , 0
BC Design=,, 0 ,, 0 ,,,,,,
BC HTab HWMax=863.11
BC Use User HTab Curves=0
BC User HTab FreeFlow(D)= 0

Type RM Length L Ch R = 1 ,19497   ,496,496,496
BEGIN DESCRIPTION:
Georges Creek 39.0
END DESCRIPTION:
XS GIS Cut Line= 6
      1544213.59      1102354.77      1544155.46      1102302.46
      1544092.97      1102285.02       1543992.7      1102372.21
      1543868.21      1102372.53      1543778.87      1102309.99
#Sta/Elev= 30
  4716.1   858.6  4717.4  858.49  4747.7  859.02  4757.5  858.96  4765.1  857.88
  4779.9   855.5  4794.3  852.85  4804.7  851.66    4833  846.68  4835.6  846.36
  4839.4  845.53  4847.2  844.29  4859.2  840.81  4862.1  840.46  4868.5  840.72
  4879.7  837.48    4918  837.74  4938.5  838.37  4976.4  844.18  4978.4  837.48
  5021.6  837.48  5023.8  844.18  5041.7  844.12  5080.8  850.11  5095.6  853.02
  5112.2  858.42  5122.3  858.26  5206.9  869.87  5214.8  870.68  5225.6  871.32
#Mann= 3 ,-1,0
  4716.1     .14       0  4976.4    .043       0  5023.8     .14       0
#XS Ineff= 2 , 0
       0    4949  853.69    5051       0  853.03
Permanent Ineff=
       F       F
Bank Sta=4976.4,5023.8
XS Rating Curve= 0 ,0
Exp/Cntr=0.5,0.3

Type RM Length L Ch R = 1 ,12403   ,135,135,135
BEGIN DESCRIPTION:
Georges Creek 25.0
END DESCRIPTION:
XS GIS Cut Line= 4
      1548874.08      1099301.55      1548869.72      1099236.16
      1548729.24      1099166.94      1548452.64      1099089.38
#Sta/Elev= 26
  4771.3  841.02  4835.7  829.21  4836.9  829.33  4839.9  829.39  4877.2  832.63
  4932.1  824.38  4943.2  821.42  4951.8  823.66  4954.4  823.87  4984.3   819.1
    4990     807    5010     807  5015.8   819.1  5028.5  815.57  5061.4   829.4
  5107.2  839.63  5192.8  848.39  5197.1  850.89  5214.9  854.25  5219.4  855.74
  5226.9  857.56  5228.4  857.65  5237.8  862.38  5249.7  867.49  5261.6  866.91
  5280.8  869.21
#Mann= 3 ,-1,0
  4771.3     .13       0  4984.3    .042       0  5015.8     .13       0
#XS Ineff= 2 , 0
       0    4879  833.07    5121       0  847.67
Permanent Ineff=
       F       F
Bank Sta=4984.3,5015.8
XS Rating Curve= 0 ,0
Exp/Cntr=0.5,0.3

Type RM Length L Ch R = 3 ,12365   ,,,
BEGIN DESCRIPTION:
Latham Rd. (Georges Cr.) - TOR
Structure ID: LDS_GC_06
Approximate Survey Structure
END DESCRIPTION:
Bridge Culvert--1,0,-1,-1, 0
Deck Dist Width WeirC Skew NumUp NumDn MinLoCord MaxHiCord MaxSubmerge Is_Ogee
21,34,3,0, 14, 14, , , , 0, 1,1,,
  4725.5  4725.9  4748.4  4791.9  4820.6  4833.9  4886.3  4897.9    4900    4900
    5100    5100  5107.2  5321.7
  843.97  843.94  840.26  829.38  832.34  832.42  833.18  831.63   832.7   832.7
   832.7   832.7  846.82  860.01
     787     787     787     787     787     787     787     787     787   828.7
   828.7     787     787     787
  4725.5  4725.9  4748.4  4791.9  4820.6  4833.9  4886.3  4897.9    4900    4900
    5100    5100  5107.2  5321.7
  843.97  843.94  840.26  829.38  832.34  832.42  833.18  831.63   832.7   832.7
   832.7   832.7  846.82  860.01
     787     787     787     787     787     787     787     787     787   828.7
   828.7     787     787     787
Pier Skew, UpSta & Num, DnSta & Num=  ,4950, 2 ,4950, 2 , 0 , 0 , 0 ,0,0
       4       4
  823.19   828.7
       4       4
  817.34   828.7
Pier Skew, UpSta & Num, DnSta & Num=  ,5050, 2 ,5050, 2 , 0 , 0 , 0 ,0,0
       4       4
  824.61   828.7
       4       4
  824.69   828.7
Abutment Skew #Up #Dn= , 2 , 2
    4900    4910
   828.7   827.7
    4900    4910
   828.7  822.29
Abutment Skew #Up #Dn= , 2 , 2
    5090    5100
  839.88   828.7
    5090    5100
  831.64   828.7
BR Coef= 1 , 1 , 0 ,1.25, 0 ,,,0.8,0,2,0,
WSPro=,,,, 1 ,,,, 0 ,,,, 0 ,,,,-1 ,-1 ,-1 , 0 , 0 , 0 , 0 , 0
BC Design=,, 0 ,, 0 ,,,,,,
BC HTab HWMax=869.21
BC Use User HTab Curves=0
BC User HTab FreeFlow(D)= 0