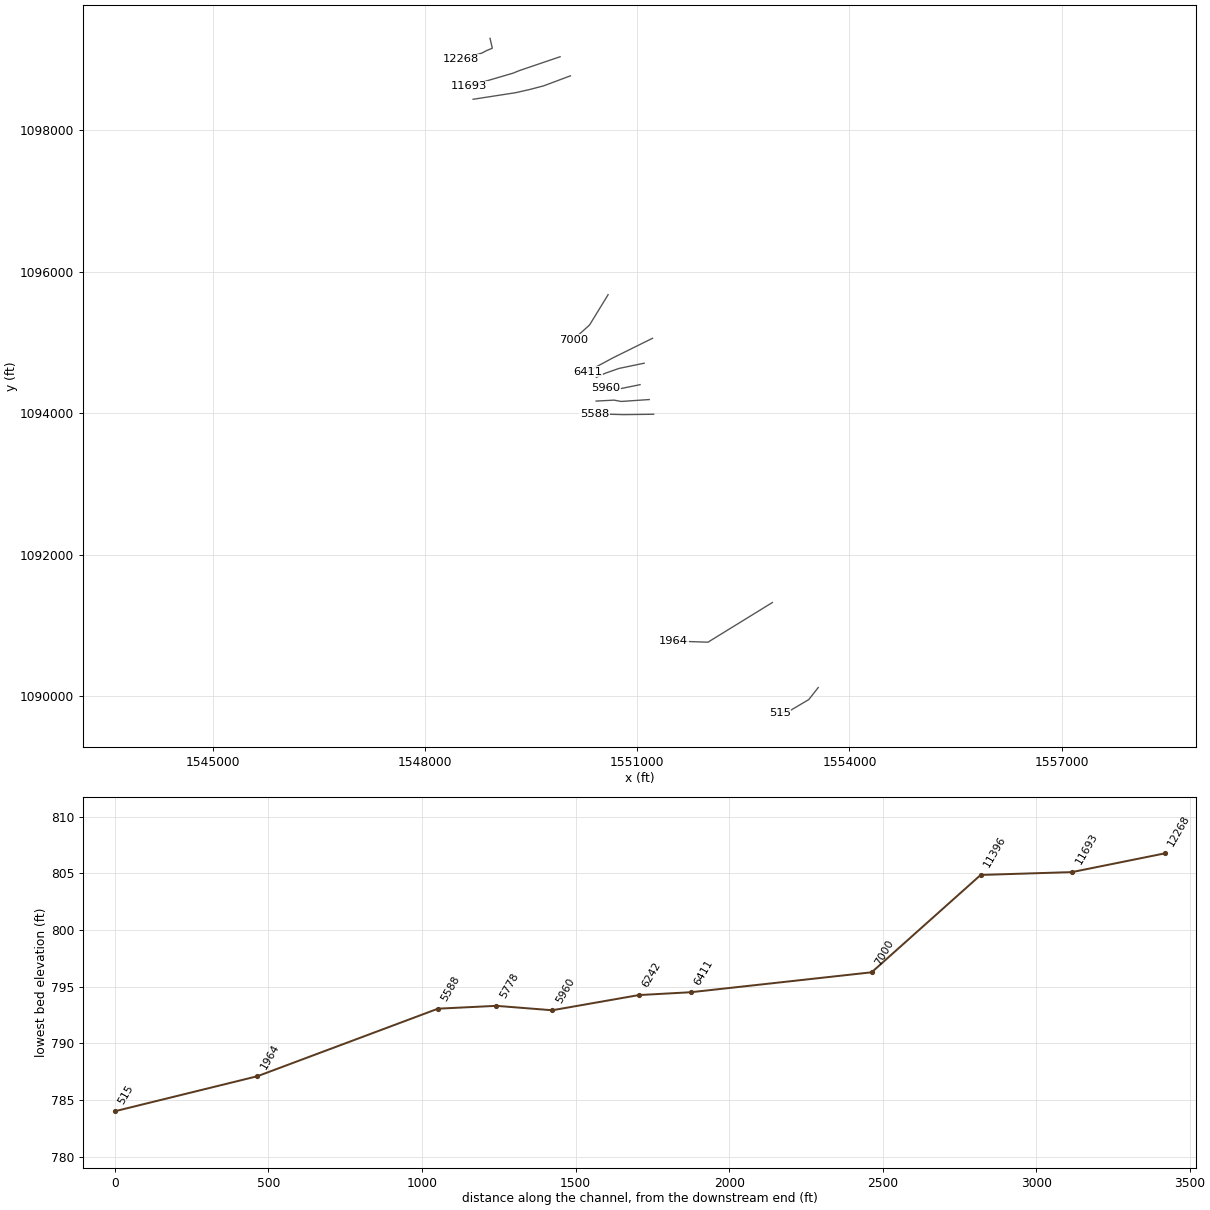
HEC-RAS study GeorgesCreek.prj: Georges Creek Limited Detail Study

--- GeorgesCreek.g01 (geometry) --- (continued)

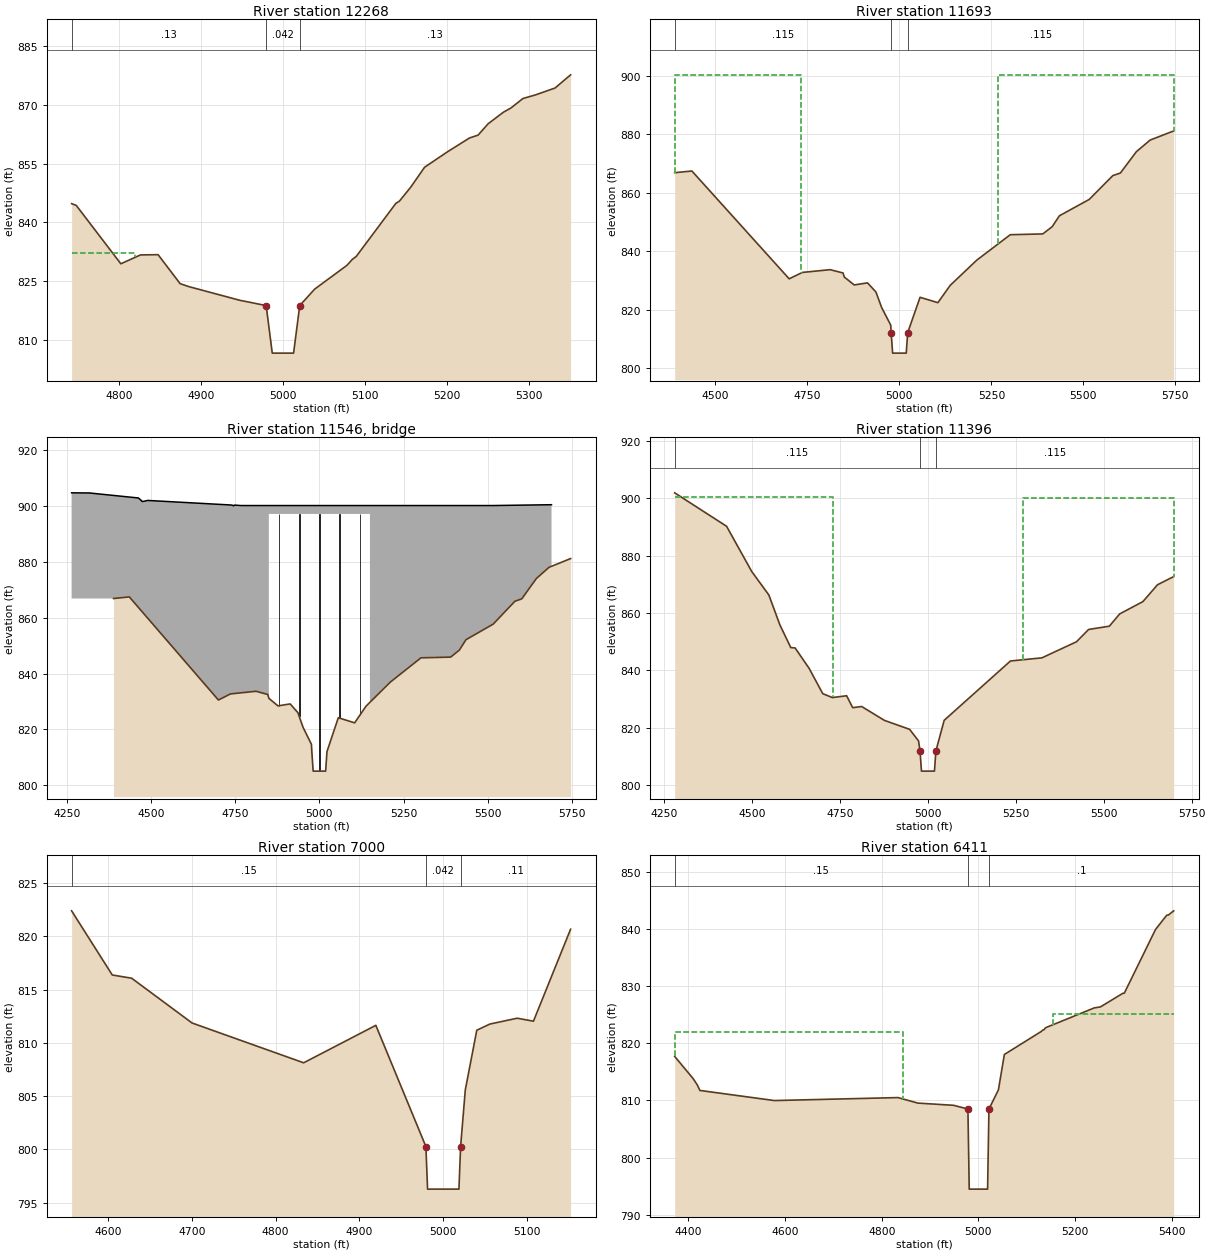
Type RM Length L Ch R = 1 ,12268   ,302,302,302
BEGIN DESCRIPTION:
Georges Creek 24.5
END DESCRIPTION:
XS GIS Cut Line= 5
      1548920.58      1099301.55      1548952.55      1099162.04
      1548872.62      1099128.62      1548807.23      1099093.74
      1548515.13        1099008.
#Sta/Elev= 30
  4742.4   844.8  4748.1  844.34  4802.4  829.49  4826.3  831.74  4847.8  831.81
  4874.7  824.43  4885.6  823.66  4947.6  820.19  4979.6  818.85    4987  806.75
    5013  806.75  5020.5  818.85  5038.7  823.04  5078.1   829.1  5084.5  830.59
  5089.4  831.36  5137.7  844.87    5142  845.43  5155.9  849.01  5172.7  854.06
  5201.2  858.07  5227.5  861.51  5237.9  862.23  5250.2  865.13  5268.9  868.08
  5278.1  869.16  5292.6  871.55  5307.6  872.45  5331.8  874.23  5350.7  877.58
#Mann= 3 ,-1,0
  4742.4     .13       0  4979.6    .042       0  5020.5     .13       0
#XS Ineff= 2 , 0
       0    4820  832.28    5180       0   851.3
Permanent Ineff=
       F       F
Bank Sta=4979.6,5020.5
XS Rating Curve= 0 ,0
Exp/Cntr=0.5,0.3

Type RM Length L Ch R = 1 ,11693   ,297,297,297
BEGIN DESCRIPTION:
Georges Creek 23.0
END DESCRIPTION:
XS GIS Cut Line= 4
      1549910.95      1099041.42      1549336.13      1098845.73
      1549245.38      1098808.91      1548620.49       1098625.8
#Sta/Elev= 30
  4389.1  866.84  4435.9  867.42  4700.3  830.53    4736  832.71  4811.7  833.66
  4846.8  832.53  4850.1  831.14  4877.1  828.44  4913.3  829.14  4936.2  826.01
  4951.7  820.71  4976.4  814.68  4977.5   812.1  4981.5   805.1  5018.5   805.1
  5022.5   812.1  5056.1   824.2  5104.6  822.37  5138.1   828.3    5210  836.89
  5301.3  845.62  5389.7  845.89  5415.4  848.39  5434.8  852.09  5515.8  857.69
  5580.2  865.86  5600.5  866.72  5644.1  874.03  5681.6  878.01  5745.4  881.13
#Mann= 3 ,-1,0
  4389.1    .115       0  4977.5     .04       0  5022.5    .115       0
#XS Ineff= 2 , 0
       0    4733  900.33    5267       0   900.1
Permanent Ineff=
       F       F
Bank Sta=4977.5,5022.5
XS Rating Curve= 0 ,0
Exp/Cntr=0.5,0.3

Type RM Length L Ch R = 3 ,11546   ,,,
BEGIN DESCRIPTION:
Southern Railway (Georges Cr.) - TOR
Structure ID: Southern Railway (Georges Cr.)
Approximate Survey Structure
END DESCRIPTION:
Bridge Culvert--1,0,-1,-1, 0
Deck Dist Width WeirC Skew NumUp NumDn MinLoCord MaxHiCord MaxSubmerge Is_Ogee
117,60,3,0, 29, 29, , , , 0, 1,1,,
  4264.7  4319.5    4320  4320.2  4320.3  4321.2    4463  4471.2    4472  4472.6
  4473.3    4475  4490.3  4738.7  4743.3  4743.9  4744.1  4744.4  4744.8  4745.2
  4745.5  4748.3  4767.5    4850    4850    5150    5150    5514  5688.7
  904.65   904.6  904.62  904.61  904.59  904.55  902.81  901.93  901.89   901.7
  901.64  901.52  901.93  900.29  900.16  900.07  900.07  900.06  900.02  900.04
  900.01  900.26   900.1   900.1   900.1   900.1   900.1   900.1   900.4
   785.1   785.1   785.1   785.1   785.1   785.1   785.1   785.1   785.1   785.1
   785.1   785.1   785.1   785.1   785.1   785.1   785.1   785.1   785.1   785.1
   785.1   785.1   785.1   785.1   897.1   897.1   785.1   785.1   785.1
  4264.7  4319.5    4320  4320.2  4320.3  4321.2    4463  4471.2    4472  4472.6
  4473.3    4475  4490.3  4738.7  4743.3  4743.9  4744.1  4744.4  4744.8  4745.2
  4745.5  4748.3  4767.5    4850    4850    5150    5150    5514  5688.7
  904.65   904.6  904.62  904.61  904.59  904.55  902.81  901.93  901.89   901.7
  901.64  901.52  901.93  900.29  900.16  900.07  900.07  900.06  900.02  900.04
  900.01  900.26   900.1   900.1   900.1   900.1   900.1   900.1   900.4
   785.1   785.1   785.1   785.1   785.1   785.1   785.1   785.1   785.1   785.1
   785.1   785.1   785.1   785.1   785.1   785.1   785.1   785.1   785.1   785.1
   785.1   785.1   785.1   785.1   897.1   897.1   785.1   785.1   785.1
Pier Skew, UpSta & Num, DnSta & Num=  ,4880, 2 ,4880, 2 , 0 , 0 , 0 ,0,0
       2       2
  828.37   897.1
       2       2
  822.48   897.1
Pier Skew, UpSta & Num, DnSta & Num=  ,4940, 2 ,4940, 2 , 0 , 0 , 0 ,0,0
       2       2
  824.71   897.1
       2       2
   819.7   897.1
Pier Skew, UpSta & Num, DnSta & Num=  ,5000, 2 ,5000, 2 , 0 , 0 , 0 ,0,0
       2       2
   805.1   897.1
       2       2
  804.85   897.1
Pier Skew, UpSta & Num, DnSta & Num=  ,5060, 2 ,5060, 2 , 0 , 0 , 0 ,0,0
       2       2
  824.01   897.1
       2       2
  824.19   897.1
Pier Skew, UpSta & Num, DnSta & Num=  ,5120, 2 ,5120, 2 , 0 , 0 , 0 ,0,0
       2       2
  825.17   897.1
       2       2
  830.97   897.1
Abutment Skew #Up #Dn= , 2 , 2
    4850    4900
   897.1  828.21
    4850    4900
   897.1   822.2
Abutment Skew #Up #Dn= , 2 , 2
    5100    5150
  822.45   897.1
    5100    5150
  828.83   897.1
BR Coef= 1 , 1 , 0 ,1.25, 0 ,,,0.8,0,2,0,
WSPro=,,,, 1 ,,,, 0 ,,,, 0 ,,,,-1 ,-1 ,-1 , 0 , 0 , 0 , 0 , 0
BC Design=,, 0 ,, 0 ,,,,,,
BC HTab HWMax=881.13
BC Use User HTab Curves=0
BC User HTab FreeFlow(D)= 0

Type RM Length L Ch R = 1 ,11396   ,355,355,355
BEGIN DESCRIPTION:
Georges Creek 22.5
END DESCRIPTION:
XS GIS Cut Line= 5
      1550056.27      1098771.12      1549675.53      1098628.71
      1549474.02      1098576.13      1549283.16       1098532.8
      1548681.53      1098439.79
#Sta/Elev= 30
  4279.6  901.91  4427.2  890.25  4499.1  874.41  4547.5  866.29    4579  855.81
  4609.9  847.93  4622.1  847.82  4662.3  840.63  4700.8  831.86  4728.2  830.51
  4768.7  831.14  4785.9  826.99  4811.5  827.39  4875.9  822.56  4947.9  819.42
  4973.2  815.38  4977.5  811.85  4981.5  804.85  5018.5  804.85  5022.5  811.85
  5046.1  822.57  5234.6  843.26  5324.2  844.36  5422.5  849.97  5456.8  854.25
    5516  855.41  5545.3  859.68  5611.4  863.98    5653  869.86  5698.8  872.69
#Mann= 3 ,-1,0
  4279.6    .115       0  4977.5     .04       0  5022.5    .115       0
#XS Ineff= 2 , 0
       0    4730  900.35    5270       0   900.1
Permanent Ineff=
       F       F
Bank Sta=4977.5,5022.5
XS Rating Curve= 0 ,0
Exp/Cntr=0.5,0.3

Type RM Length L Ch R = 1 ,7000    ,589,589,589
BEGIN DESCRIPTION:
Georges Creek 14.0
END DESCRIPTION:
XS GIS Cut Line= 3
        1550589.      1095675.48      1550326.46      1095246.59
      1550094.58      1095038.68
#Sta/Elev= 16
  4556.7  822.41  4605.2  816.38  4628.3  816.08  4700.4  811.87  4833.5  808.13
  4919.6  811.65  4979.3  800.26  4981.3  796.26  5018.7  796.26  5020.7  800.26
  5026.3  805.58    5040  811.19  5055.6  811.77  5088.2  812.32  5107.6  812.04
  5151.9  820.68
#Mann= 3 ,-1,0
  4556.7     .15       0  4979.3    .042       0  5020.7     .11       0
Bank Sta=4979.3,5020.7
XS Rating Curve= 0 ,0
Exp/Cntr=0.5,0.3

Type RM Length L Ch R = 1 ,6411    ,169,169,169
BEGIN DESCRIPTION:
Georges Creek 13.0
END DESCRIPTION:
XS GIS Cut Line= 3
      1551217.06      1095059.49      1550653.69      1094780.53
      1550298.16       1094589.1
#Sta/Elev= 27
  4371.5   817.7  4409.4  813.85  4418.9  812.63  4423.6  811.75  4577.7  809.98
  4833.6   810.5  4874.5  809.54  4948.5  809.15  4978.3   808.5    4981   794.5
    5019   794.5  5021.8   808.5  5041.4  811.85  5053.7  818.03  5130.1  822.06
  5133.7  822.33  5135.6  822.34  5138.7  822.68  5140.2  822.75  5239.9  826.18
  5252.4  826.34  5298.8  828.72  5301.9  828.75  5366.5  839.88  5389.6  842.36
  5393.1  842.41    5404  843.14
#Mann= 3 ,-1,0
  4371.5     .15       0  4978.3    .042       0  5021.8      .1       0
#XS Ineff= 2 , 0
       0  4844.8  821.95  5155.3       0  825.06
Permanent Ineff=
       F       F
Bank Sta=4978.3,5021.8
XS Rating Curve= 0 ,0
Exp/Cntr=0.5,0.3

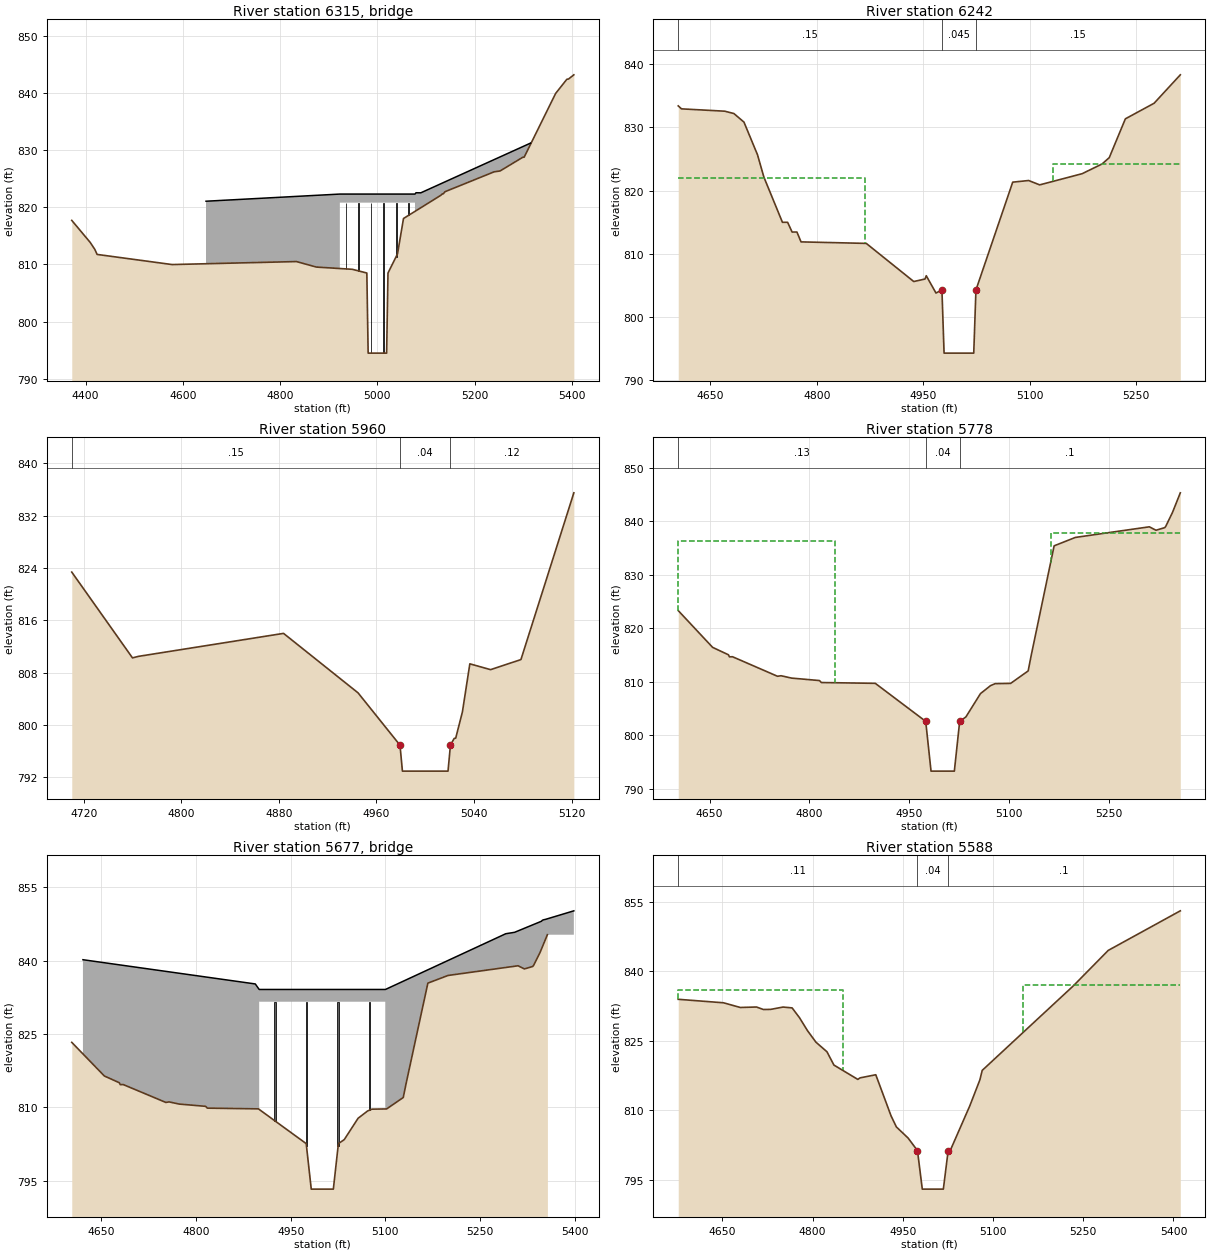
Type RM Length L Ch R = 3 ,6315    ,,,
BEGIN DESCRIPTION:
Old Easley Hwy. - TOR
Structure ID: LDS_GC_04
Approximate Survey Structure
END DESCRIPTION:
Bridge Culvert--1,0,-1,-1, 0
Deck Dist Width WeirC Skew NumUp NumDn MinLoCord MaxHiCord MaxSubmerge Is_Ogee
78,36,3,0, 8, 8, , , , 0, 1,1,,
  4647.6  4922.8  4922.8  5077.3  5077.3  5079.4  5089.3    5315
  821.05   822.3   822.3   822.3   822.3  822.53  822.52  831.21
   774.5   774.5   820.8   820.8   774.5   774.5   774.5   774.5
  4647.6  4922.8  4922.8  5077.3  5077.3  5079.4  5089.3    5315
  821.05   822.3   822.3   822.3   822.3  822.53  822.52  831.21
   774.5   774.5   820.8   820.8   774.5   774.5   774.5   774.5
Pier Skew, UpSta & Num, DnSta & Num=  ,4935.6, 2 ,4935.6, 2 , 0 , 0 , 0 ,0,0
     1.5     1.5
  809.22   820.8
     1.5     1.5
  805.66   820.8
Pier Skew, UpSta & Num, DnSta & Num=  ,4961.4, 2 ,4961.4, 2 , 0 , 0 , 0 ,0,0
     1.5     1.5
  810.17   820.8
     1.5     1.5
  805.03   820.8
Pier Skew, UpSta & Num, DnSta & Num=  ,4987.1, 2 ,4987.1, 2 , 0 , 0 , 0 ,0,0
     1.5     1.5
   794.5   820.8
     1.5     1.5
  794.25   820.8
Pier Skew, UpSta & Num, DnSta & Num=  ,5012.9, 2 ,5012.9, 2 , 0 , 0 , 0 ,0,0
     1.5     1.5
   794.5   820.8
     1.5     1.5
  794.25   820.8
Pier Skew, UpSta & Num, DnSta & Num=  ,5038.6, 2 ,5038.6, 2 , 0 , 0 , 0 ,0,0
     1.5     1.5
   811.8   820.8
     1.5     1.5
  803.26   820.8
Pier Skew, UpSta & Num, DnSta & Num=  ,5064.4, 2 ,5064.4, 2 , 0 , 0 , 0 ,0,0
     1.5     1.5
  818.59   820.8
     1.5     1.5
  815.79   820.8
Abutment Skew #Up #Dn= , 2 , 2
  4922.8  4923.8
   820.8  809.28
  4922.8  4923.8
   820.8  806.73
Abutment Skew #Up #Dn= , 2 , 2
  5076.3  5077.3
  819.22   820.8
  5076.3  5077.3
  821.33   820.8
BR Coef= 1 , 1 , 0 ,1.25, 0 ,,,0.8,0,2,0,
WSPro=,,,, 1 ,,,, 0 ,,,, 0 ,,,,-1 ,-1 ,-1 , 0 , 0 , 0 , 0 , 0
BC Design=,, 0 ,, 0 ,,,,,,
BC HTab HWMax=843.14
BC Use User HTab Curves=0
BC User HTab FreeFlow(D)= 0

Type RM Length L Ch R = 1 ,6242    ,282,282,282
BEGIN DESCRIPTION:
Georges Creek 12.5
END DESCRIPTION:
XS GIS Cut Line= 4
       1551098.1      1094706.69      1550742.57      1094632.85
       1550548.4      1094564.48      1550422.59      1094507.05
#Sta/Elev= 30
  4604.6  833.41  4609.2  832.94  4670.1  832.57    4683   832.2  4697.2  830.84
  4716.3  825.66  4725.3  822.12  4751.4  814.97  4758.7  814.97    4765  813.43
  4771.8  813.43  4777.6  811.87  4869.5  811.63  4936.4  805.59  4952.3  805.99
    4954  806.51  4967.7  803.77  4976.1  804.25  4979.1  794.25  5020.9  794.25
    5024  804.25  5075.8  821.33  5098.2  821.59  5113.8   820.9  5173.6  822.67
  5201.7  824.21  5211.8  825.21  5234.5  831.36    5275  833.83  5311.9  838.33
#Mann= 3 ,-1,0
  4604.6     .15       0  4976.1    .045       0    5024     .15       0
#XS Ineff= 2 , 0
       0  4867.8  822.05  5132.3       0  824.18
Permanent Ineff=
       F       F
Bank Sta=4976.1,5024
XS Rating Curve= 0 ,0
Exp/Cntr=0.5,0.3

Type RM Length L Ch R = 1 ,5960    ,182,182,182
BEGIN DESCRIPTION:
Georges Creek 12.0
END DESCRIPTION:
XS GIS Cut Line= 3
      1551040.87      1094403.23      1550762.74      1094346.52
      1550552.11      1094357.32
#Sta/Elev= 17
  4710.1  823.37  4759.9  810.24  4764.7  810.47  4883.8  813.99  4944.9  804.89
  4979.2  796.91  4979.3  796.91  4981.3  792.91  5018.7  792.91  5020.7  796.91
  5023.8  797.92    5025  797.95  5030.5  801.97  5036.6  809.33  5053.6  808.44
  5078.5  809.98  5121.9   835.5
#Mann= 3 ,-1,0
  4710.1     .15       0  4979.3     .04       0  5020.7     .12       0
Bank Sta=4979.3,5020.7
XS Rating Curve= 0 ,0
Exp/Cntr=0.5,0.3

Type RM Length L Ch R = 1 ,5778    ,190,190,190
BEGIN DESCRIPTION:
Georges Creek 11.5
END DESCRIPTION:
XS GIS Cut Line= 4
      1551170.49       1094192.6      1550773.54       1094165.6
      1550673.63       1094184.5      1550419.79        1094171.
#Sta/Elev= 30
    4603  823.29  4654.6  816.42  4678.3  815.04  4679.9  814.65  4684.5  814.67
    4752  811.02  4757.3  811.12  4773.1  810.68    4815  810.22  4817.9  809.85
  4898.8   809.7  4974.5   802.6  4982.5   793.3  5017.5   793.3  5025.5   802.6
  5034.8  803.42  5056.7  807.78  5071.8  809.27  5078.7  809.64    5102  809.69
  5128.3  812.02  5132.9  814.94  5167.3  835.39  5199.2  836.96  5310.2  838.94
  5320.2   838.3  5333.4  838.79  5334.9  839.04    5345  841.64  5356.7  845.29
#Mann= 3 ,-1,0
    4603     .13       0  4974.5     .04       0  5025.5      .1       0
#XS Ineff= 2 , 0
       0    4838  836.24    5162       0   837.8
Permanent Ineff=
       F       F
Bank Sta=4974.5,5025.5
XS Rating Curve= 0 ,0
Exp/Cntr=0.5,0.3

Type RM Length L Ch R = 3 ,5677    ,,,
BEGIN DESCRIPTION:
US Hwy 123 (Georges Cr.) - TOR
Structure ID: LDS_GC_03
Approximate Survey Structure
END DESCRIPTION:
Bridge Culvert--1,0,-1,-1, 0
Deck Dist Width WeirC Skew NumUp NumDn MinLoCord MaxHiCord MaxSubmerge Is_Ogee
62,78,3,0, 14, 14, , , , 0, 1,1,,
  4620.7  4893.8    4900    4900    5100    5100  5290.7  5304.7  5347.4  5348.2
  5348.9  5350.6  5353.8  5398.6
  840.18  835.23   834.1   834.1   834.1   834.1  845.49  845.78  848.05  848.18
  848.25  848.34  848.43  850.17
   773.3   773.3   773.3   831.6   831.6   773.3   773.3   773.3   773.3   773.3
   773.3   773.3   773.3   773.3
  4620.7  4893.8    4900    4900    5100    5100  5290.7  5304.7  5347.4  5348.2
  5348.9  5350.6  5353.8  5398.6
  840.18  835.23   834.1   834.1   834.1   834.1  845.49  845.78  848.05  848.18
  848.25  848.34  848.43  850.17
   773.3   773.3   773.3   831.6   831.6   773.3   773.3   773.3   773.3   773.3
   773.3   773.3   773.3   773.3
Pier Skew, UpSta & Num, DnSta & Num=  ,4925, 2 ,4925, 2 , 0 , 0 , 0 ,0,0
       2       2
  808.63   831.6
       2       2
  810.79   831.6
Pier Skew, UpSta & Num, DnSta & Num=  ,4975, 2 ,4975, 2 , 0 , 0 , 0 ,0,0
       2       2
  805.77   831.6
       2       2
  805.52   831.6
Pier Skew, UpSta & Num, DnSta & Num=  ,5025, 2 ,5025, 2 , 0 , 0 , 0 ,0,0
       2       2
  805.77   831.6
       2       2
  805.52   831.6
Pier Skew, UpSta & Num, DnSta & Num=  ,5075, 2 ,5075, 2 , 0 , 0 , 0 ,0,0
       2       2
  809.44   831.6
       2       2
  815.52   831.6
Abutment Skew #Up #Dn= , 2 , 2
    4900    4901
   831.6  809.61
    4900    4901
   831.6  817.59
Abutment Skew #Up #Dn= , 2 , 2
    5099    5100
  809.68   831.6
    5099    5100
  828.67   831.6
BR Coef= 1 , 1 , 0 ,1.25, 0 ,,,0.8,0,2,0,
WSPro=,,,, 1 ,,,, 0 ,,,, 0 ,,,,-1 ,-1 ,-1 , 0 , 0 , 0 , 0 , 0
BC Design=,, 0 ,, 0 ,,,,,,
BC HTab HWMax=845.29
BC Use User HTab Curves=0
BC User HTab FreeFlow(D)= 0

Type RM Length L Ch R = 1 ,5588    ,588,588,588
BEGIN DESCRIPTION:
Georges Creek 11.0
END DESCRIPTION:
XS GIS Cut Line= 3
       1551232.6      1093984.67      1550811.34      1093979.27
      1550398.19      1093990.08
#Sta/Elev= 30
  4576.8  833.96  4652.1  833.21  4679.9   832.2  4706.9   832.3  4718.4  831.76
  4730.5  831.79    4751  832.29  4766.1  832.11  4778.4  829.99  4791.9  827.16
  4805.8  824.71    4824  822.66  4835.6  819.79  4875.3   816.7  4879.1  817.03
  4905.2   817.7  4930.7   808.8  4939.4  806.46  4958.9  804.06  4974.5  801.35
  4982.5  793.05  5017.5  793.05  5025.5  801.35  5029.9  801.65  5061.5  811.01
  5078.2  816.59  5082.1  818.64  5233.5  836.85  5291.6   844.5  5411.4  853.03
#Mann= 3 ,-1,0
  4576.8     .11       0  4974.5     .04       0  5025.5      .1       0
#XS Ineff= 2 , 0
       0    4850  836.02    5150       0  837.09
Permanent Ineff=
       F       F
Bank Sta=4974.5,5025.5
XS Rating Curve= 0 ,0
Exp/Cntr=0.5,0.3

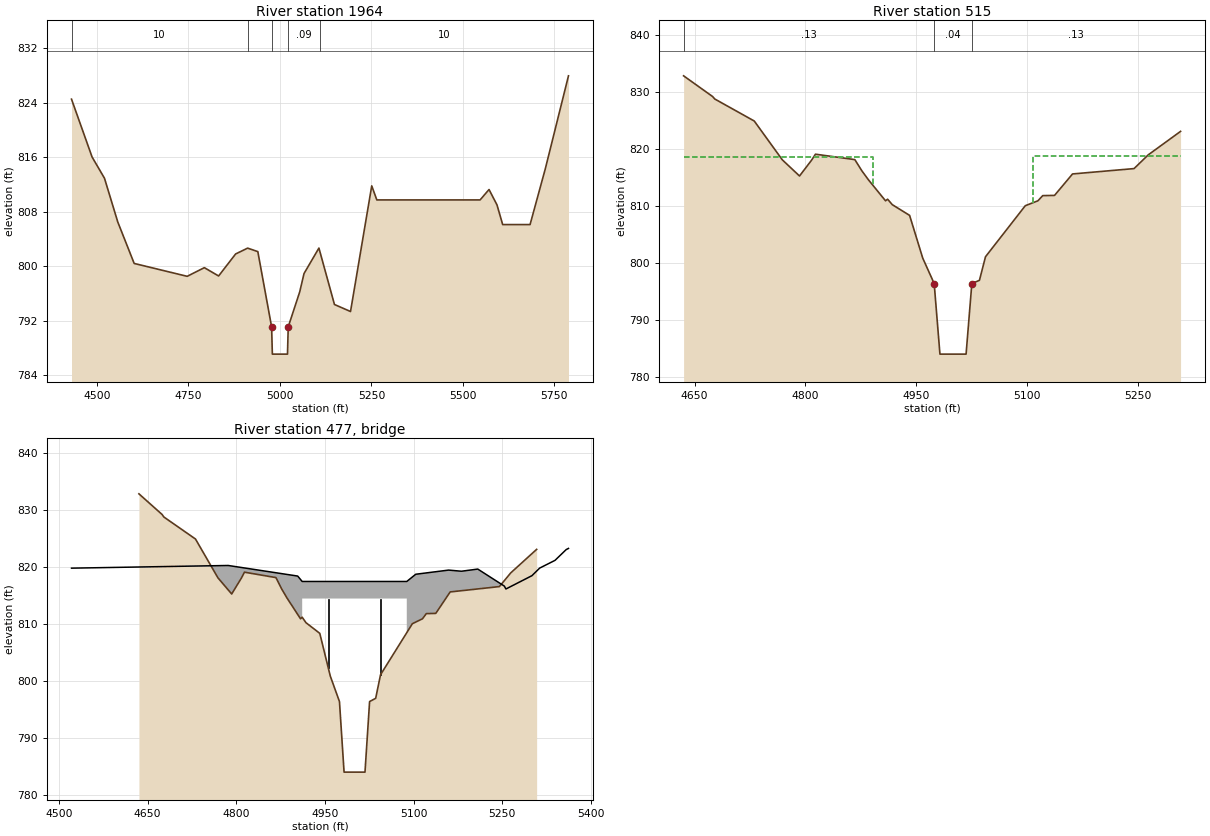
Type RM Length L Ch R = 1 ,1964    ,464,464,464
BEGIN DESCRIPTION:
Georges Creek 4.0
END DESCRIPTION:
XS GIS Cut Line= 3
      1552909.49      1091321.34      1551999.88      1090760.63
      1551513.93      1090777.24
#Sta/Elev= 30
  4430.3  824.54  4486.5  816.05  4520.4  812.93  4556.7  806.51  4601.6  800.41
  4746.5  798.52  4793.4  799.79  4832.4  798.57  4878.9   801.8  4911.7  802.66
  4939.6  802.15  4977.3  791.09  4979.3  787.09  5020.7  787.09  5022.7  791.09
  5054.1  796.23  5065.9  798.93  5106.6  802.67  5108.4  802.32  5149.1  794.38
    5193  793.35    5251  811.81  5264.9  809.74  5547.2  809.74  5571.6  811.27
  5593.4  809.01  5608.9  806.12  5683.8  806.12  5725.6  814.34  5788.8  827.97
#Mann= 5 ,-1,0
  4430.3      10       0  4911.7     .14       0  4977.3     .04       0
  5022.7     .09       0  5108.4      10       0
Bank Sta=4977.3,5022.7
XS Rating Curve= 0 ,0
Exp/Cntr=0.3,0.1

Type RM Length L Ch R = 1 ,515     ,110,110,110
BEGIN DESCRIPTION:
Georges Creek 1.8
END DESCRIPTION:
XS GIS Cut Line= 4
      1553558.25      1090119.36       1553424.7      1089949.13
      1553176.69      1089802.38      1553015.26      1089753.95
#Sta/Elev= 30
  4635.2   832.9  4674.5  829.26  4677.4  828.83  4730.9  824.96  4768.9  818.14
  4792.2   815.3  4808.6  818.09  4813.8  819.13  4867.1  818.18  4876.7   816.2
  4885.5  814.64  4908.7  810.94  4911.5  811.22  4917.9  810.26  4941.3  808.38
  4959.1  800.87  4974.6   796.4  4982.4     784  5017.8     784  5025.6   796.4
  5035.9  796.97  5044.1  801.11    5098  810.08  5115.1  810.94  5121.6  811.85
  5137.6  811.89    5162  815.66  5245.3   816.6  5264.5  819.01  5308.3  823.14
#Mann= 3 ,-1,0
  4635.2     .13       0  4974.6     .04       0  5025.6     .13       0
#XS Ineff= 2 , 0
       0  4891.5  818.65  5108.5       0  818.83
Permanent Ineff=
       F       F
Bank Sta=4974.6,5025.6
XS Rating Curve= 0 ,0
Exp/Cntr=0.5,0.3

Type RM Length L Ch R = 3 ,477     ,,,
BEGIN DESCRIPTION:
Old Easley Bridge Rd. - TOR
Structure ID: LDS_GC_01
Approximate Survey Structure
END DESCRIPTION:
Bridge Culvert--1,0,-1,-1, 0
Deck Dist Width WeirC Skew NumUp NumDn MinLoCord MaxHiCord MaxSubmerge Is_Ogee
20,36,3,0, 18, 18, , , , 0, 1,1,,
  4521.1  4786.3  4903.9  4911.5  4911.5  5088.5  5088.5  5103.7  5159.3    5181
  5208.7  5253.6  5256.3  5300.4  5313.4  5339.4  5358.4  5362.2
  819.84  820.31  818.45   817.5   817.5   817.5   817.5  818.77   819.5   819.3
  819.68  816.69  816.18  818.52  819.85  821.21  823.11  823.31
     764     764     764     764   814.5   814.5     764     764     764     764
     764     764     764     764     764     764     764     764
  4521.1  4786.3  4903.9  4911.5  4911.5  5088.5  5088.5  5103.7  5159.3    5181
  5208.7  5253.6  5256.3  5300.4  5313.4  5339.4  5358.4  5362.2
  819.84  820.31  818.45   817.5   817.5   817.5   817.5  818.77   819.5   819.3
  819.68  816.69  816.18  818.52  819.85  821.21  823.11  823.31
     764     764     764     764   814.5   814.5     764     764     764     764
     764     764     764     764     764     764     764     764
Pier Skew, UpSta & Num, DnSta & Num=  ,4955.8, 2 ,4955.8, 2 , 0 , 0 , 0 ,0,0
     2.5     2.5
  802.26   814.5
     2.5     2.5
  797.38   814.5
Pier Skew, UpSta & Num, DnSta & Num=  ,5044.3, 2 ,5044.3, 2 , 0 , 0 , 0 ,0,0
     2.5     2.5
  801.21   814.5
     2.5     2.5
  793.35   814.5
Abutment Skew #Up #Dn= , 2 , 2
  4911.5  4912.5
   814.5  811.07
  4911.5  4912.5
   814.5  800.53
Abutment Skew #Up #Dn= , 2 , 2
  5087.5  5088.5
  810.57   814.5
  5087.5  5088.5
  800.73   814.5
BR Coef= 1 , 1 , 0 ,1.25, 0 ,,,0.8,0,2,0,
WSPro=,,,, 1 ,,,, 0 ,,,, 0 ,,,,-1 ,-1 ,-1 , 0 , 0 , 0 , 0 , 0
BC Design=,, 0 ,, 0 ,,,,,,
BC HTab HWMax=832.9
BC Use User HTab Curves=0
BC User HTab FreeFlow(D)= 0