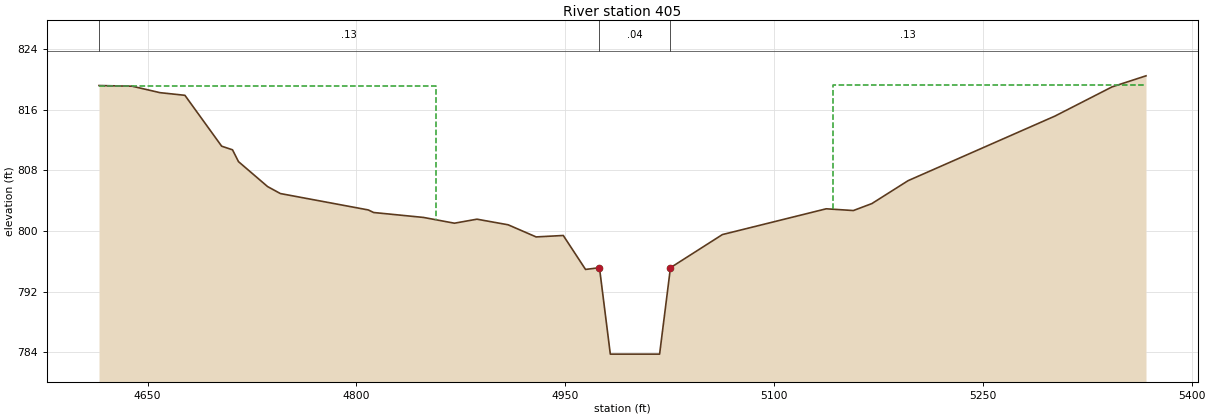
HEC-RAS study GeorgesCreek.prj: Georges Creek Limited Detail Study

--- GeorgesCreek.g01 (geometry) --- (continued)

Type RM Length L Ch R = 1 ,405     ,67,67,67
BEGIN DESCRIPTION:
Georges Creek 1.5
END DESCRIPTION:
XS GIS Cut Line= 5
      1553658.04      1090044.52       1553533.3      1089910.98
      1553399.75      1089811.18      1553228.33      1089697.53
      1553031.41      1089701.12
#Sta/Elev= 30
  4615.1  819.18  4638.9  819.09  4658.9  818.24  4676.8  817.89  4703.2  811.18
    4711   810.7  4715.3  809.14  4736.2  805.85  4745.4  804.93  4808.5  802.77
  4812.4  802.43  4848.2  801.78  4870.4  801.02  4886.6  801.55    4909  800.81
  4929.1  799.21  4948.6   799.4  4964.6  794.92  4974.6  795.15  4982.4  783.75
  5017.8  783.75  5025.6  795.15  5062.9  799.52  5137.5  802.92    5157  802.69
  5170.3  803.61  5196.3  806.63  5301.8  815.15  5342.8     819  5367.2  820.46
#Mann= 3 ,-1,0
  4615.1     .13       0  4974.6     .04       0  5025.6     .13       0
#XS Ineff= 2 , 0
       0  4857.5  819.18  5142.5       0  819.28
Permanent Ineff=
       F       F
Bank Sta=4974.6,5025.6
XS Rating Curve= 0 ,0
Exp/Cntr=0.5,0.3

--- GeorgesCreek.g02 (geometry) ---

Geom Title=Corrected Effective
Program Version=6.10

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
River Reach=Georges Creek   ,Reach-1

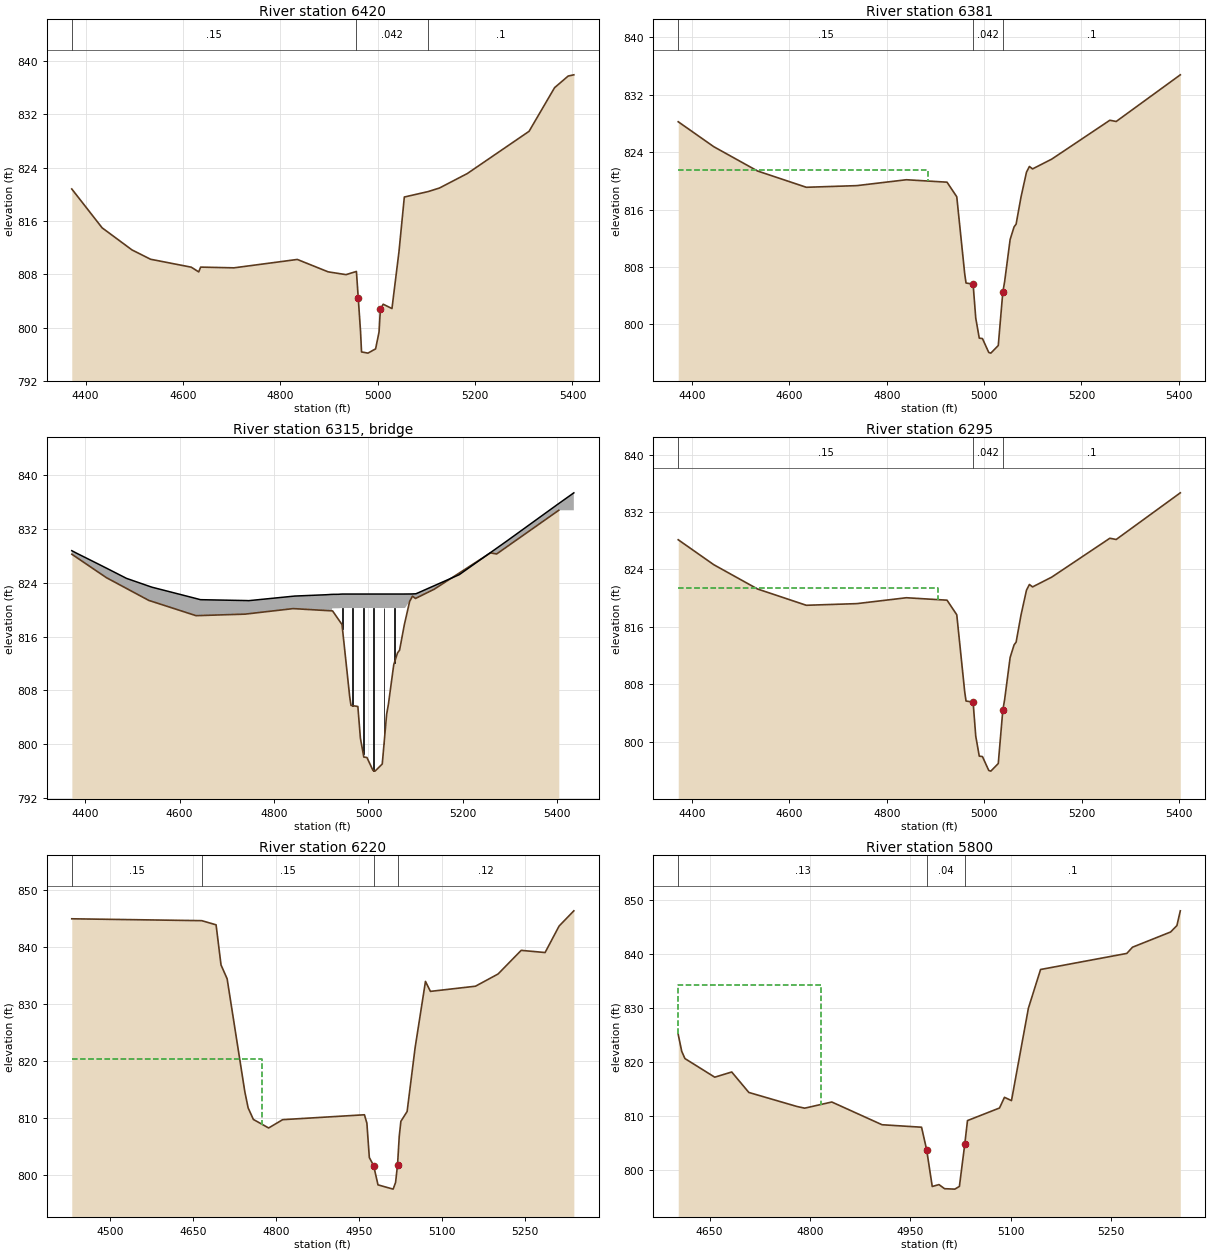
Type RM Length L Ch R = 1 ,6420    ,39,39,39
BEGIN DESCRIPTION:
Georges Creek 13.0
END DESCRIPTION:
XS GIS Cut Line= 2
    1551220.9265    1095051.0574    1550283.4392    1094621.2055
#Sta/Elev= 30
  4371.5  820.81  4433.8  814.98  4495.2  811.66  4533.4  810.26  4616.9  809.07
  4632.3  808.36  4636.2  809.08  4704.6  808.97  4834.8  810.23  4898.1  808.37
  4934.9  807.95  4956.2  808.43    4960 804.386  4964.6  799.49  4966.7  796.35
  4979.9  796.17  4995.6  796.81  5002.7  799.36  5005.4  802.75  5011.2  803.51
  5029.2  802.86  5043.6  811.39  5054.6   819.6  5103.7  820.42  5126.7  820.95
  5183.9  823.12  5310.8  829.46  5363.2  836.01  5391.2  837.76  5402.8  837.94
#Mann= 3 ,-1,0
  4371.5     .15       0  4956.2    .042       0  5103.7      .1       0
Bank Sta=4960,5005.4
XS Rating Curve= 0 ,0
Exp/Cntr=0.5,0.3

Type RM Length L Ch R = 1 ,6381    ,86,86,86
BEGIN DESCRIPTION:
Georges Creek 13.0
END DESCRIPTION:
XS GIS Cut Line= 4
    1551237.1813    1095015.6063    1551237.1813    1095015.6063
1550554.584369411094702.62543343     1550299.694    1094585.7544
#Sta/Elev= 30
 4371.75  828.24 4444.85  824.76 4534.65  821.38 4634.78  819.11  4738.6  819.34
 4840.41  820.16  4923.9  819.82 4943.91  817.79 4960.24  807.04 4962.95  805.77
 4977.47  805.61 4982.89  800.88 4990.11  798.09 4996.65  798.03 5009.56   796.1
 5013.89     796 5029.15  797.06 5038.42  804.45 5042.18  805.94 5053.51  811.83
 5061.54  813.58 5065.82  813.98 5075.89  817.76 5087.13  821.22 5093.13  822.01
  5099.6  821.67 5139.15  823.04 5258.34  828.45 5271.38  828.28 5403.09  834.78
#Mann= 3 ,-1,0
 4371.75     .15       0 4977.47    .042       0 5038.42      .1       0
#XS Ineff= 2 , 0
       0  4884.8  821.51 5129.47       0  821.51
Permanent Ineff=
       F       F
Bank Sta=4977.47,5038.42
XS Rating Curve= 0 ,0
Exp/Cntr=0.5,0.3

Type RM Length L Ch R = 3 ,6315    ,,,
BEGIN DESCRIPTION:
Old Easley Hwy. - TOR
Structure ID: LDS_GC_04
Approximate Survey Structure
END DESCRIPTION:
Bridge Culvert--1,0,-1,-1, 0
Deck Dist Width WeirC Skew NumUp NumDn MinLoCord MaxHiCord MaxSubmerge Is_Ogee
38,36,3,0, 101, 101, , , , 0, 1,1,,
  4371.5 4378.964382.864  4383.24388.4614401.3384406.5864410.5254412.3794421.558
4430.0454437.1174437.8764438.4174447.9654448.7614453.8394462.2044470.3554475.687
4482.0684486.5414487.4414489.5424495.8114503.5574510.1144521.8094532.3244537.422
4540.8064541.3474550.2264559.6414591.9224605.2024617.6154633.6334644.0624644.813
 4655.424664.4944709.4794742.1454746.127 4751.74 4778.774798.7544815.0954839.658
4843.5694843.5874844.2284855.3414866.5874892.0544910.732  4922.8  4922.8 4937.47
4939.7364942.1074944.6184944.618  5077.3  5077.3 5091.47 5091.475100.2975100.725
5106.5755133.0045147.8345158.4895186.0875192.0735192.2155192.2615192.3645192.501
5192.5495192.7075210.937  5213.15239.255 5262.155281.9165292.364 5292.425292.582
5298.8485318.9895350.7345367.0135391.2875397.3595399.5415401.6355406.1855419.167
5434.951
 828.775 828.501 828.358 828.346 828.163 827.713 827.529 827.391 827.326 827.003
 826.705 826.455 826.428 826.407 826.071 826.042  825.86 825.561 825.269 825.078
 824.849 824.689 824.657 824.606 824.453 824.265 824.105  823.82 823.563 823.439
 823.359 823.346 823.186 823.017 822.436 822.197 821.973 821.683 821.491  821.49
 821.475 821.463 821.402 821.358 821.343 821.382 821.572 821.712 821.827 821.999
 822.027 822.027 822.029 822.062 822.095  822.17 822.225  822.28  822.28  822.29
  822.31 822.317 822.326 822.326  822.33  822.33  822.34  822.34 822.369 822.373
 822.554 823.372 823.831 824.161 825.016 825.201 825.206 825.208 825.212 825.219
 825.221 825.229 826.136 826.244 827.542 828.678 829.659 830.178 830.178 830.188
 830.506 831.526 833.135  833.96  835.19 835.498 835.609 835.714 835.941 836.588
 837.375
                                                                                
                                                                                
                                                                                
                                                                                
                                                                                
                                                           820.2   820.2  820.21
  820.23  820.24  820.25  820.25  820.25  820.25  820.26
                                                                                
                                                                                
                                                                                
        
  4371.5 4378.964382.864  4383.24388.4614401.3384406.5864410.5254412.3794421.558
4430.0454437.1174437.8764438.4174447.9654448.7614453.8394462.2044470.3554475.687
4482.0684486.5414487.4414489.5424495.8114503.5574510.1144521.8094532.3244537.422
4540.8064541.3474550.2264559.6414591.9224605.2024617.6154633.6334644.0624644.813
 4655.424664.4944709.4794742.1454746.127 4751.74 4778.774798.7544815.0954839.658
4843.5694843.5874844.2284855.3414866.5874892.0544910.732  4922.8  4922.8 4937.47
4939.7364942.1074944.6184944.618  5077.3  5077.3 5091.47 5091.475100.2975100.725
5106.5755133.0045147.8345158.4895186.0875192.0735192.2155192.2615192.3645192.501
5192.5495192.7075210.937  5213.15239.255 5262.155281.9165292.364 5292.425292.582
5298.8485318.9895350.7345367.0135391.2875397.3595399.5415401.6355406.1855419.167
5434.951
 828.775 828.501 828.358 828.346 828.163 827.713 827.529 827.391 827.326 827.003
 826.705 826.455 826.428 826.407 826.071 826.042  825.86 825.561 825.269 825.078
 824.849 824.689 824.657 824.606 824.453 824.265 824.105  823.82 823.563 823.439
 823.359 823.346 823.186 823.017 822.436 822.197 821.973 821.683 821.491  821.49
 821.475 821.463 821.402 821.358 821.343 821.382 821.572 821.712 821.827 821.999
 822.027 822.027 822.029 822.062 822.095  822.17 822.225  822.28  822.28  822.29
  822.31 822.317 822.326 822.326  822.33  822.33  822.34  822.34 822.369 822.373
 822.554 823.372 823.831 824.161 825.016 825.201 825.206 825.208 825.212 825.219
 825.221 825.229 826.136 826.244 827.542 828.678 829.659 830.178 830.178 830.188
 830.506 831.526 833.135  833.96  835.19 835.498 835.609 835.714 835.941 836.588
 837.375
                                                                                
                                                                                
                                                                                
                                                                                
                                                                                
                                                           820.2   820.2  820.21
  820.23  820.24  820.25  820.25  820.25  820.25  820.26
                                                                                
                                                                                
                                                                                
        
Pier Skew, UpSta & Num, DnSta & Num=  ,4944.8, 2 ,4944.8, 2 , 0 , 0 , 0 ,0,0
    1.75    1.75
  809.22   820.8
    1.75    1.75
  805.66   820.8
Pier Skew, UpSta & Num, DnSta & Num=  ,4966.8, 2 ,4966.8, 2 , 0 , 0 , 0 ,0,0
    1.75    1.75
  810.17   820.8
    1.75    1.75
  805.03   820.8
Pier Skew, UpSta & Num, DnSta & Num=  ,4988.8, 2 ,4988.8, 2 , 0 , 0 , 0 ,0,0
    1.75    1.75
   794.5   820.8
    1.75    1.75
  794.25   820.8
Pier Skew, UpSta & Num, DnSta & Num=  ,5010.8, 2 ,5010.8, 2 , 0 , 0 , 0 ,0,0
    1.75    1.75
   794.5   820.8
    1.75    1.75
  794.25   820.8
Pier Skew, UpSta & Num, DnSta & Num=  ,5032.8, 2 ,5032.8, 2 , 0 , 0 , 0 ,0,0
    1.75    1.75
   811.8   820.8
    1.75    1.75
  803.26   820.8
Pier Skew, UpSta & Num, DnSta & Num=  ,5054.8, 2 ,5054.8, 2 , 0 , 0 , 0 ,0,0
    1.75    1.75
  818.59   820.8
    1.75    1.75
  815.79   820.8
Abutment Skew #Up #Dn= , 2 , 2
  4922.8 4943.37
     820     808
  4922.8 4943.37
     820     808
Abutment Skew #Up #Dn= , 2 , 2
 5090.47 5091.47
  819.22  820.08
 5090.47 5091.47
  819.22  820.08
BR Coef=-1 ,-1 , 0 ,1.25, 0 ,,,0.8,0,2,0,
WSPro=,,,, 1 ,,,, 0 ,,,, 0 ,,,,-1 ,-1 ,-1 , 0 , 0 , 0 , 0 , 0
BC Design=,, 0 ,, 0 ,,,,,,
BC HTab HWMax=843.14
BC Use User HTab Curves=0
BC User HTab FreeFlow(D)= 0

Type RM Length L Ch R = 1 ,6295    ,75,75,75
BEGIN DESCRIPTION:
Georges Creek 13.0
END DESCRIPTION:
XS GIS Cut Line= 2
    1551273.0254    1094937.4321     1550335.538    1094507.5802
#Sta/Elev= 30
  4371.5  828.13  4444.6  824.65  4534.4  821.27 4634.53     819 4738.35  819.23
 4840.16  820.05 4923.65  819.71 4943.66  817.68 4959.99  806.93  4962.7  805.66
 4977.22   805.5 4982.64  800.77 4989.86  797.98  4996.4  797.92 5009.31  795.99
 5013.64  795.89  5028.9  796.95 5038.17  804.34 5041.93  805.83 5053.26  811.72
 5061.29  813.47 5065.57  813.87 5075.64  817.65 5086.88  821.11 5092.88   821.9
 5099.35  821.56  5138.9  822.93 5258.09  828.34 5271.13  828.17 5402.84  834.67
#Mann= 3 ,-1,0
  4371.5     .15       0 4977.22    .042       0 5038.17      .1       0
#XS Ineff= 2 , 0
       0  4904.8   821.4 5109.47       0   821.4
Permanent Ineff=
       F       F
Bank Sta=4977.22,5038.17
XS Rating Curve= 0 ,0
Exp/Cntr=0.5,0.3

Type RM Length L Ch R = 1 ,6220    ,260,260,260
XS GIS Cut Line= 2
    1551320.6064    1094872.9437    1550360.5379    1094437.7468
#Sta/Elev= 30
    4430     845    4665  844.67 4690.89  843.94 4699.84  836.89 4710.87  834.46
 4742.87   814.6 4748.83  811.77 4758.32  809.73  4785.9  808.23 4811.28  809.69
 4959.12  810.55 4963.54  809.08 4967.95  803.04 4975.67  801.63 4983.62  798.23
 5010.98  797.48  5015.4  798.64 5018.98  801.76 5022.02  806.74    5025   809.4
 5036.29  811.13  5050.7  822.32 5069.46  833.99 5078.43  832.24 5159.93  833.15
 5200.76   835.3 5242.48  839.45 5285.72  839.07 5311.09  843.73  5337.7   846.4
#Mann= 4 ,-1,0
    4430     .15       0    4665     .15       0 4975.67    .045       0
 5018.98     .12       0
#XS Ineff= 2 , 0
       0  4774.8  820.36  5225.3       0  820.36
Permanent Ineff=
       F       F
Bank Sta=4975.67,5018.98
XS Rating Curve= 0 ,0
Exp/Cntr(USF)=0,0
Exp/Cntr=0.5,0.3

Type RM Length L Ch R = 1 ,5800    ,42,42,42
BEGIN DESCRIPTION:
Georges Creek 11.5
END DESCRIPTION:
XS GIS Cut Line= 2
      1551170.49       1094192.6    1550419.6349    1094182.1911
#Sta/Elev= 30
    4603  825.18    4603  825.16  4608.2  822.06    4613  820.71  4657.6  817.26
    4683  818.22  4708.6  814.43  4780.6  811.83  4792.1  811.52  4832.7  812.66
  4907.8  808.45  4966.9  807.99  4974.5  803.83  4982.9  797.01    4993  797.36
  5001.3   796.6  5016.6  796.52  5023.5  797.02  5031.6   804.9  5035.6  809.22
  5083.5  811.55  5090.9  813.53  5101.4  812.92  5126.7  830.04  5144.9  837.21
  5273.9  840.19  5282.4  841.34  5339.4  844.16  5348.8  845.35  5353.9  848.08
#Mann= 3 ,-1,0
    4603     .13       0  4974.5     .04       0  5031.6      .1       0
#XS Ineff= 2 , 0
       0    4816  834.26    5184       0   837.8
Permanent Ineff=
       F       F
Bank Sta=4974.5,5031.6
XS Rating Curve= 0 ,0
Exp/Cntr=0.5,0.3

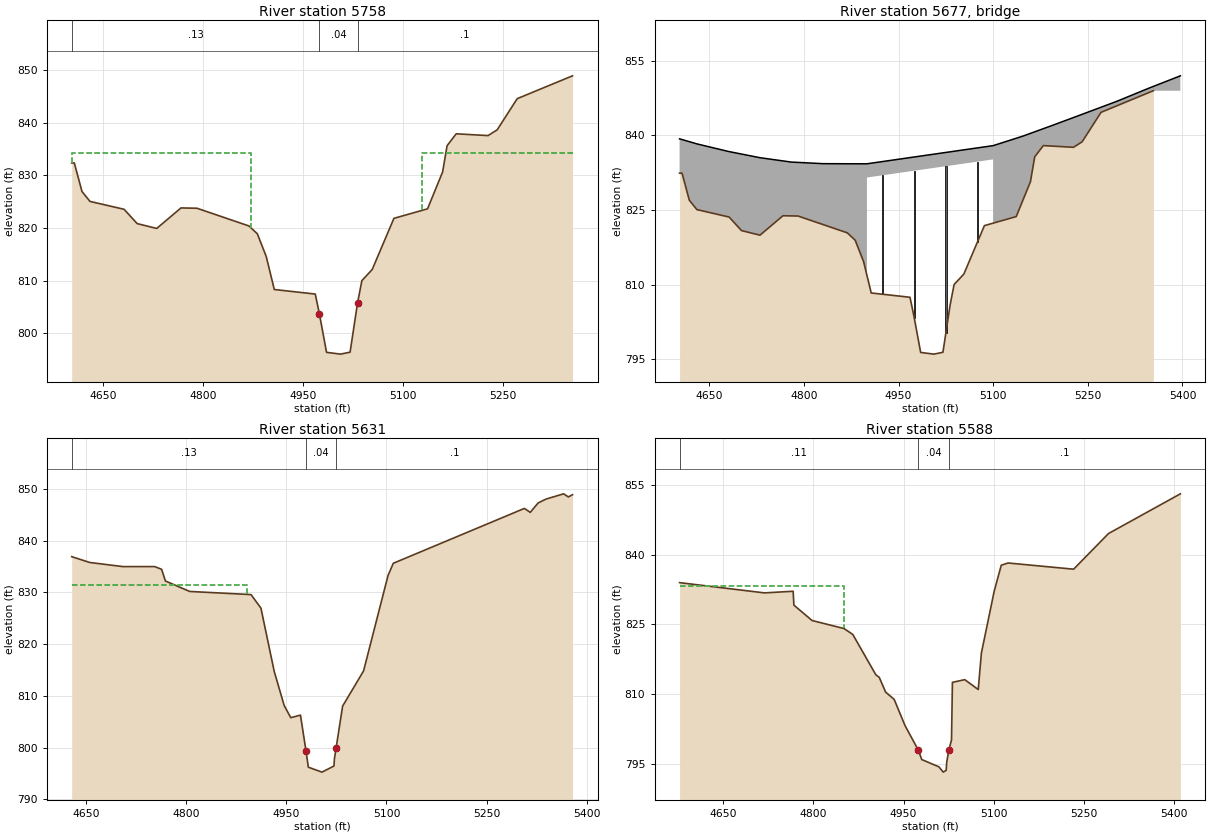
Type RM Length L Ch R = 1 ,5758    ,127,127,127
BEGIN DESCRIPTION:
Georges Creek 11.5
END DESCRIPTION:
XS GIS Cut Line= 2
    1551171.0722     1094150.604     1550420.217    1094140.1951
#Sta/Elev= 30
    4603  832.37 4606.91  832.37 4618.43  826.94 4630.42  825.06 4681.53  823.56
 4701.16  820.84 4730.48  819.92 4766.87  823.82 4790.84  823.76 4868.79  820.39
 4881.33  818.91 4894.71  814.58 4906.78  808.31 4968.19  807.45  4974.5  803.62
 4985.11  796.37 5006.02  796.03 5020.42   796.4  5031.6  805.75  5038.1     810
  5053.6  812.12 5086.16  821.84 5136.57  823.65 5159.13  830.65 5165.88  835.65
 5179.53  837.91 5227.28  837.57 5240.96  838.66 5271.01  844.59 5353.93  848.93
#Mann= 3 ,-1,0
    4603     .13       0  4974.5     .04       0  5031.6      .1       0
#XS Ineff= 2 , 0
       0    4872  834.26    5128       0  834.26
Permanent Ineff=
       F       F
Bank Sta=4974.5,5031.6
XS Rating Curve= 0 ,0
Exp/Cntr=0.5,0.3

Type RM Length L Ch R = 3 ,5677    ,,,
BEGIN DESCRIPTION:
US Hwy 123 (Georges Cr.) - TOR
Structure ID: LDS_GC_03
Approximate Survey Structure
END DESCRIPTION:
Bridge Culvert--1,0,-1,-1, 0
Deck Dist Width WeirC Skew NumUp NumDn MinLoCord MaxHiCord MaxSubmerge Is_Ogee
28,78,3,0, 20, 20, , , , 0, 1,1,,
    4603 4630.26 4630.73 4680.33 4730.12 4780.09  4830.3  4883.7    4900    4900
    5100    5100 5146.87 5196.91 5246.78 5246.78 5297.07 5297.07 5346.71 5396.73
 839.271 838.263 838.248 836.737 835.487 834.602 834.282 834.257 834.257 834.257
 837.904 837.904 839.803 842.112 844.467 844.467 846.856 846.856 849.443 851.924
                                                                           831.5
  835.14
    4603 4630.26 4630.73 4680.33 4730.12 4780.09  4830.3  4883.7    4900    4900
    5100    5100 5146.87 5196.91 5246.78 5246.78 5297.07 5297.07 5346.71 5396.73
 839.271 838.263 838.248 836.737 835.487 834.602 834.282 834.257 834.257 834.257
 837.904 837.904 839.803 842.112 844.467 844.467 846.856 846.856 849.443 851.924
                                                                           831.5
  835.14
Pier Skew, UpSta & Num, DnSta & Num=  ,4925, 2 ,4925, 2 , 0 , 0 , 0 ,0,0
    2.33    2.33
  808.63     832
    2.33    2.33
  810.79     832
Pier Skew, UpSta & Num, DnSta & Num=  ,4975, 2 ,4975, 2 , 0 , 0 , 0 ,0,0
    2.33    2.33
  805.77     833
    2.33    2.33
  805.52     833
Pier Skew, UpSta & Num, DnSta & Num=  ,5025, 2 ,5025, 2 , 0 , 0 , 0 ,0,0
    2.33    2.33
  805.77   834.6
    2.33    2.33
  805.52   834.6
Pier Skew, UpSta & Num, DnSta & Num=  ,5075, 2 ,5075, 2 , 0 , 0 , 0 ,0,0
    2.33    2.33
  809.44   835.6
    2.33    2.33
  815.52   835.6
Abutment Skew #Up #Dn= , 10 , 10
    4900 4902.39 4904.05 4907.63 4908.73 4911.98 4923.34 4925.11 4929.03 4941.87
 830.465 830.465  827.77 826.686 826.475 824.555 817.377  816.54 814.314 808.123
    4900 4902.39 4904.05 4907.63 4908.73 4911.98 4923.34 4925.11 4929.03 4941.87
 830.465 830.465  827.77 826.686 826.475 824.555 817.377  816.54 814.314 808.123
Abutment Skew #Up #Dn= , 8 , 8
    5054 5054.43 5060.64 5063.99 5072.63 5074.05 5075.51    5100
     810  811.08   816.1  818.38  823.04  823.92  824.56  833.04
    5054 5054.43 5060.64 5063.99 5072.63 5074.05 5075.51    5100
     810  811.08   816.1  818.38  823.04  823.92  824.56  833.04
BR Coef=-1 ,-1 , 0 ,1.25, 0 ,,,0.8,0,2,0,
WSPro=,,,, 1 ,,,, 0 ,,,, 0 ,,,,-1 ,-1 ,-1 , 0 , 0 , 0 , 0 , 0
BC Design=,, 0 ,, 0 ,,,,,,
BC HTab HWMax=845.29
BC Use User HTab Curves=0
BC User HTab FreeFlow(D)= 0

Type RM Length L Ch R = 1 ,5631    ,43,43,43
BEGIN DESCRIPTION:
Georges Creek 11.5
END DESCRIPTION:
XS GIS Cut Line= 2
    1551172.8326    1094023.6162    1550421.9774    1094013.2073
#Sta/Elev= 30
    4628  836.91 4654.91  835.79  4704.8  834.99 4752.48  834.99  4762.8  834.47
 4768.53  832.21 4804.86  830.19 4896.89  829.58 4911.73  826.97 4931.69  814.73
 4946.53  808.17 4956.48   805.8 4971.03  806.29 4979.42  799.29 4982.84  796.23
 5003.29  795.28  5021.2  796.46 5021.99  797.91 5024.45  799.92 5034.19  808.03
 5065.63  814.83 5102.32  833.27  5110.2  835.63 5306.74  846.23 5315.57  845.47
 5327.31  847.28 5339.32  848.04 5365.62  849.05 5372.73  848.45 5378.93  848.88
#Mann= 3 ,-1,0
    4628     .13       0 4979.42     .04       0 5024.45      .1       0
#XS Ineff= 2 , 0
       0    4891   831.5    5123       0   831.5
Permanent Ineff=
       F       F
Bank Sta=4979.42,5024.45
XS Rating Curve= 0 ,0
Exp/Cntr=0.5,0.3

Type RM Length L Ch R = 1 ,5588    ,588,588,588
BEGIN DESCRIPTION:
Georges Creek 11.0
END DESCRIPTION:
XS GIS Cut Line= 3
       1551232.6      1093984.67      1550811.34      1093979.27
      1550398.19      1093990.08
#Sta/Elev= 30
  4576.8  833.96  4718.4  831.76  4766.1  832.114767.326 829.1354797.576 825.832
4850.913 824.1034865.506 822.8354904.031 814.1534909.492 813.6414920.245 810.455
4934.445 808.8964952.569 803.262  4974.5 798.0444980.428 795.9745008.932 794.421
  5016.3 793.2775021.068 793.6625022.041 795.413  5025.5 797.9675030.013 800.206
5031.502 812.5465052.072 813.1335074.556 811.0115079.796 818.8435101.183  832.15
 5112.93 837.7035124.261  838.18  5233.5  836.85  5291.6   844.5  5411.4  853.03
#Mann= 3 ,-1,0
  4576.8     .11       0  4974.5     .04       0  5025.5      .1       0
#XS Ineff= 2 , 0
       0    4850  833.26    5150       0  837.09
Permanent Ineff=
       F       F
Bank Sta=4974.5,5025.5
XS Rating Curve= 0 ,0
Exp/Cntr=0.5,0.3

--- GeorgesCreek.g03 (geometry) ---

Geom Title=Temporary Condition
Program Version=6.10

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
River Reach=Georges Creek   ,Reach-1

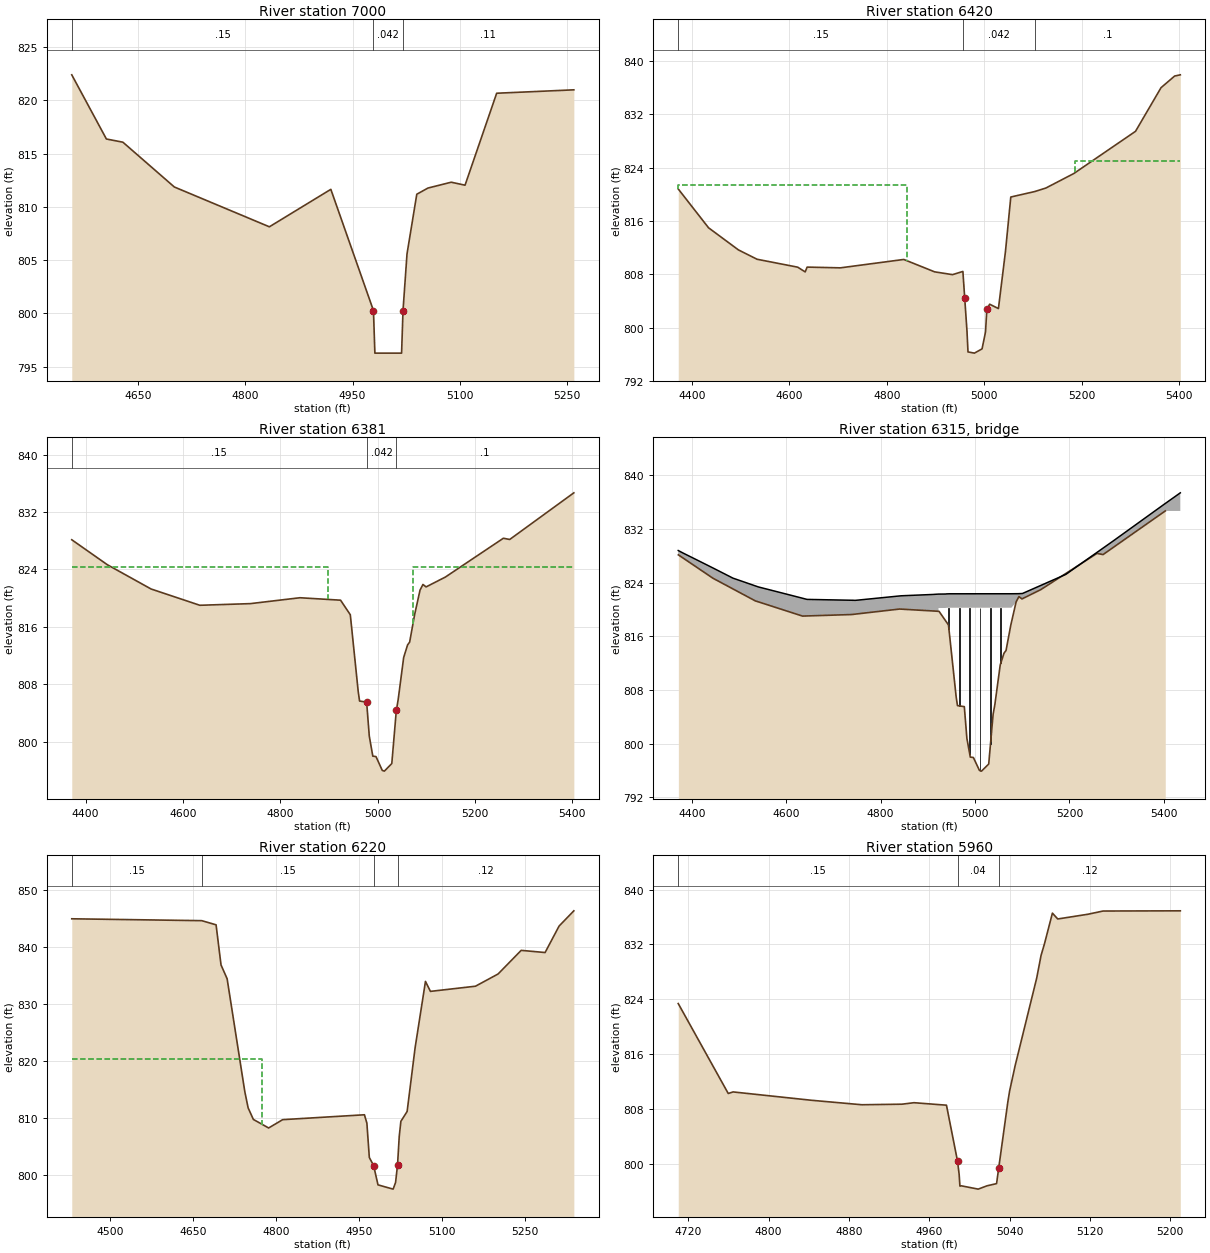
Type RM Length L Ch R = 1 ,7000    ,589,589,589
BEGIN DESCRIPTION:
Georges Creek 14.0
END DESCRIPTION:
XS GIS Cut Line= 3
        1550589.      1095675.48      1550326.46      1095246.59
      1550094.58      1095038.68
#Sta/Elev= 17
  4556.7  822.41  4605.2  816.38  4628.3  816.08  4700.4  811.87  4833.5  808.13
  4919.6  811.65  4979.3  800.26  4981.3  796.26  5018.7  796.26  5020.7  800.26
  5026.3  805.58    5040  811.19  5055.6  811.77  5088.2  812.32  5107.6  812.04
  5151.9  820.68    5260     821
#Mann= 3 ,-1,0
  4556.7     .15       0  4979.3    .042       0  5020.7     .11       0
Bank Sta=4979.3,5020.7
XS Rating Curve= 0 ,0
Exp/Cntr=0.5,0.3

Type RM Length L Ch R = 1 ,6420    ,39,39,39
BEGIN DESCRIPTION:
Georges Creek 13.0
END DESCRIPTION:
XS GIS Cut Line= 2
    1551220.9265    1095051.0574    1550283.4392    1094621.2055
#Sta/Elev= 30
  4371.5  820.81  4433.8  814.98  4495.2  811.66  4533.4  810.26  4616.9  809.07
  4632.3  808.36  4636.2  809.08  4704.6  808.97  4834.8  810.23  4898.1  808.37
  4934.9  807.95  4956.2  808.43    4960 804.386  4964.6  799.49  4966.7  796.35
  4979.9  796.17  4995.6  796.81  5002.7  799.36  5005.4  802.75  5011.2  803.51
  5029.2  802.86  5043.6  811.39  5054.6   819.6  5103.7  820.42  5126.7  820.95
  5183.9  823.12  5310.8  829.46  5363.2  836.01  5391.2  837.76  5402.8  837.94
#Mann= 3 ,-1,0
  4371.5     .15       0  4956.2    .042       0  5103.7      .1       0
#XS Ineff= 2 , 0
       0 4841.47  821.36 5187.47       0  825.06
Permanent Ineff=
       F       F
Bank Sta=4960,5005.4
XS Rating Curve= 0 ,0
Exp/Cntr=0.5,0.3

Type RM Length L Ch R = 1 ,6381    ,86,86,86
BEGIN DESCRIPTION:
Georges Creek 13.0
END DESCRIPTION:
XS GIS Cut Line= 4
    1551237.1813    1095015.6063    1551237.1813    1095015.6063
1550554.584369411094702.62543343     1550299.694    1094585.7544
#Sta/Elev= 30
 4371.75  828.13 4444.85  824.65 4534.65  821.27 4634.78     819  4738.6  819.23
 4840.41  820.05  4923.9  819.71 4943.91  817.68 4960.24  806.93 4962.95  805.66
 4977.47   805.5 4982.89  800.77 4990.11  797.98 4996.65  797.92 5009.56  795.99
 5013.89  795.89 5029.15  796.95 5038.42  804.34 5042.18  805.83 5053.51  811.72
 5061.54  813.47 5065.82  813.87 5075.89  817.65 5087.13  821.11 5093.13   821.9
  5099.6  821.56 5139.15  822.93 5258.34  828.34 5271.38  828.17 5403.09  834.67
#Mann= 3 ,-1,0
 4371.75     .15       0 4977.47    .042       0 5038.42      .1       0
#XS Ineff= 2 , 0
     .25 4898.55  824.38 5072.55     .25  824.38
Permanent Ineff=
       F       F
Bank Sta=4977.47,5038.42
XS Rating Curve= 0 ,0
Exp/Cntr=0.5,0.3

Type RM Length L Ch R = 3 ,6315    ,,,
BEGIN DESCRIPTION:
Old Easley Hwy. - TOR
Structure ID: LDS_GC_04
Approximate Survey Structure
END DESCRIPTION:
Bridge Culvert--1,0,-1,-1, 0
Deck Dist Width WeirC Skew NumUp NumDn MinLoCord MaxHiCord MaxSubmerge Is_Ogee
38,36,3,0, 101, 101, , , , 0, 1,1,,
  4371.5 4378.964382.864  4383.24388.4614401.3384406.5864410.5254412.3794421.558
4430.0454437.1174437.8764438.4174447.9654448.7614453.8394462.2044470.3554475.687
4482.0684486.5414487.4414489.5424495.8114503.5574510.1144521.8094532.3244537.422
4540.8064541.3474550.2264559.6414591.9224605.2024617.6154633.6334644.0624644.813
 4655.424664.4944709.4794742.1454746.127 4751.74 4778.774798.7544815.0954839.658
4843.5694843.5874844.2284855.3414866.5874892.0544910.732  4922.8  4922.8 4937.47
4939.7364942.1074944.6184944.618  5077.3  5077.3 5091.47 5091.475100.2975100.725
5106.5755133.0045147.8345158.4895186.0875192.0735192.2155192.2615192.3645192.501
5192.5495192.7075210.937  5213.15239.255 5262.155281.9165292.364 5292.425292.582
5298.8485318.9895350.7345367.0135391.2875397.3595399.5415401.6355406.1855419.167
5434.951
 828.775 828.501 828.358 828.346 828.163 827.713 827.529 827.391 827.326 827.003
 826.705 826.455 826.428 826.407 826.071 826.042  825.86 825.561 825.269 825.078
 824.849 824.689 824.657 824.606 824.453 824.265 824.105  823.82 823.563 823.439
 823.359 823.346 823.186 823.017 822.436 822.197 821.973 821.683 821.491  821.49
 821.475 821.463 821.402 821.358 821.343 821.382 821.572 821.712 821.827 821.999
 822.027 822.027 822.029 822.062 822.095  822.17 822.225  822.28  822.28  822.29
  822.31 822.317 822.326 822.326  822.33  822.33  822.34  822.34 822.369 822.373
 822.554 823.372 823.831 824.161 825.016 825.201 825.206 825.208 825.212 825.219
 825.221 825.229 826.136 826.244 827.542 828.678 829.659 830.178 830.178 830.188
 830.506 831.526 833.135  833.96  835.19 835.498 835.609 835.714 835.941 836.588
 837.375
                                                                                
                                                                                
                                                                                
                                                                                
                                                                                
                                                           820.2   820.2  820.21
  820.23  820.24  820.25  820.25  820.25  820.25  820.26
                                                                                
                                                                                
                                                                                
        
  4371.5 4378.964382.864  4383.24388.4614401.3384406.5864410.5254412.3794421.558
4430.0454437.1174437.8764438.4174447.9654448.7614453.8394462.2044470.3554475.687
4482.0684486.5414487.4414489.5424495.8114503.5574510.1144521.8094532.3244537.422
4540.8064541.3474550.2264559.6414591.9224605.2024617.6154633.6334644.0624644.813
 4655.424664.4944709.4794742.1454746.127 4751.74 4778.774798.7544815.0954839.658
4843.5694843.5874844.2284855.3414866.5874892.0544910.732  4922.8  4922.8 4937.47
4939.7364942.1074944.6184944.618  5077.3  5077.3 5091.47 5091.475100.2975100.725
5106.5755133.0045147.8345158.4895186.0875192.0735192.2155192.2615192.3645192.501
5192.5495192.7075210.937  5213.15239.255 5262.155281.9165292.364 5292.425292.582
5298.8485318.9895350.7345367.0135391.2875397.3595399.5415401.6355406.1855419.167
5434.951
 828.775 828.501 828.358 828.346 828.163 827.713 827.529 827.391 827.326 827.003
 826.705 826.455 826.428 826.407 826.071 826.042  825.86 825.561 825.269 825.078
 824.849 824.689 824.657 824.606 824.453 824.265 824.105  823.82 823.563 823.439
 823.359 823.346 823.186 823.017 822.436 822.197 821.973 821.683 821.491  821.49
 821.475 821.463 821.402 821.358 821.343 821.382 821.572 821.712 821.827 821.999
 822.027 822.027 822.029 822.062 822.095  822.17 822.225  822.28  822.28  822.29
  822.31 822.317 822.326 822.326  822.33  822.33  822.34  822.34 822.369 822.373
 822.554 823.372 823.831 824.161 825.016 825.201 825.206 825.208 825.212 825.219
 825.221 825.229 826.136 826.244 827.542 828.678 829.659 830.178 830.178 830.188
 830.506 831.526 833.135  833.96  835.19 835.498 835.609 835.714 835.941 836.588
 837.375
                                                                                
                                                                                
                                                                                
                                                                                
                                                                                
                                                           820.2   820.2  820.21
  820.23  820.24  820.25  820.25  820.25  820.25  820.26
                                                                                
                                                                                
                                                                                
        
Pier Skew, UpSta & Num, DnSta & Num=  ,4944.8, 2 ,4944.8, 2 , 0 , 0 , 0 ,0,0
    1.75    1.75
  809.22   820.8
    1.75    1.75
  805.66   820.8
Pier Skew, UpSta & Num, DnSta & Num=  ,4966.8, 2 ,4966.8, 2 , 0 , 0 , 0 ,0,0
    1.75    1.75
  810.17   820.8
    1.75    1.75
  805.03   820.8
Pier Skew, UpSta & Num, DnSta & Num=  ,4988.8, 2 ,4988.8, 2 , 0 , 0 , 0 ,0,0
    1.75    1.75
   794.5   820.8
    1.75    1.75
  794.25   820.8
Pier Skew, UpSta & Num, DnSta & Num=  ,5010.8, 2 ,5010.8, 2 , 0 , 0 , 0 ,0,0
    1.75    1.75
   794.5   820.8
    1.75    1.75
  794.25   820.8
Pier Skew, UpSta & Num, DnSta & Num=  ,5032.8, 2 ,5032.8, 2 , 0 , 0 , 0 ,0,0
    1.75    1.75
   811.8   820.8
    1.75    1.75
  803.26   820.8
Pier Skew, UpSta & Num, DnSta & Num=  ,5054.8, 2 ,5054.8, 2 , 0 , 0 , 0 ,0,0
    1.75    1.75
  818.59   820.8
    1.75    1.75
  815.79   820.8
Abutment Skew #Up #Dn= , 2 , 2
  4922.8 4943.37
     820     808
  4922.8 4943.37
     820     808
Abutment Skew #Up #Dn= , 2 , 2
 5090.47 5091.47
  819.22  820.08
  5076.3  5077.3
  819.22  820.08
BR Coef=-1 ,-1 , 0 ,1.25, 0 ,,,0.8,0,2,0,
WSPro=,,,, 1 ,,,, 0 ,,,, 0 ,,,,-1 ,-1 ,-1 , 0 , 0 , 0 , 0 , 0
BC Design=,, 0 ,, 0 ,,,,,,
BC HTab HWMax=843.14
BC Use User HTab Curves=0
BC User HTab FreeFlow(D)= 0

Type RM Length L Ch R = 1 ,6220    ,260,260,260
XS GIS Cut Line= 2
    1551320.6064    1094872.9437    1550360.5379    1094437.7468
#Sta/Elev= 30
    4430     845    4665  844.67 4690.89  843.94 4699.84  836.89 4710.87  834.46
 4742.87   814.6 4748.83  811.77 4758.32  809.73  4785.9  808.23 4811.28  809.69
 4959.12  810.55 4963.54  809.08 4967.95  803.04 4975.67  801.63 4983.62  798.23
 5010.98  797.48  5015.4  798.64 5018.98  801.76 5022.02  806.74    5025   809.4
 5036.29  811.13  5050.7  822.32 5069.46  833.99 5078.43  832.24 5159.93  833.15
 5200.76   835.3 5242.48  839.45 5285.72  839.07 5311.09  843.73  5337.7   846.4
#Mann= 4 ,-1,0
    4430     .15       0    4665     .15       0 4975.67    .045       0
 5018.98     .12       0
#XS Ineff= 2 , 0
       0  4774.8  820.36  5225.3       0  820.36
Permanent Ineff=
       F       F
Bank Sta=4975.67,5018.98
XS Rating Curve= 0 ,0
Exp/Cntr(USF)=0,0
Exp/Cntr=0.5,0.3

Type RM Length L Ch R = 1 ,5960    ,57.6,57.6,57.6
BEGIN DESCRIPTION:
Georges Creek 12.0
END DESCRIPTION:
XS GIS Cut Line= 4
      1551040.87      1094403.23      1550762.74      1094346.52
      1550552.11      1094357.321550540.936689951094357.89290865
#Sta/Elev= 27
  4710.1  823.37  4759.9  810.24  4764.7  810.474842.529 809.2544892.841 808.599
4932.809 808.6794944.874 808.8964977.175 808.5334988.165 800.3794989.785 798.446
4990.566  796.734992.082 796.7645008.815 796.2845017.452 796.7655027.048 797.088
 5029.24 799.4165038.279 809.0145040.111 810.6495045.509 814.2795067.002  827.08
5071.343 830.384 5074.81 832.1195082.657 836.561 5087.96 835.7115117.904 836.397
5133.088  836.87    5210   836.9
#Mann= 3 ,-1,0
  4710.1     .15       04988.165     .04       0 5029.24     .12       0
Bank Sta=4988.165,5029.24
XS Rating Curve= 0 ,0
Exp/Cntr=0.5,0.3

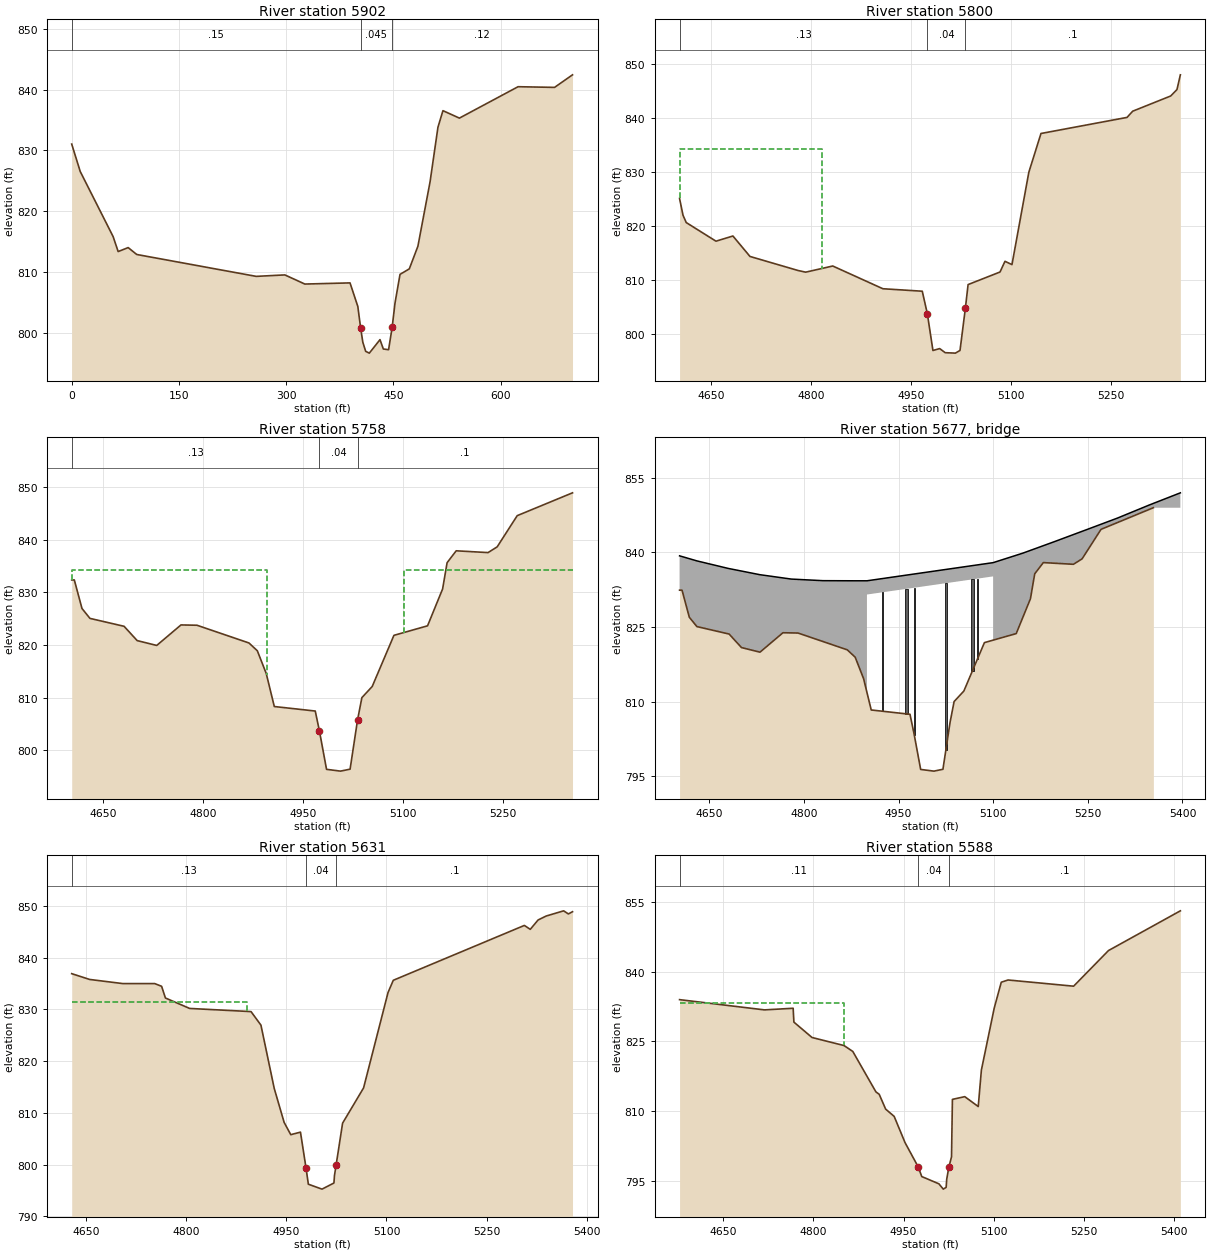
Type RM Length L Ch R = 1 ,5902    ,102,102,102
XS GIS Cut Line= 2
1551186.417496921094302.36684743 1550486.40119381094275.80076382
#Sta/Elev= 30
       0  831.05   11.93  826.55   57.96  815.87   64.96  813.42   78.97  814.07
   90.98  812.94   258.1  809.35  298.13  809.59  326.15  808.09   389.3  808.28
  400.21  804.42  404.21  800.83  407.21  798.55  411.21  797.05   416.3  796.76
  431.23  798.97  435.89  797.44  443.24  797.32  448.24  800.99  452.24  804.99
  459.25  809.68  472.22  810.58  484.27   814.3  501.28  824.87  512.29  833.81
  519.29  836.53  542.31  835.31  624.37  840.46   675.4  840.35  700.52  842.41
#Mann= 3 ,-1,0
       0     .15       0  404.21    .045       0  448.24     .12       0
Bank Sta=404.21,448.24
XS Rating Curve= 0 ,0
Exp/Cntr(USF)=0,0
Exp/Cntr=0.3,0.1

Type RM Length L Ch R = 1 ,5800    ,42,42,42
BEGIN DESCRIPTION:
Georges Creek 11.5
END DESCRIPTION:
XS GIS Cut Line= 2
      1551170.49       1094192.6    1550419.6349    1094182.1911
#Sta/Elev= 30
    4603  825.18    4603  825.16  4608.2  822.06    4613  820.71  4657.6  817.26
    4683  818.22  4708.6  814.43  4780.6  811.83  4792.1  811.52  4832.7  812.66
  4907.8  808.45  4966.9  807.99  4974.5  803.83  4982.9  797.01    4993  797.36
  5001.3   796.6  5016.6  796.52  5023.5  797.02  5031.6   804.9  5035.6  809.22
  5083.5  811.55  5090.9  813.53  5101.4  812.92  5126.7  830.04  5144.9  837.21
  5273.9  840.19  5282.4  841.34  5339.4  844.16  5348.8  845.35  5353.9  848.08
#Mann= 3 ,-1,0
    4603     .13       0  4974.5     .04       0  5031.6      .1       0
#XS Ineff= 2 , 0
       0    4816  834.26    5184       0   837.8
Permanent Ineff=
       F       F
Bank Sta=4974.5,5031.6
XS Rating Curve= 0 ,0
Exp/Cntr=0.5,0.3

Type RM Length L Ch R = 1 ,5758    ,127,127,127
BEGIN DESCRIPTION:
Georges Creek 11.5
END DESCRIPTION:
XS GIS Cut Line= 2
    1551171.0722     1094150.604     1550420.217    1094140.1951
#Sta/Elev= 30
    4603  832.37 4606.91  832.37 4618.43  826.94 4630.42  825.06 4681.53  823.56
 4701.16  820.84 4730.48  819.92 4766.87  823.82 4790.84  823.76 4868.79  820.39
 4881.33  818.91 4894.71  814.58 4906.78  808.31 4968.19  807.45  4974.5  803.62
 4985.11  796.37 5006.02  796.03 5020.42   796.4  5031.6  805.75  5038.1     810
  5053.6  812.12 5086.16  821.84 5136.57  823.65 5159.13  830.65 5165.88  835.65
 5179.53  837.91 5227.28  837.57 5240.96  838.66 5271.01  844.59 5353.93  848.93
#Mann= 3 ,-1,0
    4603     .13       0  4974.5     .04       0  5031.6      .1       0
#XS Ineff= 2 , 0
       0 4895.27  834.26    5101       0  834.26
Permanent Ineff=
       F       F
Bank Sta=4974.5,5031.6
XS Rating Curve= 0 ,0
Exp/Cntr=0.5,0.3

Type RM Length L Ch R = 3 ,5677    ,,,
BEGIN DESCRIPTION:
US Hwy 123 (Georges Cr.) - TOR
Structure ID: LDS_GC_03
Approximate Survey Structure
END DESCRIPTION:
Bridge Culvert--1,0,-1,-1, 0
Deck Dist Width WeirC Skew NumUp NumDn MinLoCord MaxHiCord MaxSubmerge Is_Ogee
1,125,3,0, 20, 20, , , , 0, 1,1,,
    4603 4630.26 4630.73 4680.33 4730.12 4780.09  4830.3  4883.7    4900    4900
    5100    5100 5146.87 5196.91 5246.78 5246.78 5297.07 5297.07 5346.71 5396.73
 839.271 838.263 838.248 836.737 835.487 834.602 834.282 834.257 834.257 834.257
 837.904 837.904 839.803 842.112 844.467 844.467 846.856 846.856 849.443 851.924
                                                                           831.5
  835.14
    4603 4630.26 4630.73 4680.33 4730.12 4780.09  4830.3  4883.7    4900    4900
    5100    5100 5146.87 5196.91 5246.78 5246.78 5297.07 5297.07 5346.71 5396.73
 839.271 838.263 838.248 836.737 835.487 834.602 834.282 834.257 834.257 834.257
 837.904 837.904 839.803 842.112 844.467 844.467 846.856 846.856 849.443 851.924
                                                                           831.5
  835.14
Pier Skew, UpSta & Num, DnSta & Num=  ,4925, 2 ,4925, 2 , 0 , 0 , 0 ,0,0
    2.33    2.33
  808.63     832
    2.33    2.33
  810.79     832
Pier Skew, UpSta & Num, DnSta & Num=  ,4962, 2 ,4962, 2 , 0 , 0 , 0 ,,
       5       5
     800     833
       5       5
     800     833
Pier Skew, UpSta & Num, DnSta & Num=  ,4975, 2 ,4975, 2 , 0 , 0 , 0 ,0,0
    2.33    2.33
  805.77     833
    2.33    2.33
  805.52     833
Pier Skew, UpSta & Num, DnSta & Num=  ,5025, 2 ,5025, 2 , 0 , 0 , 0 ,0,0
    2.33    2.33
  805.77   834.6
    2.33    2.33
  805.52   834.6
Pier Skew, UpSta & Num, DnSta & Num=  ,5067, 2 ,5067, 2 , 0 , 0 , 0 ,,
       5       5
     800     835
       5       5
     800     835
Pier Skew, UpSta & Num, DnSta & Num=  ,5075, 2 ,5075, 2 , 0 , 0 , 0 ,0,0
    2.33    2.33
  809.44   835.6
    2.33    2.33
  815.52   835.6
Abutment Skew #Up #Dn= , 10 , 10
    4900 4902.39 4904.05 4907.63 4908.73 4911.98 4923.34 4925.11 4929.03 4941.87
 830.465 830.465  827.77 826.686 826.475 824.555 817.377  816.54 814.314 808.123
    4900 4902.39 4904.05 4907.63 4908.73 4911.98 4923.34 4925.11 4929.03 4941.87
 830.465 830.465  827.77 826.686 826.475 824.555 817.377  816.54 814.314 808.123
Abutment Skew #Up #Dn= , 8 , 8
    5054 5054.43 5060.64 5063.99 5072.63 5074.05 5075.51    5100
     810  811.08   816.1  818.38  823.04  823.92  824.56  833.04
    5054 5054.43 5060.64 5063.99 5072.63 5074.05 5075.51    5100
     810  811.08   816.1  818.38  823.04  823.92  824.56  833.04
BR Coef=-1 ,-1 , 0 ,1.25, 0 ,,,0.8,0,2,0,
WSPro=,,,, 1 ,,,, 0 ,,,, 0 ,,,,-1 ,-1 ,-1 , 0 , 0 , 0 , 0 , 0
BC Design=,, 0 ,, 0 ,,,,,,
BC HTab HWMax=845.29
BC Use User HTab Curves=0
BC User HTab FreeFlow(D)= 0

Type RM Length L Ch R = 1 ,5631    ,43,43,43
BEGIN DESCRIPTION:
Georges Creek 11.5
END DESCRIPTION:
XS GIS Cut Line= 2
    1551172.8326    1094023.6162    1550421.9774    1094013.2073
#Sta/Elev= 30
    4628  836.91 4654.91  835.79  4704.8  834.99 4752.48  834.99  4762.8  834.47
 4768.53  832.21 4804.86  830.19 4896.89  829.58 4911.73  826.97 4931.69  814.73
 4946.53  808.17 4956.48   805.8 4971.03  806.29 4979.42  799.29 4982.84  796.23
 5003.29  795.28  5021.2  796.46 5021.99  797.91 5024.45  799.92 5034.19  808.03
 5065.63  814.83 5102.32  833.27  5110.2  835.63 5306.74  846.23 5315.57  845.47
 5327.31  847.28 5339.32  848.04 5365.62  849.05 5372.73  848.45 5378.93  848.88
#Mann= 3 ,-1,0
    4628     .13       0 4979.42     .04       0 5024.45      .1       0
#XS Ineff= 2 , 0
       0    4891   831.5    5123       0   831.5
Permanent Ineff=
       F       F
Bank Sta=4979.42,5024.45
XS Rating Curve= 0 ,0
Exp/Cntr=0.5,0.3

Type RM Length L Ch R = 1 ,5588    ,588,588,588
BEGIN DESCRIPTION:
Georges Creek 11.0
END DESCRIPTION:
XS GIS Cut Line= 3
       1551232.6      1093984.67      1550811.34      1093979.27
      1550398.19      1093990.08
#Sta/Elev= 30
  4576.8  833.96  4718.4  831.76  4766.1  832.114767.326 829.1354797.576 825.832
4850.913 824.1034865.506 822.8354904.031 814.1534909.492 813.6414920.245 810.455
4934.445 808.8964952.569 803.262  4974.5 798.0444980.428 795.9745008.932 794.421
  5016.3 793.2775021.068 793.6625022.041 795.413  5025.5 797.9675030.013 800.206
5031.502 812.5465052.072 813.1335074.556 811.0115079.796 818.8435101.183  832.15
 5112.93 837.7035124.261  838.18  5233.5  836.85  5291.6   844.5  5411.4  853.03
#Mann= 3 ,-1,0
  4576.8     .11       0  4974.5     .04       0  5025.5      .1       0
#XS Ineff= 2 , 0
       0    4850  833.26    5150       0  837.09
Permanent Ineff=
       F       F
Bank Sta=4974.5,5025.5
XS Rating Curve= 0 ,0
Exp/Cntr=0.5,0.3

--- GeorgesCreek.g09 (geometry) ---

Geom Title=Unrestricted
Program Version=6.10

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
River Reach=Georges Creek   ,Reach-1