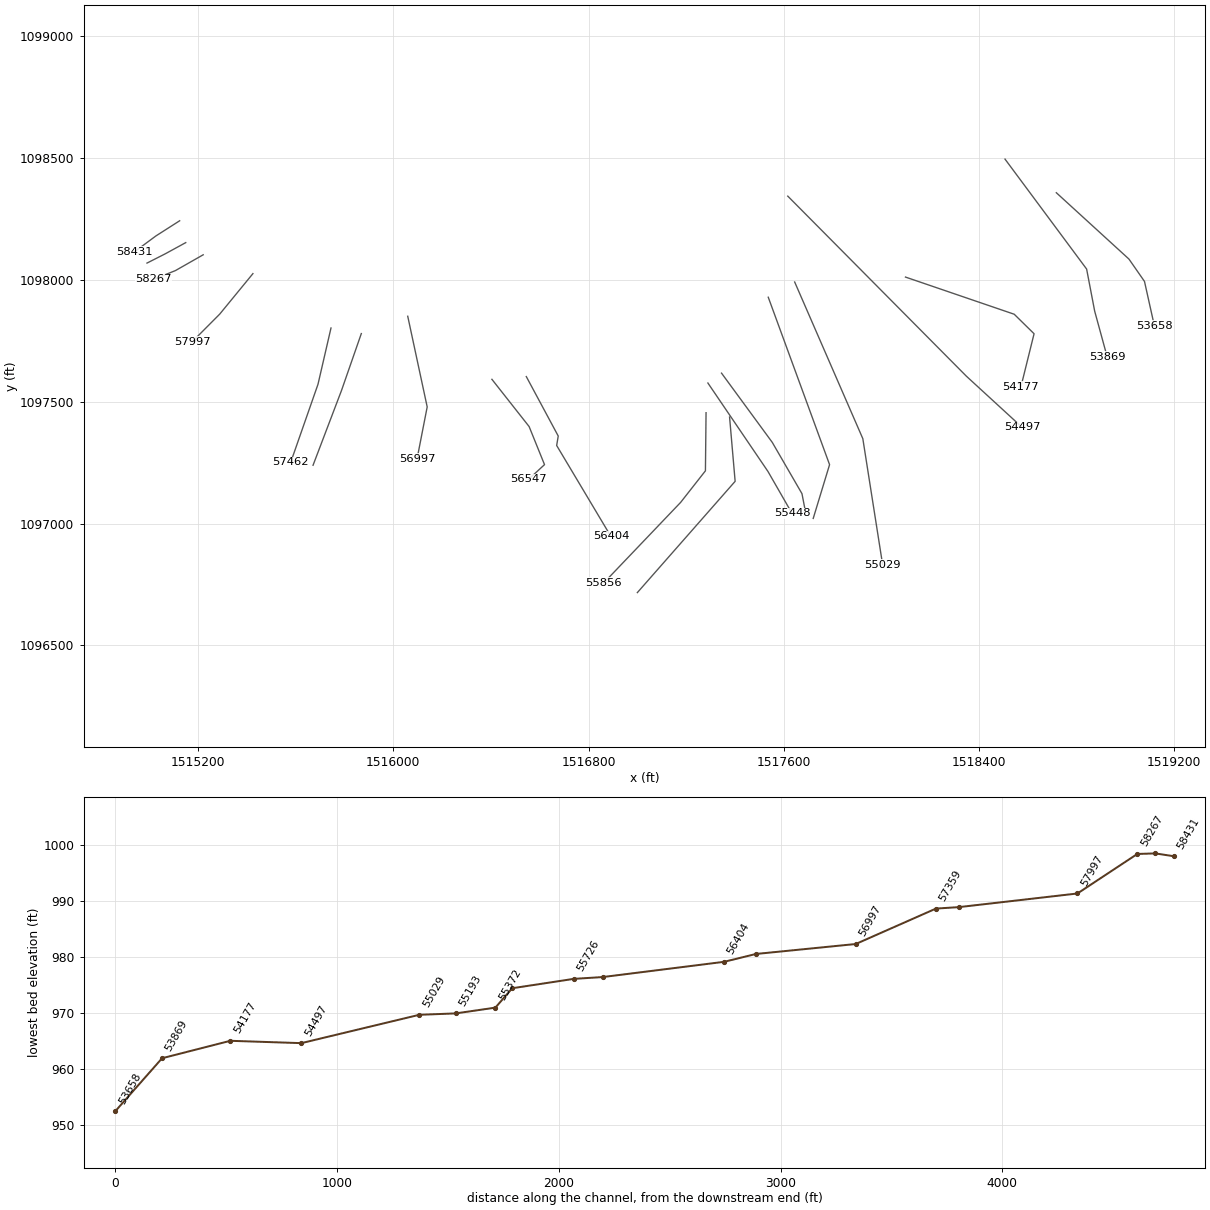
HEC-RAS study GeorgesCreek.prj: Georges Creek Limited Detail Study

--- GeorgesCreek.g09 (geometry) --- (continued)

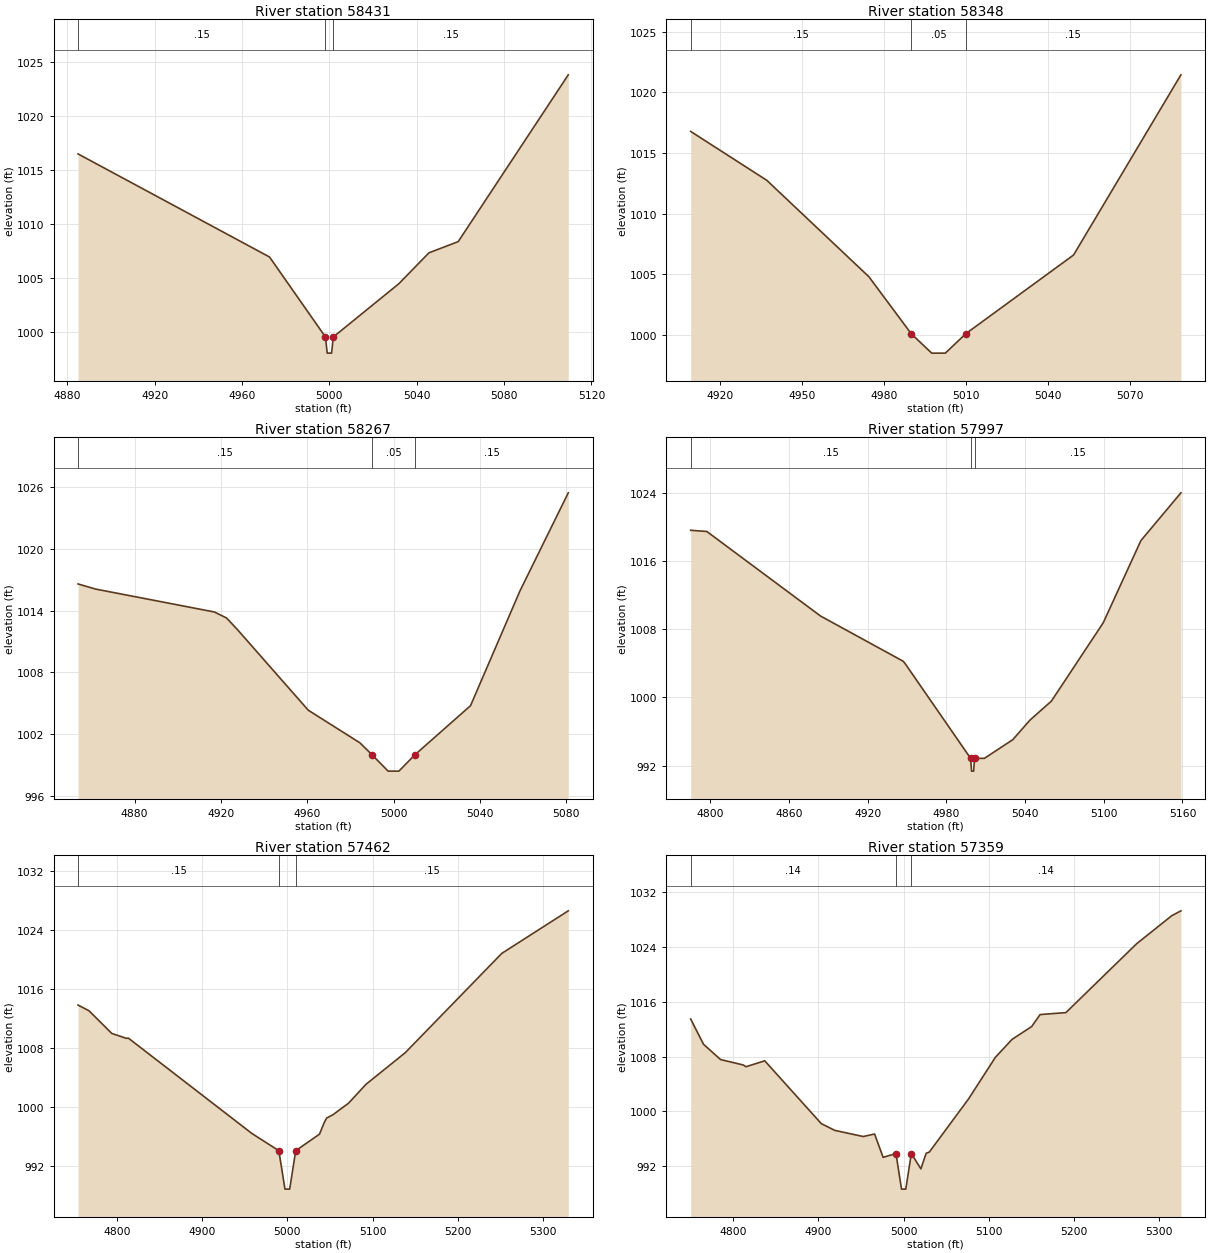
Type RM Length L Ch R = 1 ,58431   ,83,83,83
BEGIN DESCRIPTION:
Georges Creek 117.5
END DESCRIPTION:
XS GIS Cut Line= 3
      1515124.85      1098241.73      1515027.31      1098179.35
      1514939.98      1098114.71
#Sta/Elev= 10
  4884.9 1016.51  4972.6 1006.94  4998.2  999.52    4999  998.02    5001  998.02
  5001.8  999.52  5031.8 1004.46  5045.6 1007.33    5059 1008.37  5109.4 1023.85
#Mann= 3 ,-1,0
  4884.9     .15       0  4998.2     .05       0  5001.8     .15       0
Bank Sta=4998.2,5001.8
XS Rating Curve= 0 ,0
Exp/Cntr=0.3,0.1

Type RM Length L Ch R = 1 ,58348   ,81,81,81
BEGIN DESCRIPTION:
Georges Creek 117
END DESCRIPTION:
XS GIS Cut Line= 3
       1515149.8      1098152.13      1515064.74      1098105.63
      1514991.02      1098068.21
#Sta/Elev= 10
  4909.2 1016.78  4937.1 1012.75  4974.5 1004.81    4990 1000.12  4997.5  998.52
  5002.5  998.52    5010 1000.12  5048.5 1006.44  5049.5 1006.61  5088.8 1021.44
#Mann= 3 ,-1,0
  4909.2     .15       0    4990     .05       0    5010     .15       0
#XS Ineff= 2 , 0
Permanent Ineff=
       F       F
Bank Sta=4990,5010
XS Rating Curve= 0 ,0
Exp/Cntr=0.3,0.1

Type RM Length L Ch R = 1 ,58267   ,270,270,270
BEGIN DESCRIPTION:
Georges Creek 116.5
END DESCRIPTION:
XS GIS Cut Line= 3
      1515221.26      1098102.23      1515107.84      1098037.58
      1515018.24      1098001.29
#Sta/Elev= 14
  4853.8 1016.58    4862 1016.08    4917 1013.86  4922.6 1013.28  4927.5 1012.19
  4960.5 1004.33  4984.4 1001.17    4990 1000.02  4997.5  998.42  5002.5  998.42
    5010 1000.02  5035.7 1004.77  5058.6  1015.9    5081 1025.42
#Mann= 3 ,-1,0
  4853.8     .15       0    4990     .05       0    5010     .15       0
#XS Ineff= 2 , 0
Permanent Ineff=
       F       F
Bank Sta=4990,5010
XS Rating Curve= 0 ,0
Exp/Cntr=0.3,0.1

Type RM Length L Ch R = 1 ,57997   ,535,535,535
BEGIN DESCRIPTION:
Georges Creek 116.0
END DESCRIPTION:
XS GIS Cut Line= 3
        1515425.        1098025.      1515288.85      1097858.76
      1515176.88      1097746.14
#Sta/Elev= 16
  4785.1 1019.58  4797.4 1019.44  4884.1 1009.53  4947.1 1004.23  4948.5 1003.97
  4998.5  992.85  4999.2  991.35  5000.8  991.35  5001.5  992.85    5009  992.85
  5030.6  995.03  5043.8  997.34  5060.1  999.56  5099.6 1008.74  5128.3 1018.37
  5158.8 1023.97
#Mann= 3 ,-1,0
  4785.1     .15       0  4998.5     .05       0  5001.5     .15       0
Bank Sta=4998.5,5001.5
XS Rating Curve= 0 ,0
Exp/Cntr=0.3,0.1

Type RM Length L Ch R = 1 ,57462   ,103,103,103
BEGIN DESCRIPTION:
Georges Creek 115.0
END DESCRIPTION:
XS GIS Cut Line= 3
      1515744.85      1097801.92       1515691.6      1097571.18
      1515580.04       1097251.7
#Sta/Elev= 19
  4754.5 1013.82  4767.3 1013.05  4794.1 1009.98    4811 1009.32  4813.6 1009.34
  4958.5  996.44  4990.1  994.11  4997.3  988.91  5002.8  988.91  5009.9  994.11
  5037.8  996.35  5043.2  997.88  5046.2  998.53  5053.5  998.97    5072 1000.55
  5092.3 1003.09  5138.4 1007.37  5251.7 1020.81  5329.7 1026.57
#Mann= 3 ,-1,0
  4754.5     .15       0  4990.1     .05       0  5009.9     .15       0
#XS Ineff= 2 , 0
Permanent Ineff=
       F       F
Bank Sta=4990.1,5009.9
XS Rating Curve= 0 ,0
Exp/Cntr=0.3,0.1

Type RM Length L Ch R = 1 ,57359   ,362,362,362
BEGIN DESCRIPTION:
Georges Creek 114.5
END DESCRIPTION:
XS GIS Cut Line= 3
      1515869.09       1097779.1      1515787.95      1097545.83
      1515671.32      1097239.02
#Sta/Elev= 27
  4750.1 1013.49  4765.2  1009.8  4785.2 1007.57  4812.1 1006.77  4814.9 1006.52
    4837 1007.39  4903.4  998.21  4919.2  997.23  4952.6  996.33  4965.9   996.7
  4975.9  993.29    4991  993.85  4997.5  988.65  5002.5  988.65    5009  993.85
  5020.2  991.61  5026.4  993.89  5030.1  994.06  5076.3 1001.85  5107.5 1007.88
  5127.2 1010.52  5150.2 1012.39  5160.1 1014.14  5190.4 1014.43  5273.4 1024.49
  5314.6 1028.58  5325.3 1029.29
#Mann= 3 ,-1,0
  4750.1     .14       0    4991     .05       0    5009     .14       0
#XS Ineff= 2 , 0
Permanent Ineff=
       F       F
Bank Sta=4991,5009
XS Rating Curve= 0 ,0
Exp/Cntr=0.3,0.1

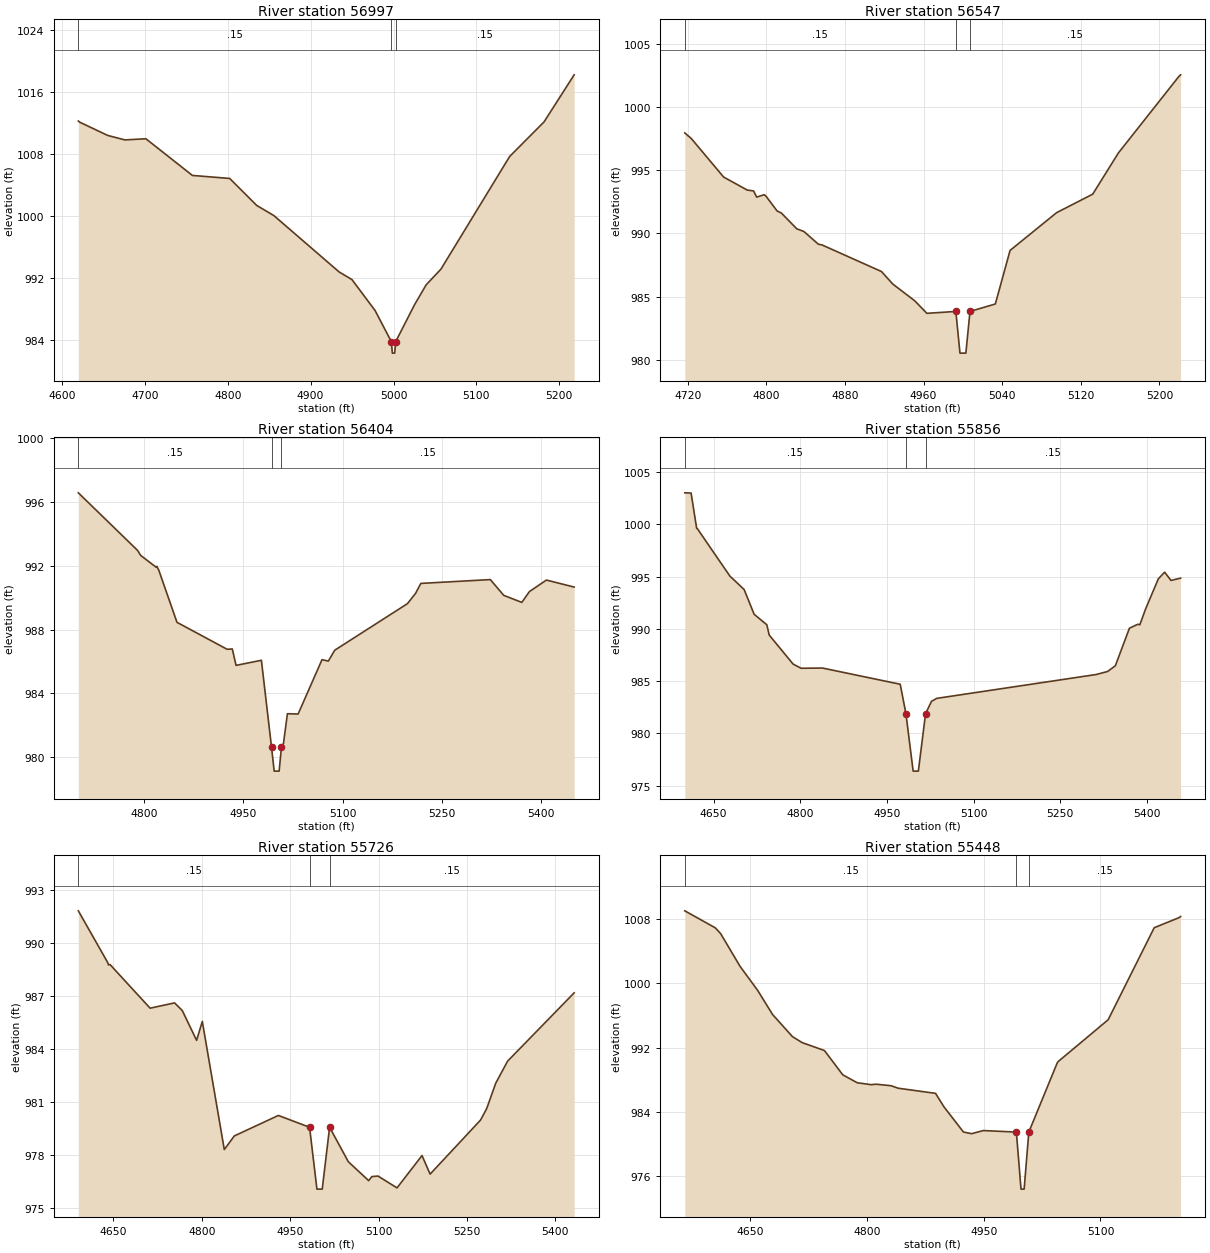
Type RM Length L Ch R = 1 ,56997   ,450,450,450
BEGIN DESCRIPTION:
Georges Creek 114.0
END DESCRIPTION:
XS GIS Cut Line= 3
      1516059.26       1097850.1      1516138.96       1097478.3
      1516097.29      1097264.38
#Sta/Elev= 22
  4619.8  1012.3  4621.7 1012.14  4655.2 1010.44  4675.9 1009.86  4701.3 1010.01
  4757.4 1005.27  4802.4 1004.88  4834.9  1001.4  4855.7 1000.08  4934.4   992.8
  4949.9  991.81  4977.8  987.81  4997.3  983.81  4998.6  982.31  5001.4  982.31
  5002.7  983.81  5025.3  988.55  5039.4  991.14  5057.2  993.16  5140.1 1007.72
  5181.6 1012.19  5217.9 1018.27
#Mann= 3 ,-1,0
  4619.8     .15       0  4997.3     .05       0  5002.7     .15       0
Bank Sta=4997.3,5002.7
XS Rating Curve= 0 ,0
Exp/Cntr=0.3,0.1

Type RM Length L Ch R = 1 ,56547   ,143,143,143
BEGIN DESCRIPTION:
Georges Creek 113.0
END DESCRIPTION:
XS GIS Cut Line= 4
       1516404.1      1097591.47      1516556.52      1097397.78
      1516619.62      1097241.56       1516553.7      1097180.71
#Sta/Elev= 30
  4716.9  997.96  4723.5  997.52  4756.4  994.47  4780.4  993.44  4786.9  993.37
  4790.1  992.88  4797.7  993.07  4799.4  992.97  4810.9  991.78  4815.2  991.62
  4830.9  990.37  4838.1  990.16  4852.9  989.15  4856.4   989.1  4917.1  986.99
  4928.6     986    4951  984.67  4963.3  983.68  4992.8  983.83    4997  980.53
    5003  980.53  5007.2  983.83    5033  984.42    5048  988.66  5095.4  991.65
  5131.8   993.1  5132.1  993.11  5158.3  996.38  5219.8 1002.43  5221.6 1002.56
#Mann= 3 ,-1,0
  4716.9     .15       0  4992.8     .05       0  5007.2     .15       0
#XS Ineff= 2 , 0
Permanent Ineff=
       F       F
Bank Sta=4992.8,5007.2
XS Rating Curve= 0 ,0
Exp/Cntr=0.3,0.1

Type RM Length L Ch R = 1 ,56404   ,548,548,548
BEGIN DESCRIPTION:
Georges Creek 112.5
END DESCRIPTION:
XS GIS Cut Line= 4
      1516544.98      1097602.71      1516675.84      1097358.83
      1516669.38      1097320.07      1516891.25      1096947.79
#Sta/Elev= 30
  4700.5  996.58  4789.8  992.98  4794.9  992.65  4818.3  991.91  4819.1  991.97
  4822.2  991.72  4849.6  988.46  4925.4  986.77  4933.2  986.79  4938.9  985.76
  4977.2  986.08  4992.5  980.63  4996.5  979.13    5004  979.13  5007.5  980.63
  5010.6  980.87  5016.5  982.73  5032.7  982.71  5068.8  986.12  5078.4  986.03
    5088  986.71  5197.9  989.63  5210.1  990.27  5218.2   990.9  5323.2  991.14
  5343.5  990.15  5370.8  989.71  5382.3  990.39    5408  991.11  5449.9  990.67
#Mann= 3 ,-1,0
  4700.5     .15       0  4992.5     .05       0  5007.5     .15       0
#XS Ineff= 2 , 0
Permanent Ineff=
       F       F
Bank Sta=4992.5,5007.5
XS Rating Curve= 0 ,0
Exp/Cntr=0.3,0.1

Type RM Length L Ch R = 1 ,55856   ,130,130,130
BEGIN DESCRIPTION:
Georges Creek 112.0
END DESCRIPTION:
XS GIS Cut Line= 4
      1517281.41      1097454.55      1517278.87       1097216.2
      1517177.45      1097086.89      1516863.04      1096757.26
#Sta/Elev= 30
  4600.2 1003.02  4611.1    1003  4620.7  999.63    4622  999.59  4678.2  995.06
  4702.9  993.77  4720.3   991.4  4742.2   990.4  4746.4  989.41  4787.7  986.64
  4801.4  986.24  4838.6  986.26  4973.1  984.71    4983   981.9  4995.5   976.4
  5004.5   976.4    5017   981.9  5027.3  983.08  5036.4  983.36  5312.2  985.64
  5332.1  985.93  5345.5  986.48  5369.9  990.07  5384.5  990.45  5387.9   990.4
    5398  991.93  5419.9  994.79  5430.8  995.43  5441.9  994.64  5458.5  994.86
#Mann= 3 ,-1,0
  4600.2     .15       0    4983     .05       0    5017     .15       0
#XS Ineff= 2 , 0
Permanent Ineff=
       F       F
Bank Sta=4983,5017
XS Rating Curve= 0 ,0
Exp/Cntr=0.3,0.1

Type RM Length L Ch R = 1 ,55726   ,278,278,278
BEGIN DESCRIPTION:
Georges Creek 111.5
END DESCRIPTION:
XS GIS Cut Line= 3
      1517377.76       1097436.8      1517400.58       1097173.1
      1516999.96       1096716.7
#Sta/Elev= 28
  4590.6  991.83  4640.5   988.9  4641.8  988.77  4644.4  988.79  4712.4  986.32
    4754  986.62  4767.1  986.18  4791.3   984.5    4801  985.57  4838.3  978.32
  4855.3  979.09  4930.1  980.25    4983  979.58  4995.5  976.08  5004.5  976.08
    5017  979.58  5048.8  977.63  5083.3  976.56  5088.7  976.79  5099.1  976.82
  5131.4  976.15  5173.8  977.98  5187.6  976.93  5273.2  979.99  5283.6  980.64
    5299  982.08    5319  983.32    5432  987.19
#Mann= 3 ,-1,0
  4590.6     .15       0    4983     .05       0    5017     .15       0
#XS Ineff= 2 , 0
Permanent Ineff=
       F       F
Bank Sta=4983,5017
XS Rating Curve= 0 ,0
Exp/Cntr=0.3,0.1

Type RM Length L Ch R = 1 ,55448   ,76,76,76
BEGIN DESCRIPTION:
Georges Creek 111.0
END DESCRIPTION:
XS GIS Cut Line= 3
      1517289.01      1097576.26      1517534.97      1097213.67
      1517633.85      1097041.25
#Sta/Elev= 30
  4566.1 1009.04  4605.3 1006.92  4612.1 1006.21  4637.1 1002.13  4659.7  999.14
  4678.9  996.13  4704.4  993.38    4717  992.63  4745.5  991.65    4769  988.63
  4787.6  987.64  4805.6   987.4  4811.9  987.46  4831.1  987.27  4840.2  986.96
  4888.2  986.32  4898.8  984.67    4924  981.51  4934.5   981.3  4949.6  981.69
    4992   981.5    4998   974.4    5002   974.4    5008   981.5  5044.6  990.13
  5046.1  990.31  5109.9  995.48  5169.1 1006.94  5200.5 1008.17    5203 1008.33
#Mann= 3 ,-1,0
  4566.1     .15       0    4992     .05       0    5008     .15       0
#XS Ineff= 2 , 0
Permanent Ineff=
       F       F
Bank Sta=4992,5008
XS Rating Curve= 0 ,0
Exp/Cntr=0.3,0.1

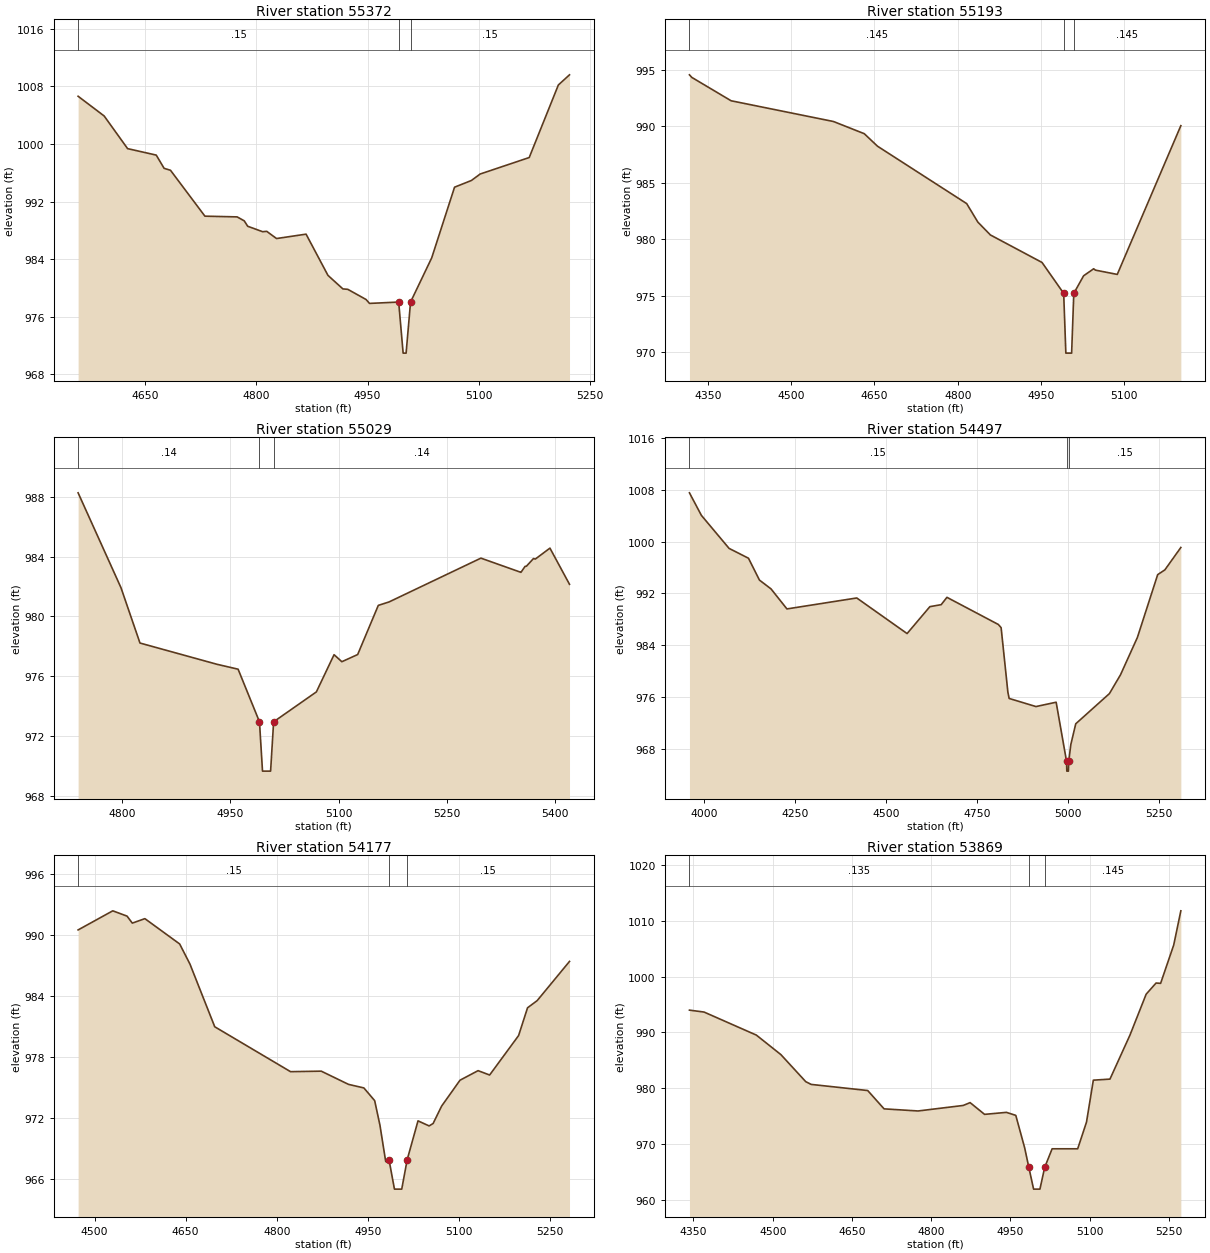
Type RM Length L Ch R = 1 ,55372   ,179,179,179
BEGIN DESCRIPTION:
Georges Creek 110.5
END DESCRIPTION:
XS GIS Cut Line= 4
       1517344.8      1097616.83      1517552.71      1097332.84
      1517674.42      1097122.39       1517687.1      1097056.46
#Sta/Elev= 30
    4560 1006.64  4595.1  1003.9  4626.7  999.36  4665.3  998.46  4675.9  996.62
  4684.5  996.35  4730.9  989.97  4774.3  989.87  4783.9  989.32  4788.5  988.57
  4808.7  987.81  4814.2  987.86  4827.4  986.86  4867.2  987.47  4896.7  981.74
  4916.8  979.86  4923.4   979.8    4948  978.39  4952.7  977.84    4992  978.03
    4998  970.93    5002  970.93    5008  978.03  5036.5  984.17  5067.3     994
    5090  994.93  5101.8  995.83  5167.9  998.12  5207.2 1008.21  5222.2 1009.62
#Mann= 3 ,-1,0
    4560     .15       0    4992     .05       0    5008     .15       0
#XS Ineff= 2 , 0
Permanent Ineff=
       F       F
Bank Sta=4992,5008
XS Rating Curve= 0 ,0
Exp/Cntr=0.3,0.1

Type RM Length L Ch R = 1 ,55193   ,164,164,164
BEGIN DESCRIPTION:
Georges Creek 110.0
END DESCRIPTION:
XS GIS Cut Line= 3
      1517536.27      1097928.13      1517787.49      1097241.47
       1517720.5      1097020.96
#Sta/Elev= 19
  4316.9  994.58  4321.2  994.35  4391.9  992.28  4576.3  990.44  4631.7  989.36
  4655.6  988.25  4816.2  983.16  4836.3  981.52  4858.9  980.38  4951.9  977.94
  4990.9   975.2  4994.8   969.9  5005.2   969.9  5009.1   975.2  5026.8  976.76
  5044.9  977.38  5048.1  977.26  5087.4  976.88  5201.9  990.07
#Mann= 3 ,-1,0
  4316.9    .145       0  4990.9    .049       0  5009.1    .145       0
#XS Ineff= 2 , 0
Permanent Ineff=
       F       F
Bank Sta=4990.9,5009.1
XS Rating Curve= 0 ,0
Exp/Cntr=0.3,0.1

Type RM Length L Ch R = 1 ,55029   ,532,532,532
BEGIN DESCRIPTION:
Georges Creek 109.5
END DESCRIPTION:
XS GIS Cut Line= 3
      1517644.46      1097990.65      1517923.68      1097348.14
      1518004.74      1096831.74
#Sta/Elev= 24
    4739  988.27  4798.4  981.92  4824.7  978.22  4931.2   976.8  4960.6  976.47
  4990.2  972.95  4994.4  969.65  5005.6  969.65  5009.8  972.95    5069  974.95
  5093.5  977.44  5104.3  976.97  5126.2  977.45  5154.8  980.74  5169.7  980.97
  5296.9   983.9  5352.3  982.95  5352.8  982.98  5358.1  983.35  5359.9  983.36
  5369.7  983.87  5372.3  983.84  5392.5  984.57  5419.6  982.15
#Mann= 3 ,-1,0
    4739     .14       0  4990.2    .048       0  5009.8     .14       0
#XS Ineff= 2 , 0
Permanent Ineff=
       F       F
Bank Sta=4990.2,5009.8
XS Rating Curve= 0 ,0
Exp/Cntr=0.3,0.1

Type RM Length L Ch R = 1 ,54497   ,320,320,320
BEGIN DESCRIPTION:
Georges Creek 109.0
END DESCRIPTION:
XS GIS Cut Line= 3
      1517616.27      1098342.77       1518347.8      1097604.42
      1518576.02      1097394.72
#Sta/Elev= 30
  3960.6 1007.51  3993.3 1004.04  4069.4  998.94  4122.7  997.42  4152.8  994.05
  4184.6  992.69  4228.3   989.6    4420  991.29  4558.2   985.8  4620.8  989.95
  4651.9  990.26  4667.6  991.39  4808.8   987.2  4816.4  986.71    4835  976.75
  4838.5  975.79  4912.1  974.54  4967.5  975.21  4996.1  966.08  4996.8  964.58
  5001.1  964.58  5002.1  966.08  5007.8  968.68  5021.3  971.88  5113.8  976.54
  5144.3  979.45  5190.6   985.2  5246.3  994.89  5266.1  995.63  5309.9  999.08
#Mann= 3 ,-1,0
  3960.6     .15       0  4996.1     .05       0  5002.1     .15       0
Bank Sta=4996.1,5002.1
XS Rating Curve= 0 ,0
Exp/Cntr=0.3,0.1

Type RM Length L Ch R = 1 ,54177   ,308,308,308
BEGIN DESCRIPTION:
Georges Creek 108.0
END DESCRIPTION:
XS GIS Cut Line= 4
      1518098.47      1098010.81      1518543.93      1097858.39
      1518625.26       1097778.4      1518571.28      1097560.32
#Sta/Elev= 30
  4472.8  990.51  4529.9  992.39  4553.4  991.87  4562.1  991.18  4582.8  991.62
  4640.1  989.13    4657  987.16  4697.9  980.98  4822.8  976.56  4873.4  976.61
  4918.3  975.31  4943.6  974.96  4961.4  973.71  4970.1  971.29  4979.6  967.71
    4985   967.9    4994     965    5006     965    5015   967.9  5032.8  971.72
  5051.1  971.22  5057.7  971.46  5071.7  973.17    5102  975.72  5131.8  976.66
  5150.8  976.23  5198.5  980.11  5213.3  982.85  5229.1  983.55  5282.4  987.41
#Mann= 3 ,-1,0
  4472.8     .15       0    4985     .05       0    5015     .15       0
#XS Ineff= 2 , 0
Permanent Ineff=
       F       F
Bank Sta=4985,5015
XS Rating Curve= 0 ,0
Exp/Cntr=0.3,0.1

Type RM Length L Ch R = 1 ,53869   ,211,211,211
BEGIN DESCRIPTION:
Georges Creek 107.9
END DESCRIPTION:
XS GIS Cut Line= 4
      1518506.19      1098494.64      1518840.58      1098043.69
      1518873.58      1097871.06       1518924.5      1097684.66
#Sta/Elev= 30
  4342.4  994.01    4370  993.67  4469.1  989.53  4515.5  986.03  4562.6  981.17
  4572.8  980.68  4679.9  979.58  4710.9  976.29  4775.3  975.91  4860.7   976.9
  4873.8  977.41  4901.2   975.3  4942.5  975.66  4960.3  975.12  4977.1  969.29
    4985  965.78    4994  961.88    5006  961.88    5015  965.78  5029.1  969.12
  5077.5  969.12  5094.2  973.92  5107.1  981.44  5138.6  981.63  5176.5  989.54
  5207.1  996.87  5225.9  998.88  5234.5  998.82  5259.3  1005.7  5272.8 1011.84
#Mann= 3 ,-1,0
  4342.4    .135       0    4985     .05       0    5015    .145       0
#XS Ineff= 2 , 0
Permanent Ineff=
       F       F
Bank Sta=4985,5015
XS Rating Curve= 0 ,0
Exp/Cntr=0.3,0.1

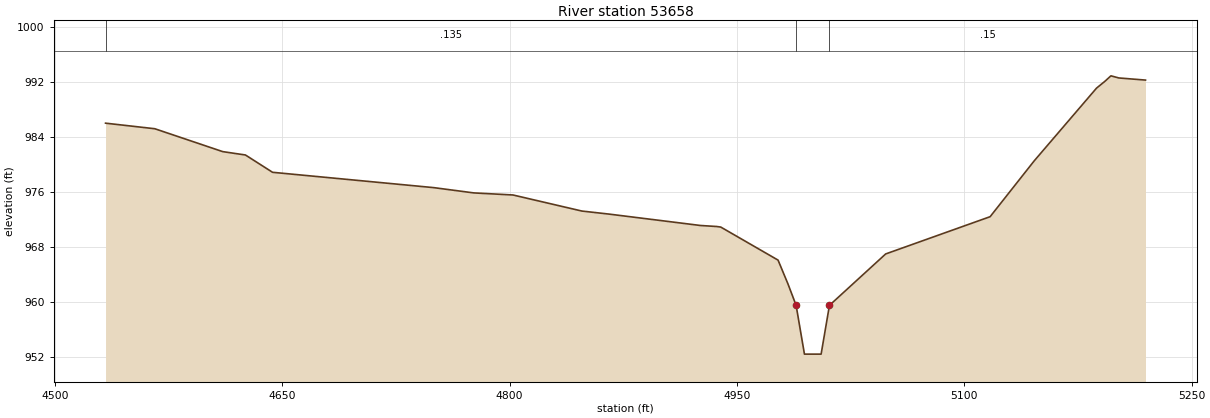
Type RM Length L Ch R = 1 ,53658   ,85,85,85
BEGIN DESCRIPTION:
Georges Creek 107.7
END DESCRIPTION:
XS GIS Cut Line= 4
      1518716.49       1098356.7      1519014.06      1098084.56
      1519077.65        1097993.      1519118.34      1097809.88
#Sta/Elev= 27
  4533.4  986.01  4565.9   985.2  4610.7  981.87  4625.7  981.38  4643.6  978.86
  4749.9  976.63  4776.4  975.86  4802.2  975.56  4847.7  973.22  4865.9  972.77
  4925.9  971.12  4936.7  970.97  4939.3  970.89  4977.1  966.08  4983.6  962.63
    4989   959.5  4994.5   952.4  5005.5   952.4    5011   959.5  5048.1  966.98
    5117   972.4  5146.1  980.53  5187.2  991.11  5192.5  992.06  5196.7   992.9
  5201.9  992.59  5219.5  992.28
#Mann= 3 ,-1,0
  4533.4    .135       0    4989     .05       0    5011     .15       0
#XS Ineff= 2 , 0
Permanent Ineff=
       F       F
Bank Sta=4989,5011
XS Rating Curve= 0 ,0
Exp/Cntr=0.3,0.1