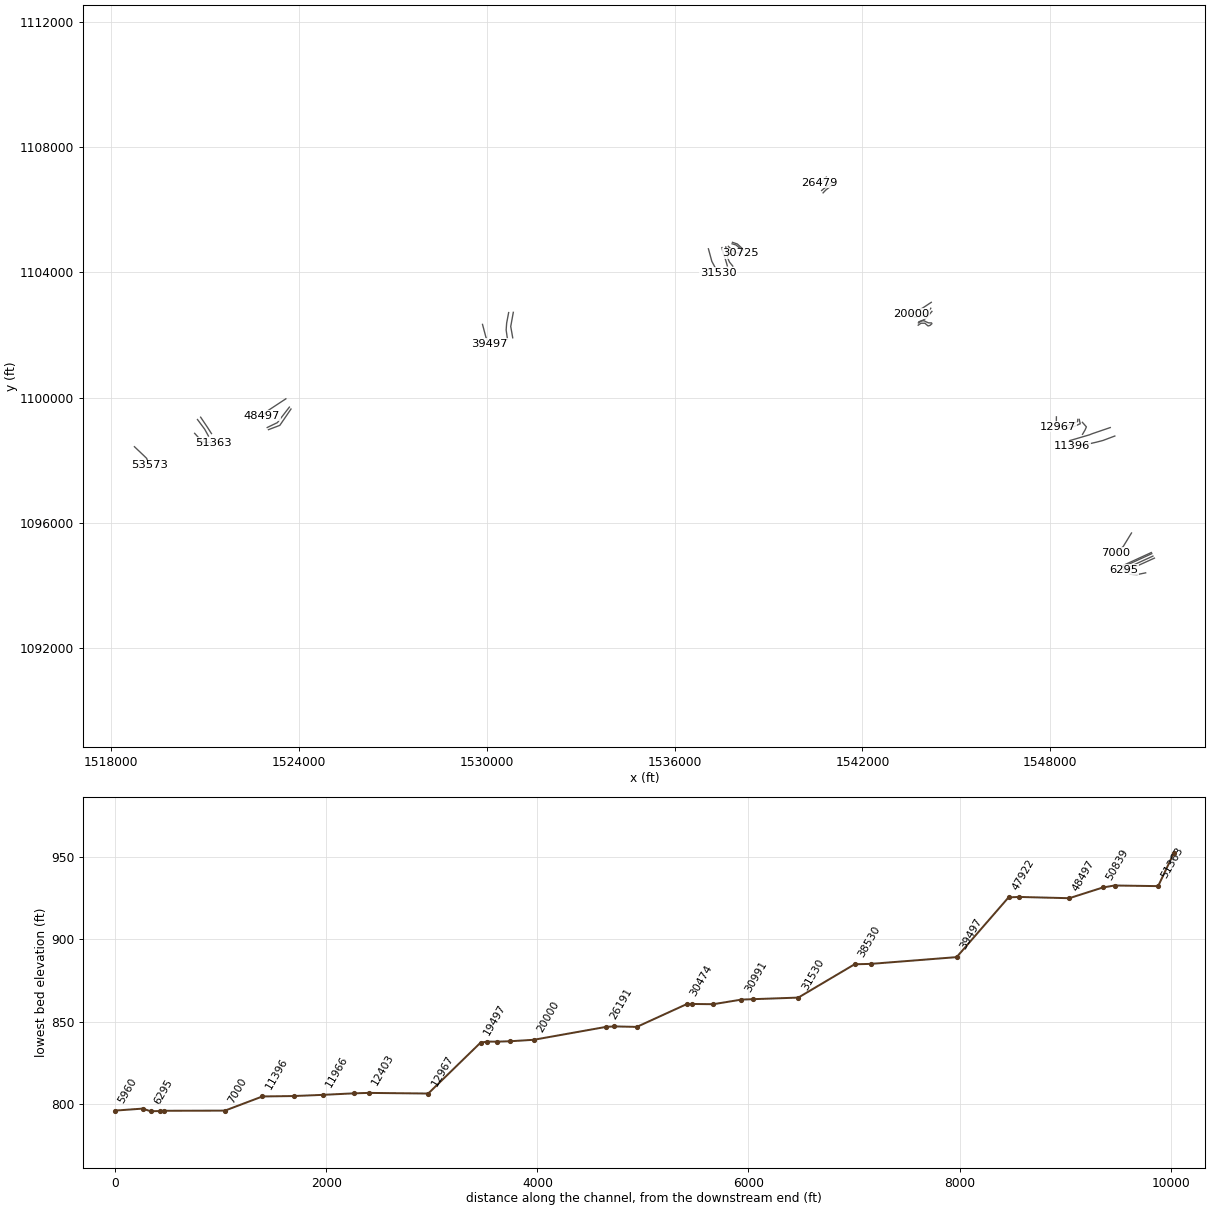
HEC-RAS study GeorgesCreek.prj: Georges Creek Limited Detail Study

--- GeorgesCreek.g09 (geometry) --- (continued)

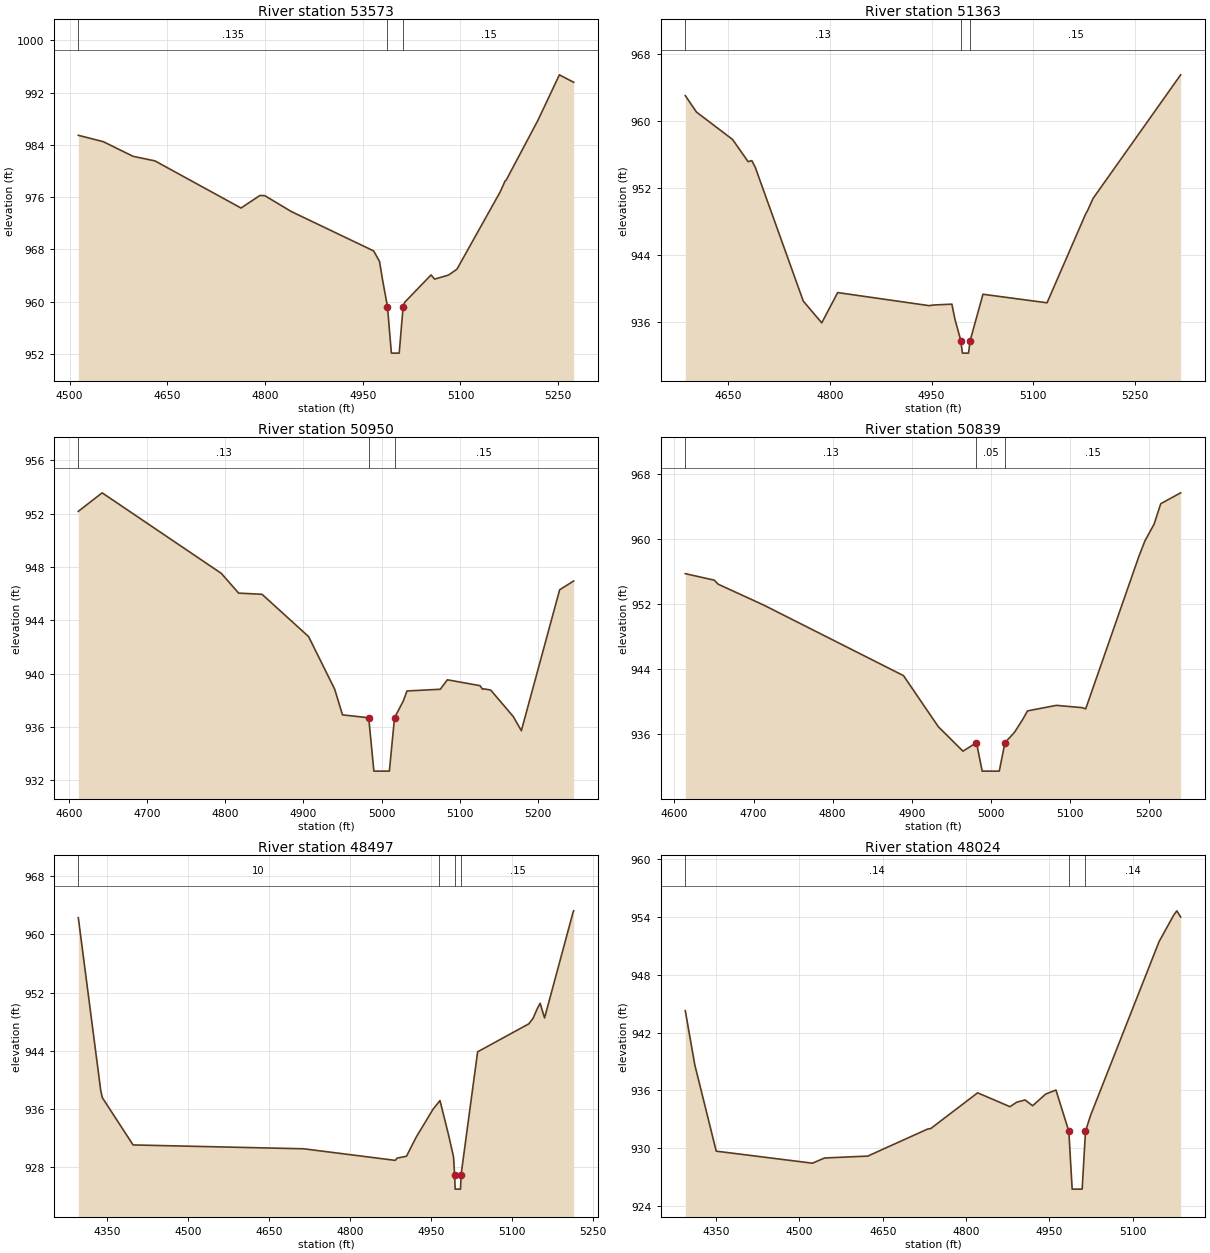
Type RM Length L Ch R = 1 ,53573   ,147,147,147
BEGIN DESCRIPTION:
Gedorges Creek 107.5
END DESCRIPTION:
XS GIS Cut Line= 4
      1518754.64      1098430.45      1519036.95       1098163.4
      1519146.32      1098056.59      1519222.61      1097830.23
#Sta/Elev= 27
  4513.4  985.46  4551.7  984.49  4597.4  982.25    4631  981.55  4763.2  974.34
  4792.2  976.26  4799.7  976.23  4840.6  973.79  4966.8  967.78  4975.8  966.17
  4980.7  963.21    4988  959.25    4994  952.15    5006  952.15    5012  959.25
  5014.5  959.93  5054.9  964.11  5060.4  963.47  5081.7  964.09  5094.6  964.98
  5160.9  976.79  5165.9  977.88  5168.4  978.46  5170.3  978.62    5219  987.77
  5251.9  994.71  5273.8  993.57
#Mann= 3 ,-1,0
  4513.4    .135       0    4988     .05       0    5012     .15       0
#XS Ineff= 2 , 0
Permanent Ineff=
       F       F
Bank Sta=4988,5012
XS Rating Curve= 0 ,0
Exp/Cntr=0.3,0.1

Type RM Length L Ch R = 1 ,51363   ,413,413,413
BEGIN DESCRIPTION:
Georges Creek 103.0
END DESCRIPTION:
XS GIS Cut Line= 3
      1520677.81      1098857.03      1520923.85      1098585.46
      1521285.95      1098552.96
#Sta/Elev= 24
  4587.1  963.02  4603.6  961.06  4656.8  957.79  4679.7  955.15  4685.1  955.27
  4690.2  954.48    4761  938.52  4788.2  935.93  4811.7  939.54  4946.4  937.98
  4953.6  938.06    4980  938.16  4984.4  936.39  4993.1  933.82  4995.5  932.32
  5004.5  932.32  5006.9  933.82  5024.8  939.05  5025.7  939.34  5120.2  938.32
  5177.1  948.91  5180.6  949.43    5188  950.76  5317.1   965.5
#Mann= 3 ,-1,0
  4587.1     .13       0  4993.1     .05       0  5006.9     .15       0
Bank Sta=4993.1,5006.9
XS Rating Curve= 0 ,0
Exp/Cntr=0.3,0.1

Type RM Length L Ch R = 1 ,50950   ,111,111,111
BEGIN DESCRIPTION:
Georges Creek 102.0
END DESCRIPTION:
XS GIS Cut Line= 4
      1520768.34      1099298.05      1520939.25      1099067.47
      1521000.45       1098984.7      1521117.89      1098771.37
#Sta/Elev= 24
  4612.1  952.18  4642.6  953.57    4795  947.53  4817.1  946.05  4847.1  945.96
  4906.6  942.79    4940  938.84    4950  936.92  4983.5   936.7  4990.1   932.7
  5009.9   932.7  5016.5   936.7  5027.8  937.97  5032.4  938.71    5075  938.84
  5084.1  939.55  5125.8  939.11  5129.1  938.84  5130.7  938.87  5139.5  938.78
  5168.3   936.8  5178.7  935.73  5227.7   946.3  5245.6  946.96
#Mann= 3 ,-1,0
  4612.1     .13       0  4983.5     .05       0  5016.5     .15       0
#XS Ineff= 2 , 0
Permanent Ineff=
       F       F
Bank Sta=4983.5,5016.5
XS Rating Curve= 0 ,0
Exp/Cntr=0.3,0.1

Type RM Length L Ch R = 1 ,50839   ,318,318,318
BEGIN DESCRIPTION:
Georges Creek 101.5
END DESCRIPTION:
XS GIS Cut Line= 3
      1520868.69      1099372.46      1521084.33      1099052.67
      1521214.32      1098849.99
#Sta/Elev= 22
  4613.7  955.75  4650.4  954.95  4655.4  954.45  4712.9  951.89  4889.7  943.22
  4933.7  936.95  4964.9  933.94    4982  934.99  4989.2  931.49  5010.8  931.49
    5018  934.99    5030  936.25  5040.7  937.88  5046.5  938.89    5083  939.57
  5115.5  939.29  5120.1  939.14  5187.3  957.85    5195  959.77  5206.6  961.83
    5215  964.34  5240.2  965.68
#Mann= 3 ,-1,0
  4613.7     .13       0    4982     .05       0    5018     .15       0
#XS Ineff= 2 , 0
Permanent Ineff=
       F       F
Bank Sta=4982,5018
XS Rating Curve= 0 ,0
Exp/Cntr=0.3,0.1

Type RM Length L Ch R = 1 ,48497   ,473,473,473
BEGIN DESCRIPTION:
Georges Creek 97.0
END DESCRIPTION:
XS GIS Cut Line= 3
      1523589.53      1099959.23      1522988.77      1099563.69
        1522825.        1099425.
#Sta/Elev= 27
    4297  962.29  4338.5  938.58  4341.4  937.58    4398  931.12  4398.9  931.07
  4714.5  930.54  4884.1  928.95  4887.5  929.26  4904.9  929.52  4922.7  932.11
  4954.2  935.99  4965.1  936.99    4967  937.16  4982.9  932.43  4992.1  929.42
    4994     927  4995.1     925    5005     925  5006.1     927  5036.7  943.86
  5131.6  947.71  5139.4  948.46  5147.1  949.78  5152.5  950.53  5160.7  948.52
  5213.8  963.11  5214.6  963.23
#Mann= 4 ,-1,0
    4297      10       0  4965.1     .15       0    4994     .05       0
  5006.1     .15       0
Bank Sta=4994,5006.1
XS Rating Curve= 0 ,0
Exp/Cntr=0.3,0.1

Type RM Length L Ch R = 1 ,48024   ,102,102,102
BEGIN DESCRIPTION:
Georges Creek 96.0
END DESCRIPTION:
XS GIS Cut Line= 3
      1523702.06      1099693.97      1523320.26      1099199.64
      1522994.72       1099042.9
#Sta/Elev= 25
  4294.5  944.27  4311.6  938.66  4350.2   929.7  4523.4  928.45  4545.3  928.99
  4623.8  929.19  4625.8  929.26  4731.5  932.01  4736.3  932.04  4820.8  935.75
  4879.1  934.31  4890.9  934.77  4906.2  935.01  4919.8  934.41  4943.3  935.62
  4961.8  936.04    4985  931.76    4991  925.76    5009  925.76    5015  931.76
    5024  933.39  5147.4  951.43  5173.8  954.18  5179.4  954.63  5186.3  953.99
#Mann= 3 ,-1,0
  4294.5     .14       0    4985    .049       0    5015     .14       0
#XS Ineff= 2 , 0
Permanent Ineff=
       F       F
Bank Sta=4985,5015
XS Rating Curve= 0 ,0
Exp/Cntr=0.3,0.1

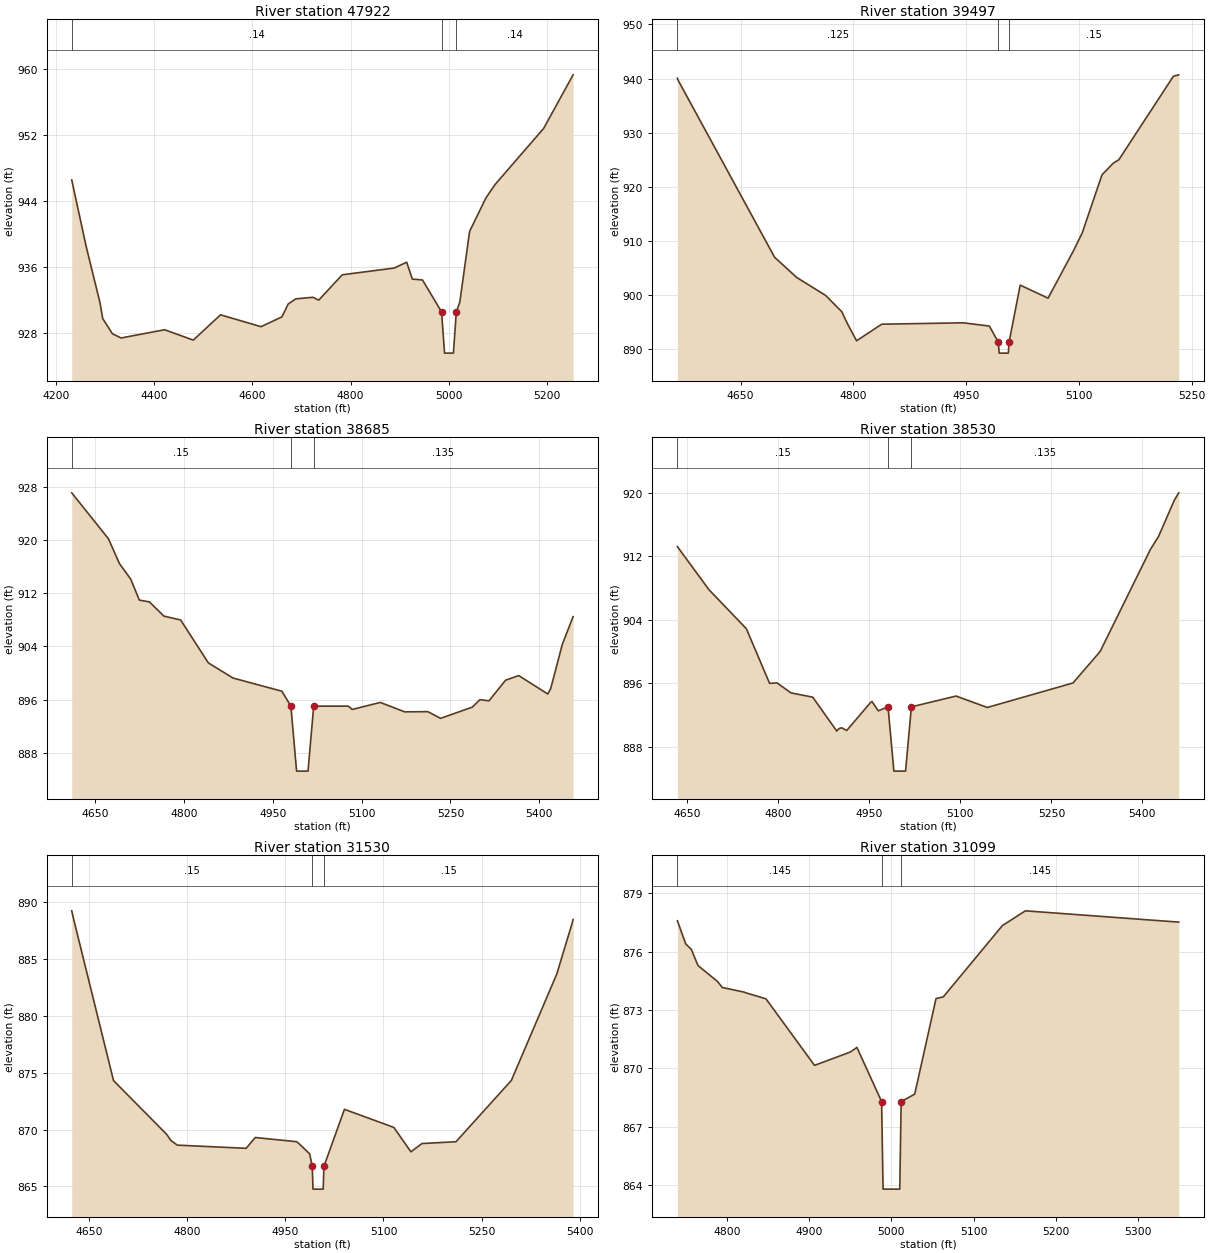
Type RM Length L Ch R = 1 ,47922   ,492,492,492
BEGIN DESCRIPTION:
Georges Creek 95.5
END DESCRIPTION:
XS GIS Cut Line= 3
      1523754.31      1099633.69      1523396.62      1099111.22
      1523034.91      1098974.58
#Sta/Elev= 30
  4232.6  946.54  4261.9  938.48  4290.2   931.6  4295.7   929.7  4315.4  927.86
    4333  927.35  4421.6  928.35  4479.9  927.09  4535.3  930.16  4617.6  928.72
  4660.2  929.91    4673  931.48  4688.6   932.1  4723.6  932.29    4735  931.94
  4782.9  935.02  4888.5  935.84    4914  936.55  4925.5   934.5  4946.2  934.39
    4985  930.51    4991  925.51    5009  925.51    5015  930.51  5022.1  931.71
    5042  940.29  5075.4  944.38  5094.2  946.01  5192.7   952.8  5252.5   959.3
#Mann= 3 ,-1,0
  4232.6     .14       0    4985    .049       0    5015     .14       0
#XS Ineff= 2 , 0
Permanent Ineff=
       F       F
Bank Sta=4985,5015
XS Rating Curve= 0 ,0
Exp/Cntr=0.3,0.1

Type RM Length L Ch R = 1 ,39497   ,812,812,812
BEGIN DESCRIPTION:
Georges Creek 79.0
END DESCRIPTION:
XS GIS Cut Line= 3
      1529868.38      1102335.11      1529979.96      1101915.66
      1530099.57      1101715.94
#Sta/Elev= 24
    4566  940.05  4567.3   939.6  4695.3  906.99  4724.6  903.27    4763  899.96
  4784.6  896.94  4792.5  894.64  4804.3  891.57  4837.7  894.63  4946.1  894.89
  4980.9  894.29  4992.9  891.29  4993.9  889.29  5006.1  889.29  5007.1  891.29
  5021.9  901.85    5059  899.44    5093  908.26  5104.4  911.49  5130.7  922.22
    5146  924.41  5153.1     925  5225.6  940.42  5232.8  940.69
#Mann= 3 ,-1,0
    4566    .125       0  4992.9    .048       0  5007.1     .15       0
Bank Sta=4992.9,5007.1
XS Rating Curve= 0 ,0
Exp/Cntr=0.3,0.1

Type RM Length L Ch R = 1 ,38685   ,155,155,155
BEGIN DESCRIPTION:
Georges Creek 78.0
END DESCRIPTION:
XS GIS Cut Line= 4
       1530702.8      1102712.46      1530639.02      1102374.97
      1530623.08      1102157.06       1530665.6      1101859.43
#Sta/Elev= 30
  4610.9  927.17  4672.8  920.25  4691.5  916.49  4710.5  914.15    4725  910.99
    4742  910.72  4766.6  908.57  4794.7     908  4841.5  901.52  4883.1  899.24
  4965.6  897.25  4980.8     895  4990.4   885.2  5009.7   885.2  5019.3     895
  5077.7     895  5084.3   894.5  5131.6  895.56  5172.8  894.14  5211.9  894.17
  5233.4  893.16    5287  894.85  5299.8  895.98  5315.1   895.8  5343.1  898.91
  5365.3  899.61  5414.4  896.83  5419.3  897.64  5438.9  904.31  5457.1   908.5
#Mann= 3 ,-1,0
  4610.9     .15       0  4980.8    .048       0  5019.3    .135       0
#XS Ineff= 2 , 0
Permanent Ineff=
       F       F
Bank Sta=4980.8,5019.3
XS Rating Curve= 0 ,0
Exp/Cntr=0.3,0.1

Type RM Length L Ch R = 1 ,38530   ,533,533,533
BEGIN DESCRIPTION:
Georges Creek 77.0
END DESCRIPTION:
XS GIS Cut Line= 3
      1530851.61      1102720.43      1530769.23      1102268.67
      1530833.01      1101907.27
#Sta/Elev= 27
  4633.7  913.24  4685.6  907.82  4747.3   902.9  4785.6  896.01  4797.8  896.07
  4820.9  894.81  4856.7  894.27  4896.3     890  4898.1  890.19  4901.5  890.36
  4904.8   890.4  4912.7  890.07  4951.7  893.57  4954.3  893.72  4964.7  892.55
  4980.8  893.05  4990.4  884.95  5009.7  884.95  5019.3  893.05  5092.9  894.41
  5144.4  892.97  5285.6  896.06  5330.3  900.02    5413  912.86  5426.7  914.54
  5452.4  919.06  5459.9  920.02
#Mann= 3 ,-1,0
  4633.7     .15       0  4980.8    .048       0  5019.3    .135       0
#XS Ineff= 2 , 0
Permanent Ineff=
       F       F
Bank Sta=4980.8,5019.3
XS Rating Curve= 0 ,0
Exp/Cntr=0.3,0.1

Type RM Length L Ch R = 1 ,31530   ,431,431,431
BEGIN DESCRIPTION:
Georges Creek 63.0
END DESCRIPTION:
XS GIS Cut Line= 3
      1537080.96      1104748.43      1537189.87      1104349.07
      1537386.96      1103980.83
#Sta/Elev= 24
  4623.2  889.24  4625.6  888.63  4687.1  874.31  4768.7  869.56  4774.6  869.05
  4784.7  868.63  4889.9  868.35  4903.9   869.3  4967.4  868.93  4972.3  868.68
  4987.1  867.86  4991.1  866.76  4992.2  864.76  5007.8  864.76  5008.9  866.76
  5040.3  871.78  5115.8  870.19    5142  868.04  5158.9  868.77  5210.9  868.93
  5295.6  874.32    5365  883.67  5388.8   888.2    5390  888.47
#Mann= 3 ,-1,0
  4623.2     .15       0  4991.1     .05       0  5008.9     .15       0
Bank Sta=4991.1,5008.9
XS Rating Curve= 0 ,0
Exp/Cntr=0.3,0.1

Type RM Length L Ch R = 1 ,31099   ,108,108,108
BEGIN DESCRIPTION:
Georges Creek 62.5
END DESCRIPTION:
XS GIS Cut Line= 4
      1537511.44      1104787.33      1537558.12      1104582.46
      1537617.76      1104432.05      1537685.18      1104203.85
#Sta/Elev= 22
  4739.7  877.59  4749.8   876.4  4756.6  876.12  4764.7  875.29  4788.5  874.47
  4794.3  874.16  4821.3  873.92  4821.9   873.9  4847.4  873.58  4906.5  870.16
  4949.8  870.84  4958.1  871.08  4988.1   868.3  4989.9   863.8  5010.2   863.8
  5011.9   868.3  5028.4  868.68  5054.3  873.59  5063.2  873.68    5135  877.34
    5163   878.1  5349.6  877.52
#Mann= 3 ,-1,0
  4739.7    .145       0  4988.1    .043       0  5011.9    .145       0
#XS Ineff= 2 , 0
Permanent Ineff=
       F       F
Bank Sta=4988.1,5011.9
XS Rating Curve= 0 ,0
Exp/Cntr=0.3,0.1

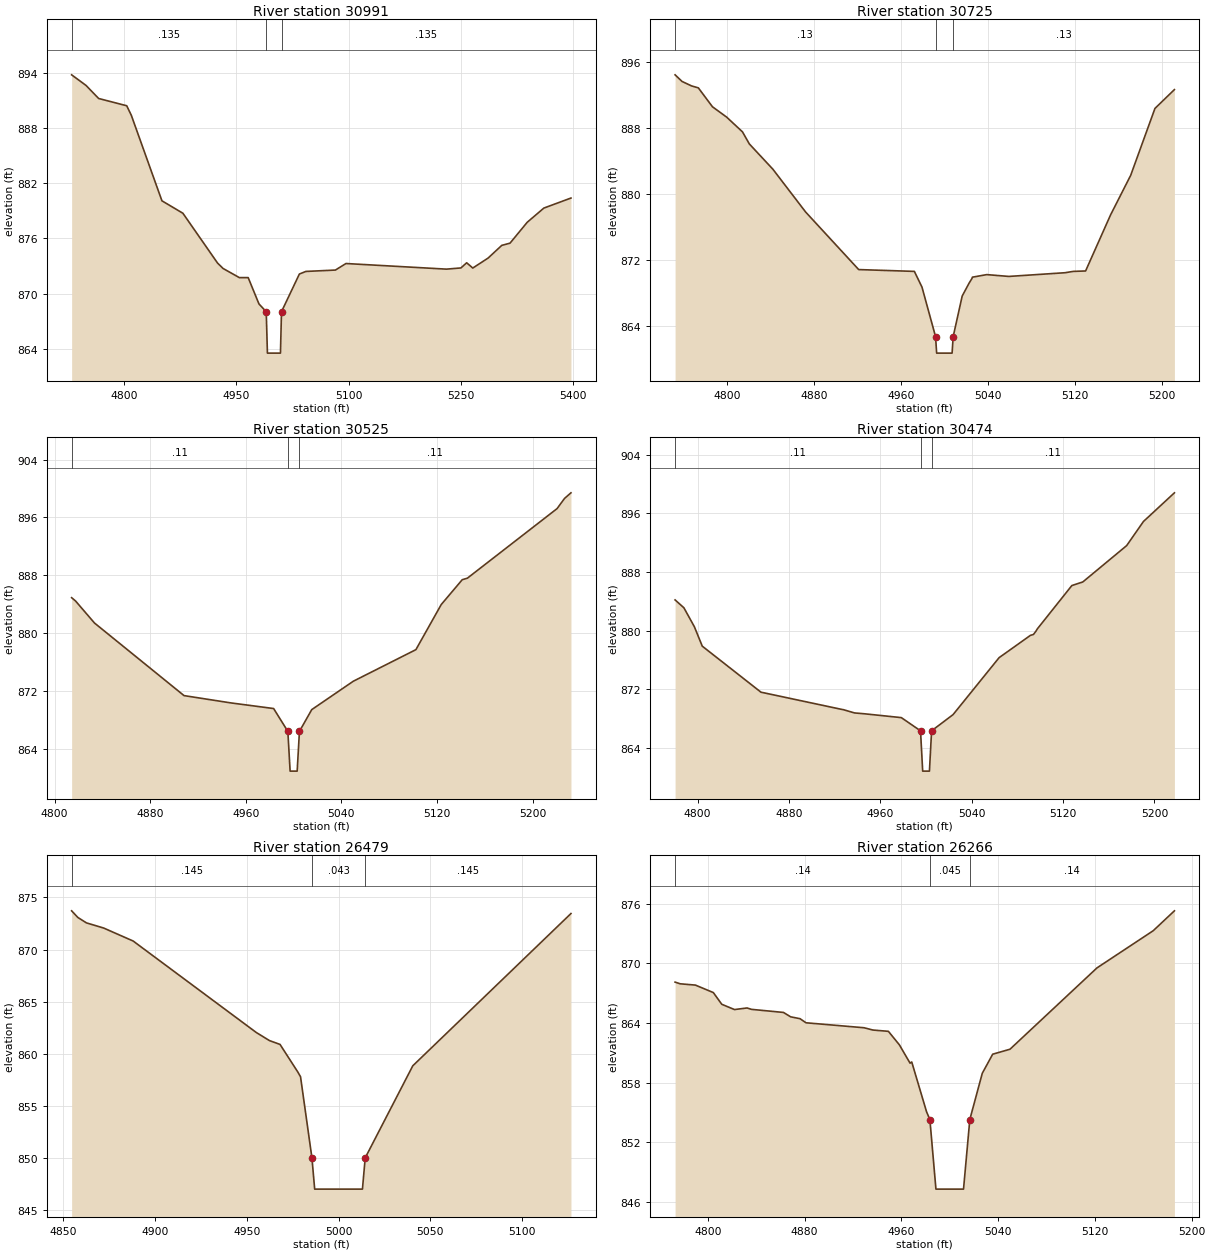
Type RM Length L Ch R = 1 ,30991   ,266,266,266
BEGIN DESCRIPTION:
Georges Creek 62.0
END DESCRIPTION:
XS GIS Cut Line= 5
      1537635.91      1104808.08      1537685.18      1104538.38
      1537695.56      1104457.99      1537752.61      1104325.73
      1537858.93      1104196.07
#Sta/Elev= 30
  4729.9  893.77  4749.1  892.62    4766   891.2  4803.5  890.41  4809.6  889.38
  4850.5  880.09  4878.5  878.74  4924.8  873.33  4932.2  872.74  4953.9  871.75
  4965.7  871.75  4980.1  868.89  4989.8  868.05  4991.4  863.55  5008.8  863.55
  5010.2  868.05  5034.1  872.14  5042.7  872.42  5082.2  872.57  5096.3  873.28
  5230.4  872.67  5249.8   872.8  5257.5  873.36  5265.7  872.79  5286.1  873.87
  5304.4  875.25  5315.4  875.49  5338.4  877.76  5360.6   879.3  5396.8  880.39
#Mann= 3 ,-1,0
  4729.9    .135       0  4989.8    .043       0  5010.2    .135       0
#XS Ineff= 2 , 0
Permanent Ineff=
       F       F
Bank Sta=4989.8,5010.2
XS Rating Curve= 0 ,0
Exp/Cntr=0.3,0.1

Type RM Length L Ch R = 1 ,30725   ,200,200,200
BEGIN DESCRIPTION:
Georges Creek 61.5
END DESCRIPTION:
XS GIS Cut Line= 4
      1537717.64      1104827.58      1537843.69      1104698.07
      1537997.38      1104618.64      1538102.71      1104611.73
#Sta/Elev= 30
  4752.3  894.47  4758.7  893.67  4767.4  893.13  4773.7  892.89  4786.7   890.6
  4799.8  889.34  4814.3  887.56  4820.6   886.1  4842.3  883.03  4872.4  877.85
  4921.2  870.88  4972.4  870.66  4979.4  868.76  4991.9  862.76  4992.9  860.76
  5007.1  860.76  5008.1  862.76  5016.4  867.68  5022.8  869.25  5025.3  869.78
  5025.8  869.96    5039  870.27  5059.3  870.05  5111.1   870.5  5118.5  870.66
  5129.9  870.71  5152.9  877.51  5171.4   882.3  5193.7   890.4  5211.6  892.68
#Mann= 3 ,-1,0
  4752.3     .13       0  4991.9    .042       0  5008.1     .13       0
Bank Sta=4991.9,5008.1
XS Rating Curve= 0 ,0
Exp/Cntr=0.3,0.1

Type RM Length L Ch R = 1 ,30525   ,51,51,51
BEGIN DESCRIPTION:
Georges Creek 61.0
END DESCRIPTION:
XS GIS Cut Line= 3
      1537836.79      1104908.74      1537964.57      1104870.75
      1538179.25      1104683.78
#Sta/Elev= 19
  4814.2   884.9  4817.5  884.44  4833.3   881.4  4908.3  871.35  4947.5  870.34
  4983.3  869.56  4995.2   866.4  4997.1   860.9    5003   860.9  5004.9   866.4
  5015.2  869.41    5050  873.34  5102.4  877.71  5123.6  883.95  5141.2  887.39
  5145.5   887.6  5220.6  897.23  5226.8  898.63  5232.2  899.41
#Mann= 3 ,-1,0
  4814.2     .11       0  4995.2    .041       0  5004.9     .11       0
#XS Ineff= 2 , 0
Permanent Ineff=
       F       F
Bank Sta=4995.2,5004.9
XS Rating Curve= 0 ,0
Exp/Cntr=0.3,0.1

Type RM Length L Ch R = 1 ,30474   ,474,474,474
BEGIN DESCRIPTION:
Georges Creek 60.5
END DESCRIPTION:
XS GIS Cut Line= 3
      1537848.87      1104955.36      1538006.01      1104901.83
       1538204.6      1104717.06
#Sta/Elev= 25
  4780.3  884.21    4788  883.14  4797.2  880.55  4804.1   877.9  4855.5  871.62
  4926.9  869.25  4927.3  869.25  4937.4  868.79  4946.3  868.67  4978.4  868.15
  4995.2  866.35  4997.1  860.85    5003  860.85  5004.9  866.35  5023.7  868.56
    5064  876.33  5091.4  879.37  5094.1   879.5  5096.3  879.95  5097.5  880.26
  5127.7  886.17  5137.3  886.66  5175.7  891.62  5190.4  894.91  5217.5  898.82
#Mann= 3 ,-1,0
  4780.3     .11       0  4995.2    .042       0  5004.9     .11       0
#XS Ineff= 2 , 0
Permanent Ineff=
       F       F
Bank Sta=4995.2,5004.9
XS Rating Curve= 0 ,0
Exp/Cntr=0.3,0.1

Type RM Length L Ch R = 1 ,26479   ,213,213,213
BEGIN DESCRIPTION:
Georges Creek 53.0
END DESCRIPTION:
XS GIS Cut Line= 3
      1540844.48      1107037.89      1540756.12       1106916.4
      1540620.83      1106858.42
#Sta/Elev= 17
  4854.7  873.72  4858.1  873.08  4862.8  872.56  4872.1  872.07  4888.2  870.82
  4955.2  862.04  4962.4  861.26  4968.2  860.89  4968.3  860.85  4977.8  858.25
  4979.3  857.79  4985.5     850    4987     847    5013     847  5014.5     850
  5040.4  858.84  5126.5  873.46
#Mann= 3 ,-1,0
  4854.7    .145       0  4985.5    .043       0  5014.5    .145       0
Bank Sta=4985.5,5014.5
XS Rating Curve= 0 ,0
Exp/Cntr=0.3,0.1

Type RM Length L Ch R = 1 ,26266   ,75,75,75
BEGIN DESCRIPTION:
Georges Creek 52.5
END DESCRIPTION:
XS GIS Cut Line= 4
       1541012.9      1106874.98      1540838.95      1106725.88
      1540761.64      1106665.14      1540696.16      1106610.43
#Sta/Elev= 29
    4773  868.12  4777.3  867.95  4789.8  867.82  4804.6  867.07  4811.6  865.89
  4822.1  865.36  4832.5  865.52  4836.2  865.38  4862.6  865.07  4868.5  864.63
  4876.3  864.44  4881.2  864.03  4929.2  863.53  4936.5   863.3  4949.3  863.17
  4958.4  861.81  4967.2  859.97  4968.6  860.09  4980.9  855.06  4983.6   854.3
  4988.6   847.3  5011.4   847.3  5016.6   854.3  5026.9  858.95  5035.5  860.87
  5049.8  861.37  5121.7  869.55  5168.2  873.29  5185.7  875.29
#Mann= 3 ,-1,0
    4773     .14       0  4983.6    .045       0  5016.6     .14       0
#XS Ineff= 2 , 0
Permanent Ineff=
       F       F
Bank Sta=4983.6,5016.6
XS Rating Curve= 0 ,0
Exp/Cntr=0.3,0.1

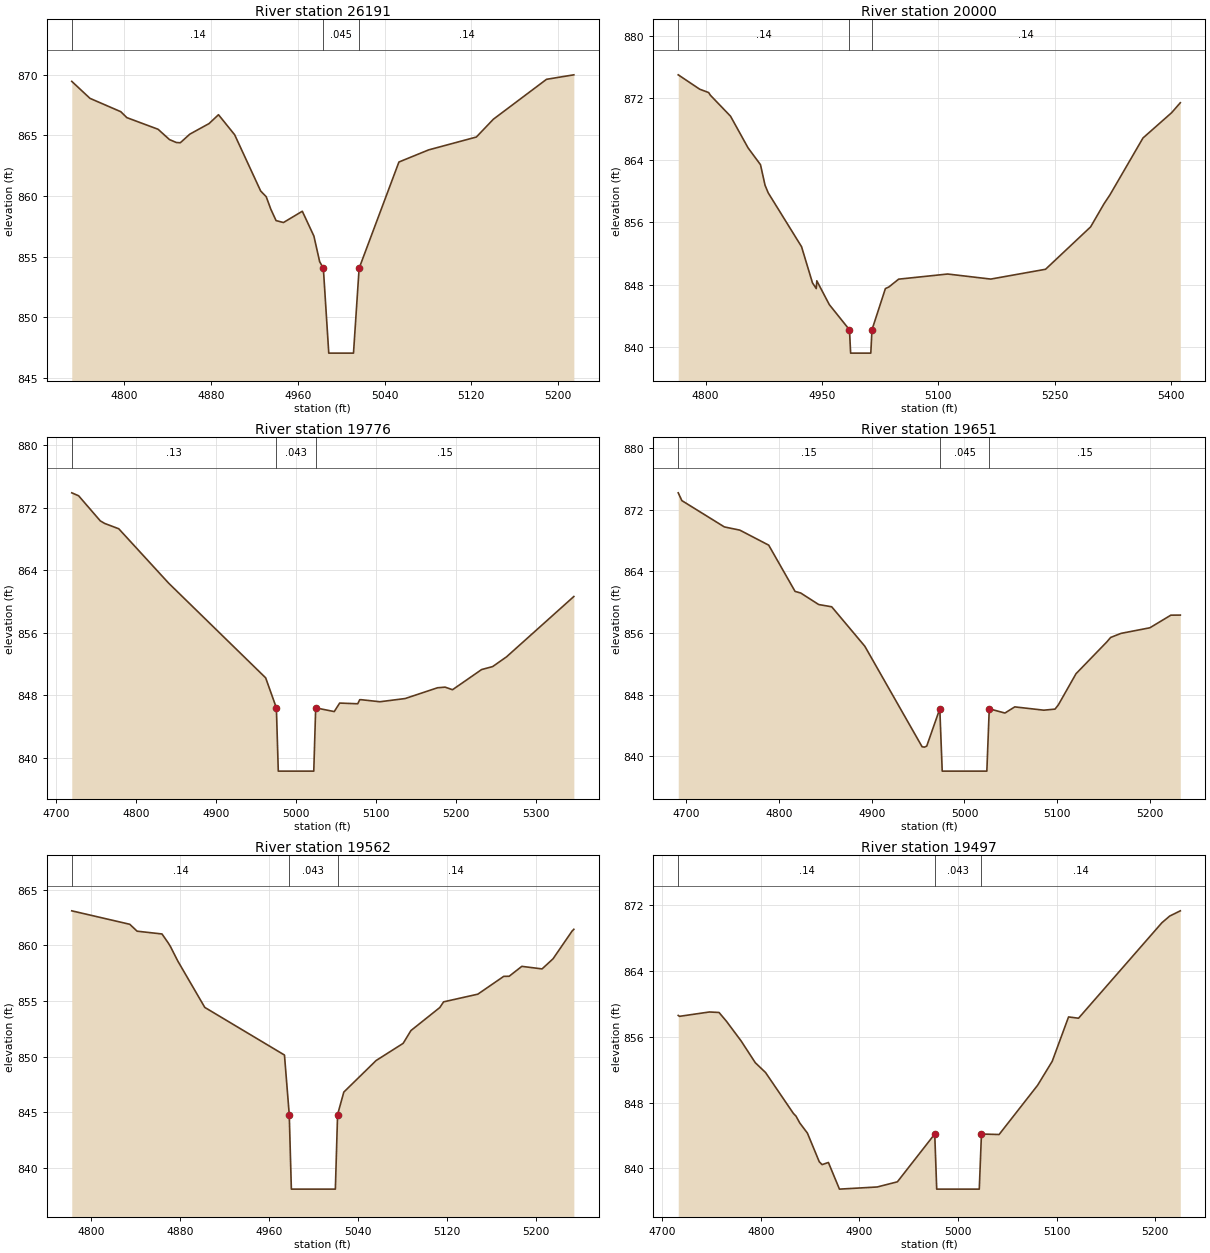
Type RM Length L Ch R = 1 ,26191   ,689,689,689
BEGIN DESCRIPTION:
Georges Creek 52.0
END DESCRIPTION:
XS GIS Cut Line= 4
      1541090.77      1106838.05      1540946.04      1106715.58
       1540834.7      1106631.46      1540741.93      1106534.98
#Sta/Elev= 30
  4751.6  869.46  4768.4  868.06  4796.8  866.96  4802.4  866.47  4831.2  865.51
  4841.7  864.66    4848  864.42  4851.7   864.4  4860.5  865.11  4878.2  865.98
  4886.9  866.71  4901.8  865.06  4925.8  860.42  4930.9  859.95  4935.2  858.91
    4940  857.98  4946.8  857.82  4964.2  858.75  4974.9   856.7  4980.2  854.59
  4983.6  854.05  4988.6  847.05  5011.4  847.05  5016.6  854.05  5053.3  862.81
  5080.7  863.81  5124.7  864.87  5140.4  866.34  5189.4  869.63  5214.6     870
#Mann= 3 ,-1,0
  4751.6     .14       0  4983.6    .045       0  5016.6     .14       0
#XS Ineff= 2 , 0
Permanent Ineff=
       F       F
Bank Sta=4983.6,5016.6
XS Rating Curve= 0 ,0
Exp/Cntr=0.3,0.1

Type RM Length L Ch R = 1 ,20000   ,224,224,224
BEGIN DESCRIPTION:
Georges Creek 40.0
END DESCRIPTION:
XS GIS Cut Line= 3
      1544196.46      1103039.81      1543918.93      1102856.43
      1543550.36      1102672.58
#Sta/Elev= 30
  4764.8  874.97  4792.5  873.12    4804  872.69  4806.3  872.34  4832.2  869.65
  4854.8  865.58  4870.8  863.42  4876.7  860.77  4880.8  859.79  4923.7  852.88
  4937.8  848.23  4942.7  847.49  4943.4  848.49  4959.5  845.43  4985.5  842.19
    4987  839.19    5013  839.19  5014.5  842.19  5031.8  847.49  5036.2  847.69
  5048.9   848.7  5112.1  849.36  5167.6  848.71  5238.2  849.97  5296.3  855.42
  5313.5  858.38  5321.1  859.52  5363.8  866.85  5400.7   870.1  5411.9  871.38
#Mann= 3 ,-1,0
  4764.8     .14       0  4985.5    .045       0  5014.5     .14       0
Bank Sta=4985.5,5014.5
XS Rating Curve= 0 ,0
Exp/Cntr=0.3,0.1

Type RM Length L Ch R = 1 ,19776   ,125,125,125
BEGIN DESCRIPTION:
Georges Creek 39.9
END DESCRIPTION:
XS GIS Cut Line= 4
       1544180.9      1102851.99      1544029.03      1102662.86
      1543920.04      1102613.45      1543658.46      1102565.49
#Sta/Elev= 25
  4719.4  873.92    4728  873.54  4755.1  870.33  4760.6     870  4778.2  869.32
  4840.7  862.35    4962  850.24  4975.4   846.4  4977.8   838.3  5022.2   838.3
  5024.6   846.4  5047.8  845.92  5054.6  847.01  5077.2  846.92  5079.7  847.44
  5081.6  847.44    5105  847.18  5136.5  847.59  5177.1  848.97  5186.5  849.05
  5195.8  848.72  5232.2   851.3    5246  851.68  5263.4  852.93  5347.6  860.65
#Mann= 3 ,-1,0
  4719.4     .13       0  4975.4    .043       0  5024.6     .15       0
#XS Ineff= 2 , 0
Permanent Ineff=
       F       F
Bank Sta=4975.4,5024.6
XS Rating Curve= 0 ,0
Exp/Cntr=0.3,0.1

Type RM Length L Ch R = 1 ,19651   ,89,89,89
BEGIN DESCRIPTION:
Georges Creek 39.6
END DESCRIPTION:
XS GIS Cut Line= 5
      1544216.64      1102750.74       1544127.3      1102643.53
      1544029.02      1102536.32      1543939.68      1102473.78
       1543802.7      1102420.18
#Sta/Elev= 29
  4691.5  874.22  4695.4  873.21  4741.2  869.79  4757.9  869.37    4789  867.42
  4817.4  861.41  4823.5   861.2  4842.9   859.7  4856.9  859.41  4892.6  854.28
  4954.3  841.22  4956.8  841.17  4959.3   841.3  4973.4  846.15    4976  838.05
  5024.1  838.05  5026.7  846.15  5043.6   845.6  5054.2   846.4  5085.5  845.97
  5097.6  846.11  5101.2  846.67  5120.2  850.71  5153.7  854.88  5157.5  855.42
  5168.6  855.95  5199.8  856.68  5222.4  858.32  5232.6  858.33
#Mann= 3 ,-1,0
  4691.5     .15       0  4973.4    .045       0  5026.7     .15       0
#XS Ineff= 2 , 0
Permanent Ineff=
       F       F
Bank Sta=4973.4,5026.7
XS Rating Curve= 0 ,0
Exp/Cntr=0.3,0.1

Type RM Length L Ch R = 1 ,19562   ,65,65,65
BEGIN DESCRIPTION:
Georges Creek 39.3
END DESCRIPTION:
XS GIS Cut Line= 6
      1544201.75      1102381.47      1544106.45      1102384.44
      1544023.07      1102420.18      1543972.44      1102449.96
      1543886.08      1102446.98      1543784.83      1102381.47
#Sta/Elev= 27
  4782.6  863.11  4834.8   861.9  4841.4  861.28  4863.8  861.03  4869.5  860.21
  4871.4   859.9    4878   858.6  4902.3  854.43    4974  850.15  4978.3   844.8
  4980.2   838.1  5019.8   838.1  5021.8   844.8  5027.4  846.82  5056.5  849.66
  5080.8   851.2  5087.8  852.35  5113.8  854.42  5117.2  854.93    5148  855.62
  5171.3  857.22  5176.2  857.23  5187.6  858.12  5205.8  857.89  5215.7   858.8
  5232.8  861.29  5234.4  861.45
#Mann= 3 ,-1,0
  4782.6     .14       0  4978.3    .043       0  5021.8     .14       0
#XS Ineff= 2 , 0
Permanent Ineff=
       F       F
Bank Sta=4978.3,5021.8
XS Rating Curve= 0 ,0
Exp/Cntr=0.3,0.1

Type RM Length L Ch R = 1 ,19497   ,496,496,496
BEGIN DESCRIPTION:
Georges Creek 39.0
END DESCRIPTION:
XS GIS Cut Line= 6
      1544213.59      1102354.77      1544155.46      1102302.46
      1544092.97      1102285.02       1543992.7      1102372.21
      1543868.21      1102372.53      1543778.87      1102309.99
#Sta/Elev= 30
  4716.1   858.6  4717.4  858.49  4747.7  859.02  4757.5  858.96  4765.1  857.88
  4779.9   855.5  4794.3  852.85  4804.7  851.66    4833  846.68  4835.6  846.36
  4839.4  845.53  4847.2  844.29  4859.2  840.81  4862.1  840.46  4868.5  840.72
  4879.7  837.48    4918  837.74  4938.5  838.37  4976.4  844.18  4978.4  837.48
  5021.6  837.48  5023.8  844.18  5041.7  844.12  5080.8  850.11  5095.6  853.02
  5112.2  858.42  5122.3  858.26  5206.9  869.87  5214.8  870.68  5225.6  871.32
#Mann= 3 ,-1,0
  4716.1     .14       0  4976.4    .043       0  5023.8     .14       0
#XS Ineff= 2 , 0
Permanent Ineff=
       F       F
Bank Sta=4976.4,5023.8
XS Rating Curve= 0 ,0
Exp/Cntr=0.3,0.1

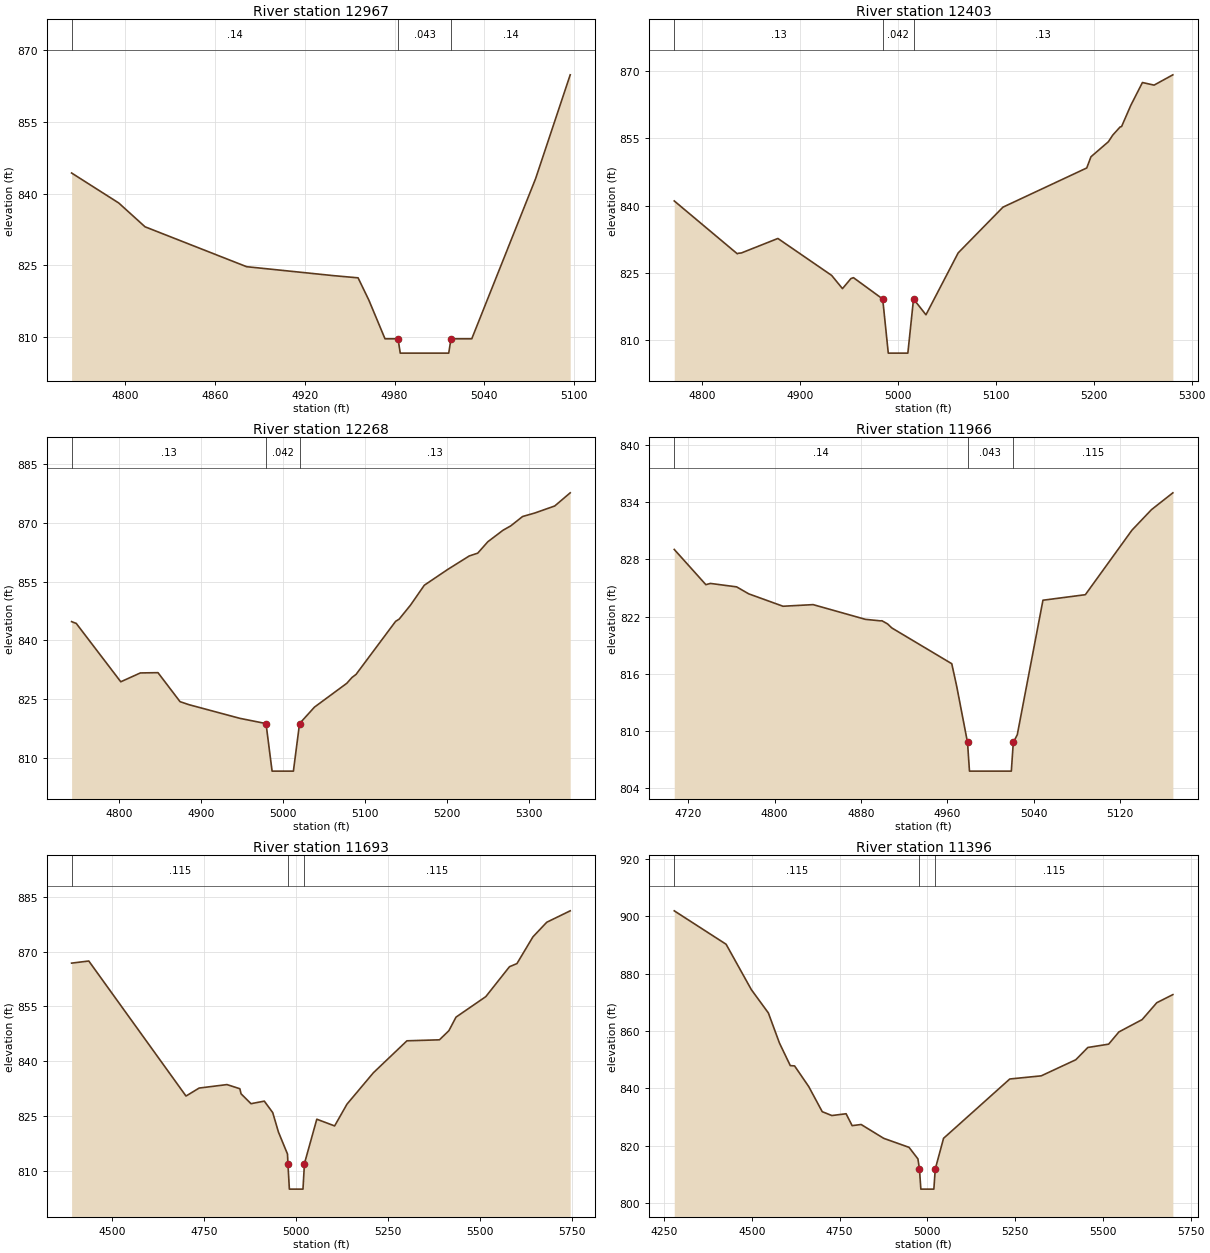
Type RM Length L Ch R = 1 ,12967   ,564,564,564
BEGIN DESCRIPTION:
Georges Creek 26.0
END DESCRIPTION:
XS GIS Cut Line= 4
      1548191.32      1099382.51       1548189.3      1099207.23
      1548213.48      1099150.82      1548251.76      1099062.17
#Sta/Elev= 15
  4764.1  844.32  4795.6  838.05  4813.2  833.06  4881.1  824.71  4939.4  822.83
  4955.6  822.38  4962.8  817.72  4973.6  809.62  4982.3  809.62  4983.8  806.62
  5016.2  806.62  5017.7  809.62  5031.6  809.62  5074.3  843.17  5097.4  864.87
#Mann= 3 ,-1,0
  4764.1     .14       0  4982.3    .043       0  5017.7     .14       0
Bank Sta=4982.3,5017.7
XS Rating Curve= 0 ,0
Exp/Cntr=0.3,0.1

Type RM Length L Ch R = 1 ,12403   ,135,135,135
BEGIN DESCRIPTION:
Georges Creek 25.0
END DESCRIPTION:
XS GIS Cut Line= 4
      1548874.08      1099301.55      1548869.72      1099236.16
      1548729.24      1099166.94      1548452.64      1099089.38
#Sta/Elev= 26
  4771.3  841.02  4835.7  829.21  4836.9  829.33  4839.9  829.39  4877.2  832.63
  4932.1  824.38  4943.2  821.42  4951.8  823.66  4954.4  823.87  4984.3   819.1
    4990     807    5010     807  5015.8   819.1  5028.5  815.57  5061.4   829.4
  5107.2  839.63  5192.8  848.39  5197.1  850.89  5214.9  854.25  5219.4  855.74
  5226.9  857.56  5228.4  857.65  5237.8  862.38  5249.7  867.49  5261.6  866.91
  5280.8  869.21
#Mann= 3 ,-1,0
  4771.3     .13       0  4984.3    .042       0  5015.8     .13       0
#XS Ineff= 2 , 0
Permanent Ineff=
       F       F
Bank Sta=4984.3,5015.8
XS Rating Curve= 0 ,0
Exp/Cntr=0.3,0.1

Type RM Length L Ch R = 1 ,12268   ,302,302,302
BEGIN DESCRIPTION:
Georges Creek 24.5
END DESCRIPTION:
XS GIS Cut Line= 5
      1548920.58      1099301.55      1548952.55      1099162.04
      1548872.62      1099128.62      1548807.23      1099093.74
      1548515.13        1099008.
#Sta/Elev= 30
  4742.4   844.8  4748.1  844.34  4802.4  829.49  4826.3  831.74  4847.8  831.81
  4874.7  824.43  4885.6  823.66  4947.6  820.19  4979.6  818.85    4987  806.75
    5013  806.75  5020.5  818.85  5038.7  823.04  5078.1   829.1  5084.5  830.59
  5089.4  831.36  5137.7  844.87    5142  845.43  5155.9  849.01  5172.7  854.06
  5201.2  858.07  5227.5  861.51  5237.9  862.23  5250.2  865.13  5268.9  868.08
  5278.1  869.16  5292.6  871.55  5307.6  872.45  5331.8  874.23  5350.7  877.58
#Mann= 3 ,-1,0
  4742.4     .13       0  4979.6    .042       0  5020.5     .13       0
#XS Ineff= 2 , 0
Permanent Ineff=
       F       F
Bank Sta=4979.6,5020.5
XS Rating Curve= 0 ,0
Exp/Cntr=0.3,0.1

Type RM Length L Ch R = 1 ,11966   ,273,273,273
BEGIN DESCRIPTION:
Georges Creek 24.0
END DESCRIPTION:
XS GIS Cut Line= 4
      1549021.24      1099207.96      1549148.85      1099063.89
      1549109.74      1098971.28        1549025.        1098825.
#Sta/Elev= 24
    4707  829.03  4736.3  825.34  4740.5  825.47  4764.8  825.11    4776  824.38
  4807.8  823.08  4835.7  823.25  4884.1  821.71    4898  821.55  4899.5  821.56
  4904.7  821.23  4908.6  820.81  4964.2  817.06  4968.8  814.68  4978.8  808.81
  4980.6  805.81  5019.4  805.81  5021.2  808.81  5024.9  809.62  5048.7  823.71
    5088  824.29  5131.2  831.05  5149.3   833.2  5169.1  834.96
#Mann= 3 ,-1,0
    4707     .14       0  4978.8    .043       0  5021.2    .115       0
Bank Sta=4978.8,5021.2
XS Rating Curve= 0 ,0
Exp/Cntr=0.3,0.1

Type RM Length L Ch R = 1 ,11693   ,297,297,297
BEGIN DESCRIPTION:
Georges Creek 23.0
END DESCRIPTION:
XS GIS Cut Line= 4
      1549910.95      1099041.42      1549336.13      1098845.73
      1549245.38      1098808.91      1548620.49       1098625.8
#Sta/Elev= 30
  4389.1  866.84  4435.9  867.42  4700.3  830.53    4736  832.71  4811.7  833.66
  4846.8  832.53  4850.1  831.14  4877.1  828.44  4913.3  829.14  4936.2  826.01
  4951.7  820.71  4976.4  814.68  4977.5   812.1  4981.5   805.1  5018.5   805.1
  5022.5   812.1  5056.1   824.2  5104.6  822.37  5138.1   828.3    5210  836.89
  5301.3  845.62  5389.7  845.89  5415.4  848.39  5434.8  852.09  5515.8  857.69
  5580.2  865.86  5600.5  866.72  5644.1  874.03  5681.6  878.01  5745.4  881.13
#Mann= 3 ,-1,0
  4389.1    .115       0  4977.5     .04       0  5022.5    .115       0
#XS Ineff= 2 , 0
Permanent Ineff=
       F       F
Bank Sta=4977.5,5022.5
XS Rating Curve= 0 ,0
Exp/Cntr=0.3,0.1

Type RM Length L Ch R = 1 ,11396   ,355,355,355
BEGIN DESCRIPTION:
Georges Creek 22.5
END DESCRIPTION:
XS GIS Cut Line= 5
      1550056.27      1098771.12      1549675.53      1098628.71
      1549474.02      1098576.13      1549283.16       1098532.8
      1548681.53      1098439.79
#Sta/Elev= 30
  4279.6  901.91  4427.2  890.25  4499.1  874.41  4547.5  866.29    4579  855.81
  4609.9  847.93  4622.1  847.82  4662.3  840.63  4700.8  831.86  4728.2  830.51
  4768.7  831.14  4785.9  826.99  4811.5  827.39  4875.9  822.56  4947.9  819.42
  4973.2  815.38  4977.5  811.85  4981.5  804.85  5018.5  804.85  5022.5  811.85
  5046.1  822.57  5234.6  843.26  5324.2  844.36  5422.5  849.97  5456.8  854.25
    5516  855.41  5545.3  859.68  5611.4  863.98    5653  869.86  5698.8  872.69
#Mann= 3 ,-1,0
  4279.6    .115       0  4977.5     .04       0  5022.5    .115       0
#XS Ineff= 2 , 0
Permanent Ineff=
       F       F
Bank Sta=4977.5,5022.5
XS Rating Curve= 0 ,0
Exp/Cntr=0.3,0.1

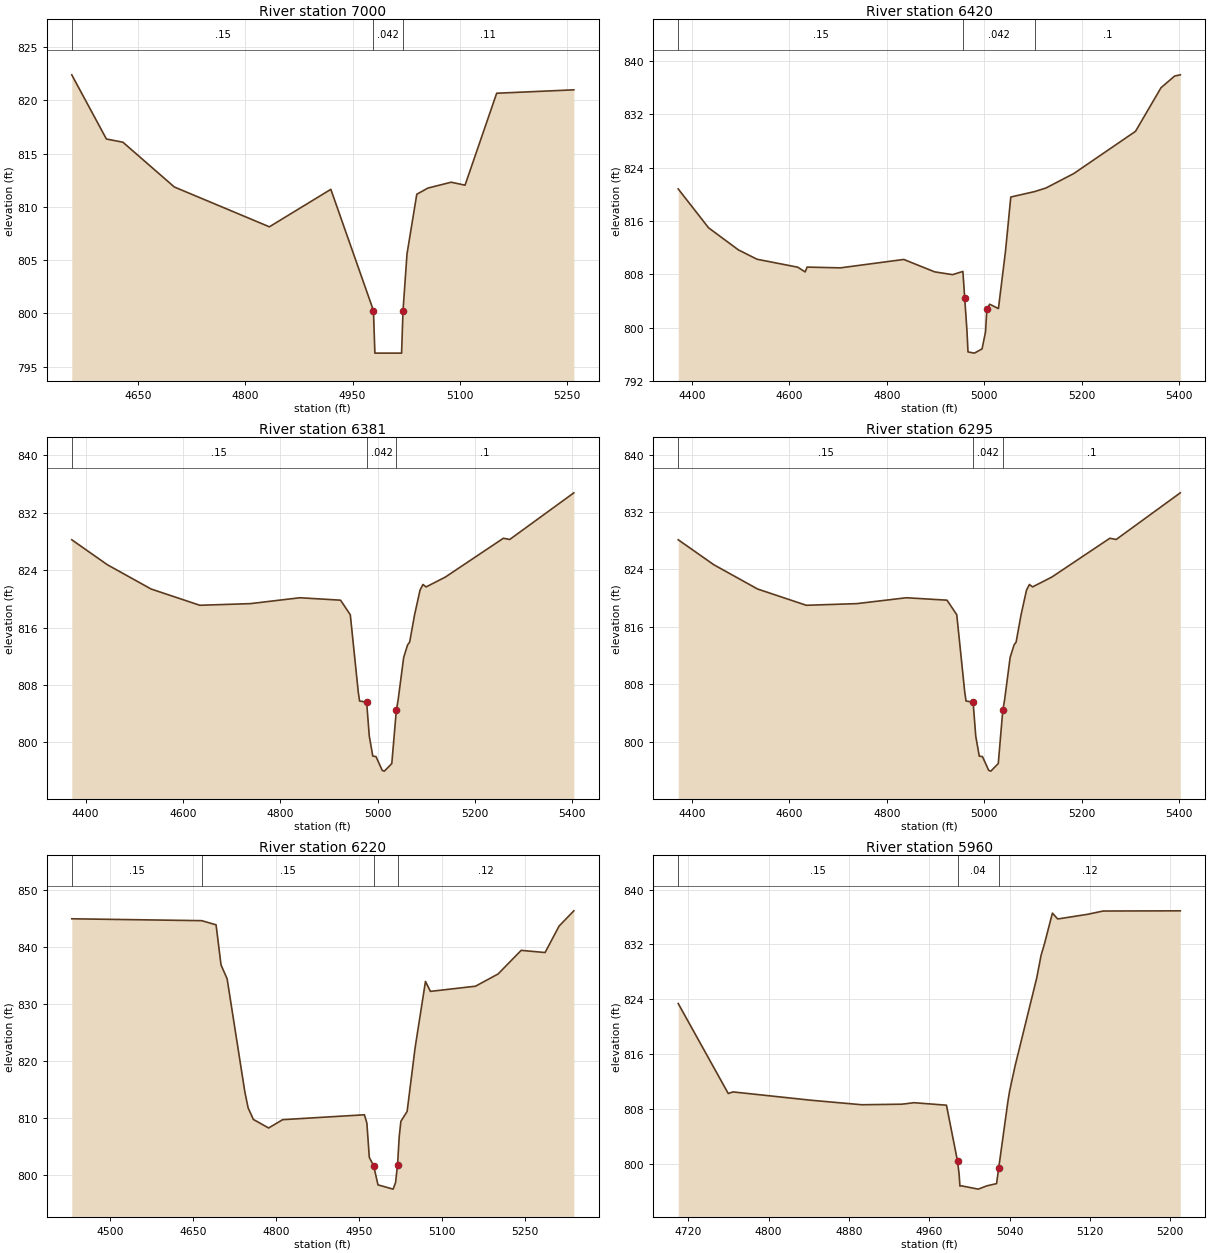
Type RM Length L Ch R = 1 ,7000    ,580,580,580
BEGIN DESCRIPTION:
Georges Creek 14.0
END DESCRIPTION:
XS GIS Cut Line= 3
        1550589.      1095675.48      1550326.46      1095246.59
      1550094.58      1095038.68
#Sta/Elev= 17
  4556.7  822.41  4605.2  816.38  4628.3  816.08  4700.4  811.87  4833.5  808.13
  4919.6  811.65  4979.3  800.26  4981.3  796.26  5018.7  796.26  5020.7  800.26
  5026.3  805.58    5040  811.19  5055.6  811.77  5088.2  812.32  5107.6  812.04
  5151.9  820.68    5260     821
#Mann= 3 ,-1,0
  4556.7     .15       0  4979.3    .042       0  5020.7     .11       0
Bank Sta=4979.3,5020.7
XS Rating Curve= 0 ,0
Exp/Cntr=0.3,0.1

Type RM Length L Ch R = 1 ,6420    ,39,39,39
BEGIN DESCRIPTION:
Georges Creek 13.0
END DESCRIPTION:
XS GIS Cut Line= 2
    1551220.9265    1095051.0574    1550283.4392    1094621.2055
#Sta/Elev= 30
  4371.5  820.81  4433.8  814.98  4495.2  811.66  4533.4  810.26  4616.9  809.07
  4632.3  808.36  4636.2  809.08  4704.6  808.97  4834.8  810.23  4898.1  808.37
  4934.9  807.95  4956.2  808.43    4960 804.386  4964.6  799.49  4966.7  796.35
  4979.9  796.17  4995.6  796.81  5002.7  799.36  5005.4  802.75  5011.2  803.51
  5029.2  802.86  5043.6  811.39  5054.6   819.6  5103.7  820.42  5126.7  820.95
  5183.9  823.12  5310.8  829.46  5363.2  836.01  5391.2  837.76  5402.8  837.94
#Mann= 3 ,-1,0
  4371.5     .15       0  4956.2    .042       0  5103.7      .1       0
Bank Sta=4960,5005.4
XS Rating Curve= 0 ,0
Exp/Cntr=0.3,0.1

Type RM Length L Ch R = 1 ,6381    ,86,86,86
BEGIN DESCRIPTION:
Georges Creek 13.0
END DESCRIPTION:
XS GIS Cut Line= 4
    1551237.1813    1095015.6063    1551237.1813    1095015.6063
1550554.584369411094702.62543343     1550299.694    1094585.7544
#Sta/Elev= 30
 4371.75  828.24 4444.85  824.76 4534.65  821.38 4634.78  819.11  4738.6  819.34
 4840.41  820.16  4923.9  819.82 4943.91  817.79 4960.24  807.04 4962.95  805.77
 4977.47  805.61 4982.89  800.88 4990.11  798.09 4996.65  798.03 5009.56   796.1
 5013.89     796 5029.15  797.06 5038.42  804.45 5042.18  805.94 5053.51  811.83
 5061.54  813.58 5065.82  813.98 5075.89  817.76 5087.13  821.22 5093.13  822.01
  5099.6  821.67 5139.15  823.04 5258.34  828.45 5271.38  828.28 5403.09  834.78
#Mann= 3 ,-1,0
 4371.75     .15       0 4977.47    .042       0 5038.42      .1       0
Bank Sta=4977.47,5038.42
XS Rating Curve= 0 ,0
Exp/Cntr=0.3,0.1

Type RM Length L Ch R = 1 ,6295    ,75,75,75
BEGIN DESCRIPTION:
Georges Creek 13.0
END DESCRIPTION:
XS GIS Cut Line= 2
    1551273.0254    1094937.4321     1550335.538    1094507.5802
#Sta/Elev= 30
  4371.5  828.13  4444.6  824.65  4534.4  821.27 4634.53     819 4738.35  819.23
 4840.16  820.05 4923.65  819.71 4943.66  817.68 4959.99  806.93  4962.7  805.66
 4977.22   805.5 4982.64  800.77 4989.86  797.98  4996.4  797.92 5009.31  795.99
 5013.64  795.89  5028.9  796.95 5038.17  804.34 5041.93  805.83 5053.26  811.72
 5061.29  813.47 5065.57  813.87 5075.64  817.65 5086.88  821.11 5092.88   821.9
 5099.35  821.56  5138.9  822.93 5258.09  828.34 5271.13  828.17 5402.84  834.67
#Mann= 3 ,-1,0
  4371.5     .15       0 4977.22    .042       0 5038.17      .1       0
#XS Ineff= 2 , 0
Permanent Ineff=
       F       F
Bank Sta=4977.22,5038.17
XS Rating Curve= 0 ,0
Exp/Cntr=0.3,0.1

Type RM Length L Ch R = 1 ,6220    ,260,260,260
XS GIS Cut Line= 2
    1551320.6064    1094872.9437    1550360.5379    1094437.7468
#Sta/Elev= 30
    4430     845    4665  844.67 4690.89  843.94 4699.84  836.89 4710.87  834.46
 4742.87   814.6 4748.83  811.77 4758.32  809.73  4785.9  808.23 4811.28  809.69
 4959.12  810.55 4963.54  809.08 4967.95  803.04 4975.67  801.63 4983.62  798.23
 5010.98  797.48  5015.4  798.64 5018.98  801.76 5022.02  806.74    5025   809.4
 5036.29  811.13  5050.7  822.32 5069.46  833.99 5078.43  832.24 5159.93  833.15
 5200.76   835.3 5242.48  839.45 5285.72  839.07 5311.09  843.73  5337.7   846.4
#Mann= 4 ,-1,0
    4430     .15       0    4665     .15       0 4975.67    .045       0
 5018.98     .12       0
#XS Ineff= 2 , 0
Permanent Ineff=
       F       F
Bank Sta=4975.67,5018.98
XS Rating Curve= 0 ,0
Exp/Cntr(USF)=0,0
Exp/Cntr=0.3,0.1

Type RM Length L Ch R = 1 ,5960    ,58,58,58
BEGIN DESCRIPTION:
Georges Creek 12.0
END DESCRIPTION:
XS GIS Cut Line= 4
      1551040.87      1094403.23      1550762.74      1094346.52
      1550552.11      1094357.321550540.936689951094357.89290865
#Sta/Elev= 27
  4710.1  823.37  4759.9  810.24  4764.7  810.474842.529 809.2544892.841 808.599
4932.809 808.6794944.874 808.8964977.175 808.5334988.165 800.3794989.785 798.446
4990.566  796.734992.082 796.7645008.815 796.2845017.452 796.7655027.048 797.088
 5029.24 799.4165038.279 809.0145040.111 810.6495045.509 814.2795067.002  827.08
5071.343 830.384 5074.81 832.1195082.657 836.561 5087.96 835.7115117.904 836.397
5133.088  836.87    5210   836.9
#Mann= 3 ,-1,0
  4710.1     .15       04988.165     .04       0 5029.24     .12       0
Bank Sta=4988.165,5029.24
XS Rating Curve= 0 ,0
Exp/Cntr=0.3,0.1