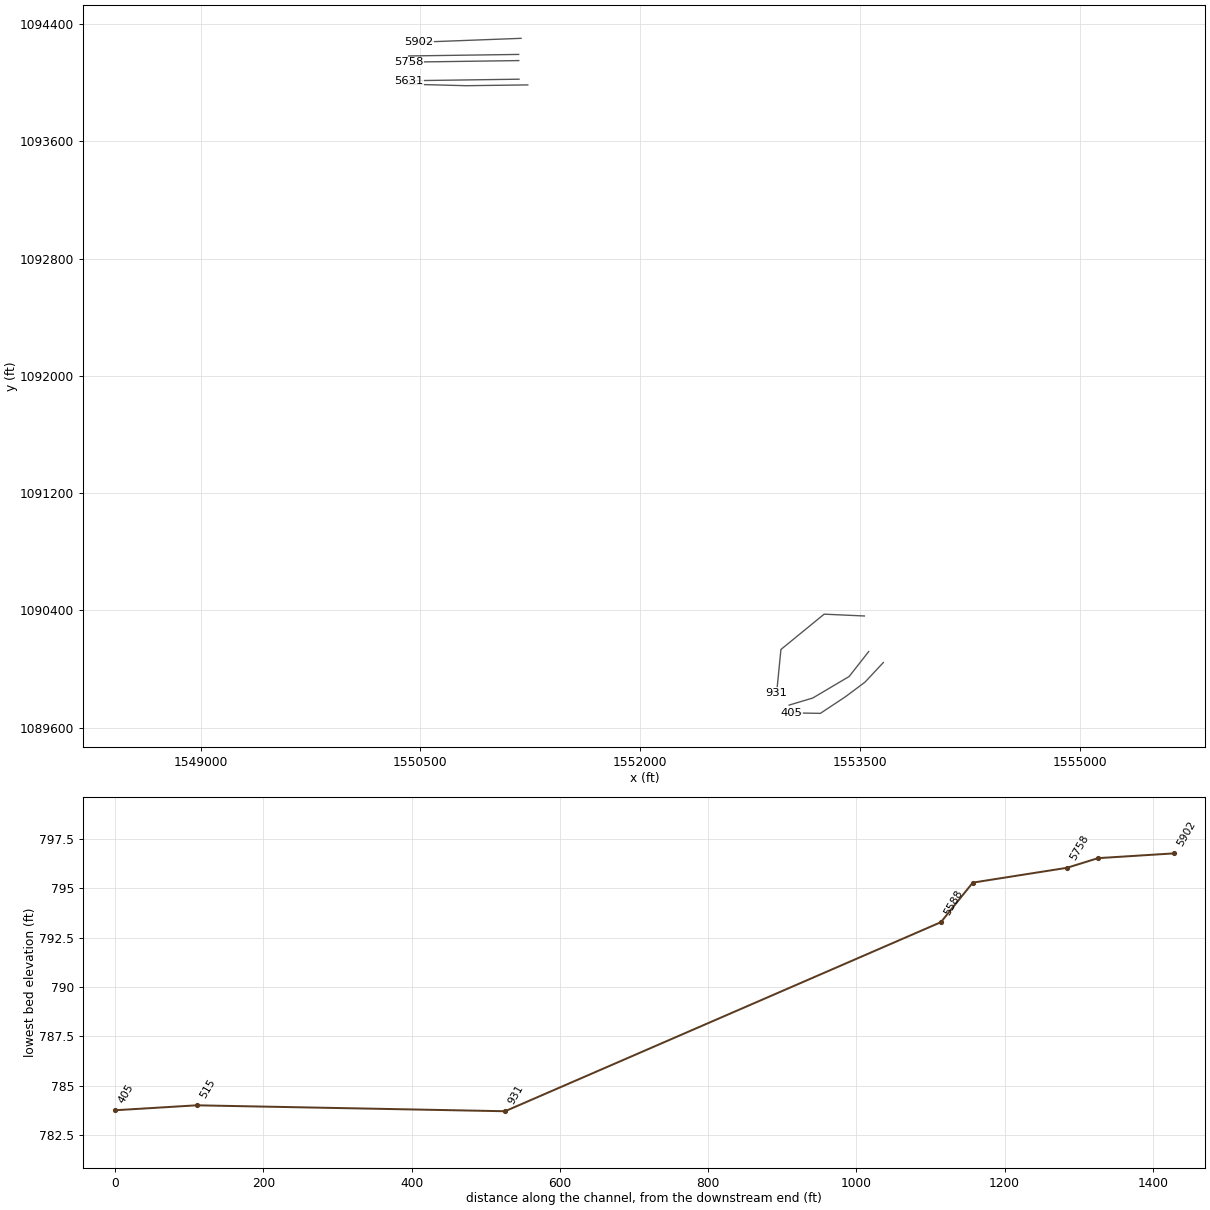
HEC-RAS study GeorgesCreek.prj: Georges Creek Limited Detail Study

--- GeorgesCreek.g09 (geometry) --- (continued)

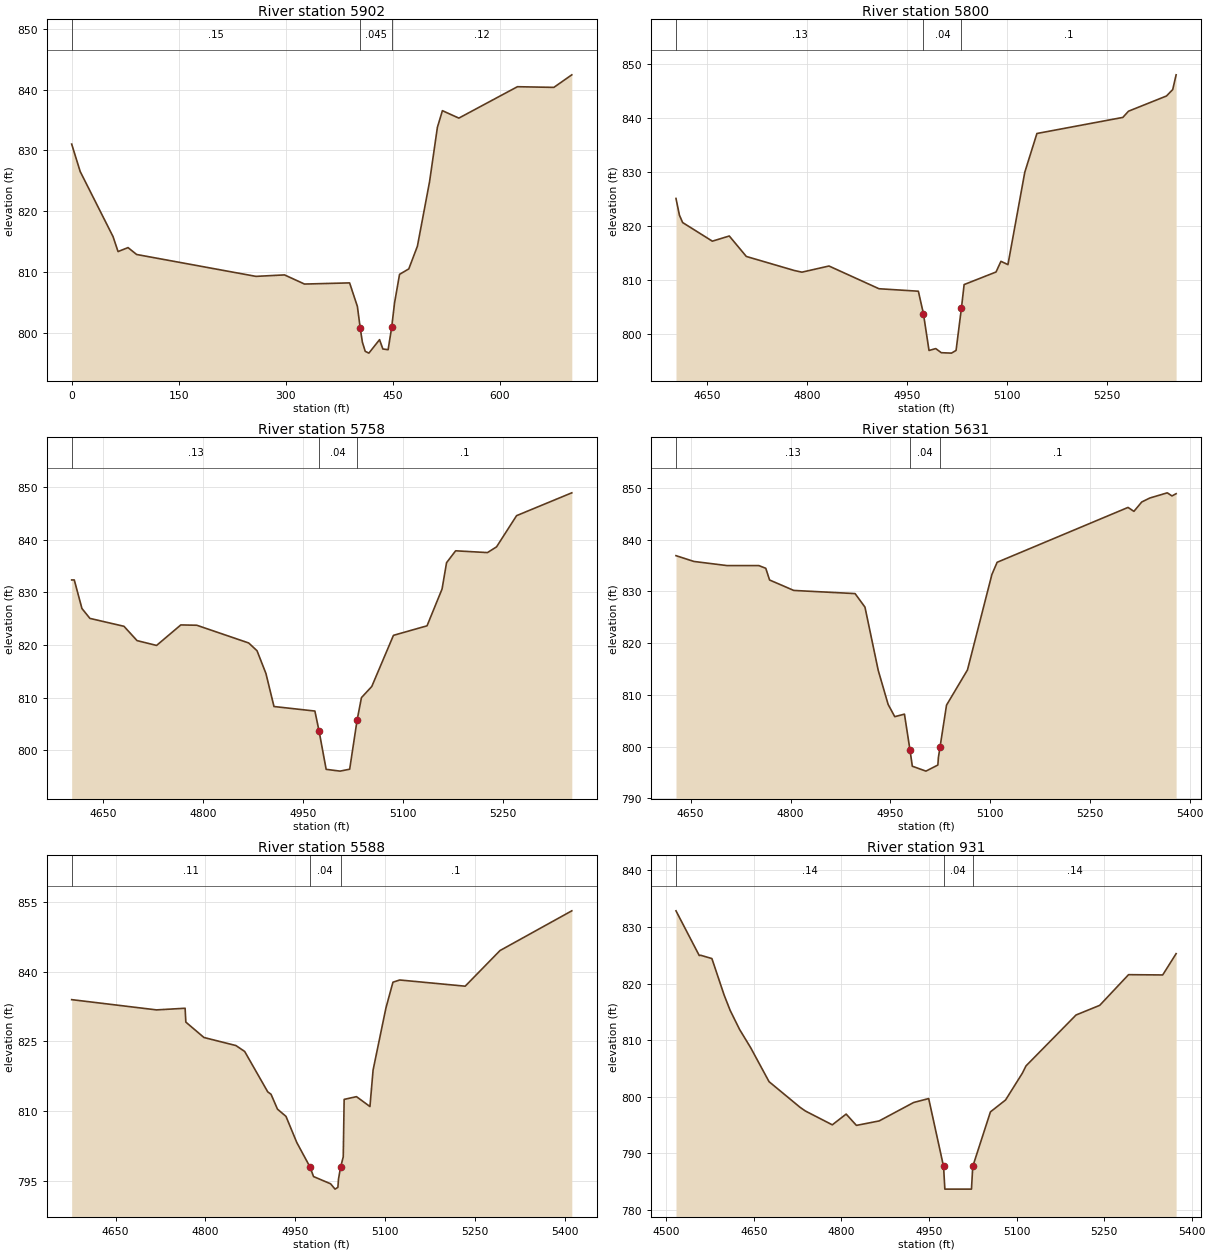
Type RM Length L Ch R = 1 ,5902    ,102,102,102
XS GIS Cut Line= 2
1551186.417496921094302.36684743 1550486.40119381094275.80076382
#Sta/Elev= 30
       0  831.05   11.93  826.55   57.96  815.87   64.96  813.42   78.97  814.07
   90.98  812.94   258.1  809.35  298.13  809.59  326.15  808.09   389.3  808.28
  400.21  804.42  404.21  800.83  407.21  798.55  411.21  797.05   416.3  796.76
  431.23  798.97  435.89  797.44  443.24  797.32  448.24  800.99  452.24  804.99
  459.25  809.68  472.22  810.58  484.27   814.3  501.28  824.87  512.29  833.81
  519.29  836.53  542.31  835.31  624.37  840.46   675.4  840.35  700.52  842.41
#Mann= 3 ,-1,0
       0     .15       0  404.21    .045       0  448.24     .12       0
Bank Sta=404.21,448.24
XS Rating Curve= 0 ,0
Exp/Cntr(USF)=0,0
Exp/Cntr=0.3,0.1

Type RM Length L Ch R = 1 ,5800    ,42,42,42
BEGIN DESCRIPTION:
Georges Creek 11.5
END DESCRIPTION:
XS GIS Cut Line= 2
      1551170.49       1094192.6    1550419.6349    1094182.1911
#Sta/Elev= 30
    4603  825.18    4603  825.16  4608.2  822.06    4613  820.71  4657.6  817.26
    4683  818.22  4708.6  814.43  4780.6  811.83  4792.1  811.52  4832.7  812.66
  4907.8  808.45  4966.9  807.99  4974.5  803.83  4982.9  797.01    4993  797.36
  5001.3   796.6  5016.6  796.52  5023.5  797.02  5031.6   804.9  5035.6  809.22
  5083.5  811.55  5090.9  813.53  5101.4  812.92  5126.7  830.04  5144.9  837.21
  5273.9  840.19  5282.4  841.34  5339.4  844.16  5348.8  845.35  5353.9  848.08
#Mann= 3 ,-1,0
    4603     .13       0  4974.5     .04       0  5031.6      .1       0
#XS Ineff= 2 , 0
Permanent Ineff=
       F       F
Bank Sta=4974.5,5031.6
XS Rating Curve= 0 ,0
Exp/Cntr=0.3,0.1

Type RM Length L Ch R = 1 ,5758    ,127,127,127
BEGIN DESCRIPTION:
Georges Creek 11.5
END DESCRIPTION:
XS GIS Cut Line= 2
    1551171.0722     1094150.604     1550420.217    1094140.1951
#Sta/Elev= 30
    4603  832.37 4606.91  832.37 4618.43  826.94 4630.42  825.06 4681.53  823.56
 4701.16  820.84 4730.48  819.92 4766.87  823.82 4790.84  823.76 4868.79  820.39
 4881.33  818.91 4894.71  814.58 4906.78  808.31 4968.19  807.45  4974.5  803.62
 4985.11  796.37 5006.02  796.03 5020.42   796.4  5031.6  805.75  5038.1     810
  5053.6  812.12 5086.16  821.84 5136.57  823.65 5159.13  830.65 5165.88  835.65
 5179.53  837.91 5227.28  837.57 5240.96  838.66 5271.01  844.59 5353.93  848.93
#Mann= 3 ,-1,0
    4603     .13       0  4974.5     .04       0  5031.6      .1       0
#XS Ineff= 2 , 0
Permanent Ineff=
       F       F
Bank Sta=4974.5,5031.6
XS Rating Curve= 0 ,0
Exp/Cntr=0.3,0.1

Type RM Length L Ch R = 1 ,5631    ,43,43,43
BEGIN DESCRIPTION:
Georges Creek 11.5
END DESCRIPTION:
XS GIS Cut Line= 2
    1551172.8326    1094023.6162    1550421.9774    1094013.2073
#Sta/Elev= 30
    4628  836.91 4654.91  835.79  4704.8  834.99 4752.48  834.99  4762.8  834.47
 4768.53  832.21 4804.86  830.19 4896.89  829.58 4911.73  826.97 4931.69  814.73
 4946.53  808.17 4956.48   805.8 4971.03  806.29 4979.42  799.29 4982.84  796.23
 5003.29  795.28  5021.2  796.46 5021.99  797.91 5024.45  799.92 5034.19  808.03
 5065.63  814.83 5102.32  833.27  5110.2  835.63 5306.74  846.23 5315.57  845.47
 5327.31  847.28 5339.32  848.04 5365.62  849.05 5372.73  848.45 5378.93  848.88
#Mann= 3 ,-1,0
    4628     .13       0 4979.42     .04       0 5024.45      .1       0
#XS Ineff= 2 , 0
Permanent Ineff=
       F       F
Bank Sta=4979.42,5024.45
XS Rating Curve= 0 ,0
Exp/Cntr=0.3,0.1

Type RM Length L Ch R = 1 ,5588    ,588,588,588
BEGIN DESCRIPTION:
Georges Creek 11.0
END DESCRIPTION:
XS GIS Cut Line= 3
       1551232.6      1093984.67      1550811.34      1093979.27
      1550398.19      1093990.08
#Sta/Elev= 30
  4576.8  833.96  4718.4  831.76  4766.1  832.114767.326 829.1354797.576 825.832
4850.913 824.1034865.506 822.8354904.031 814.1534909.492 813.6414920.245 810.455
4934.445 808.8964952.569 803.262  4974.5 798.0444980.428 795.9745008.932 794.421
  5016.3 793.2775021.068 793.6625022.041 795.413  5025.5 797.9675030.013 800.206
5031.502 812.5465052.072 813.1335074.556 811.0115079.796 818.8435101.183  832.15
 5112.93 837.7035124.261  838.18  5233.5  836.85  5291.6   844.5  5411.4  853.03
#Mann= 3 ,-1,0
  4576.8     .11       0  4974.5     .04       0  5025.5      .1       0
#XS Ineff= 2 , 0
Permanent Ineff=
       F       F
Bank Sta=4974.5,5025.5
XS Rating Curve= 0 ,0
Exp/Cntr=0.3,0.1

Type RM Length L Ch R = 1 ,931     ,416,416,416
BEGIN DESCRIPTION:
Georges Creek 2.0
END DESCRIPTION:
XS GIS Cut Line= 4
      1553528.36      1090361.89      1553254.23      1090374.35
      1552959.33      1090133.45      1552930.26      1089838.56
#Sta/Elev= 30
  4516.6  832.87  4556.4  824.98  4558.8  825.02  4578.1  824.44  4599.2  817.95
  4609.4  815.28  4625.5  811.92  4644.7  808.66    4676  802.69  4729.1  798.16
  4738.3   797.5  4784.4  795.06  4808.1  796.96  4825.7  794.96  4864.7  795.75
  4923.8  799.01  4949.5   799.7    4975   787.7  4977.2   783.7  5022.8   783.7
    5025   787.7  5055.3  797.35  5081.2  799.45  5109.9  804.17  5116.2  805.47
    5202  814.47  5242.5  816.17  5291.9  821.59  5350.4  821.54  5373.4   825.3
#Mann= 3 ,-1,0
  4516.6     .14       0    4975     .04       0    5025     .14       0
Bank Sta=4975,5025
XS Rating Curve= 0 ,0
Exp/Cntr=0.3,0.1

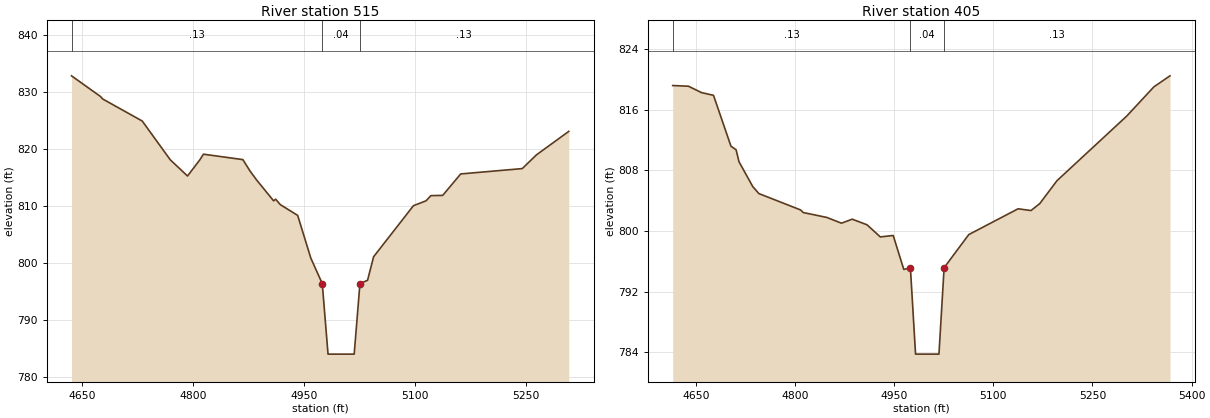
Type RM Length L Ch R = 1 ,515     ,110,110,110
BEGIN DESCRIPTION:
Georges Creek 1.8
END DESCRIPTION:
XS GIS Cut Line= 4
      1553558.25      1090119.36       1553424.7      1089949.13
      1553176.69      1089802.38      1553015.26      1089753.95
#Sta/Elev= 30
  4635.2   832.9  4674.5  829.26  4677.4  828.83  4730.9  824.96  4768.9  818.14
  4792.2   815.3  4808.6  818.09  4813.8  819.13  4867.1  818.18  4876.7   816.2
  4885.5  814.64  4908.7  810.94  4911.5  811.22  4917.9  810.26  4941.3  808.38
  4959.1  800.87  4974.6   796.4  4982.4     784  5017.8     784  5025.6   796.4
  5035.9  796.97  5044.1  801.11    5098  810.08  5115.1  810.94  5121.6  811.85
  5137.6  811.89    5162  815.66  5245.3   816.6  5264.5  819.01  5308.3  823.14
#Mann= 3 ,-1,0
  4635.2     .13       0  4974.6     .04       0  5025.6     .13       0
#XS Ineff= 2 , 0
Permanent Ineff=
       F       F
Bank Sta=4974.6,5025.6
XS Rating Curve= 0 ,0
Exp/Cntr=0.3,0.1

Type RM Length L Ch R = 1 ,405     ,67,67,67
BEGIN DESCRIPTION:
Georges Creek 1.5
END DESCRIPTION:
XS GIS Cut Line= 5
      1553658.04      1090044.52       1553533.3      1089910.98
      1553399.75      1089811.18      1553228.33      1089697.53
      1553031.41      1089701.12
#Sta/Elev= 30
  4615.1  819.18  4638.9  819.09  4658.9  818.24  4676.8  817.89  4703.2  811.18
    4711   810.7  4715.3  809.14  4736.2  805.85  4745.4  804.93  4808.5  802.77
  4812.4  802.43  4848.2  801.78  4870.4  801.02  4886.6  801.55    4909  800.81
  4929.1  799.21  4948.6   799.4  4964.6  794.92  4974.6  795.15  4982.4  783.75
  5017.8  783.75  5025.6  795.15  5062.9  799.52  5137.5  802.92    5157  802.69
  5170.3  803.61  5196.3  806.63  5301.8  815.15  5342.8     819  5367.2  820.46
#Mann= 3 ,-1,0
  4615.1     .13       0  4974.6     .04       0  5025.6     .13       0
#XS Ineff= 2 , 0
Permanent Ineff=
       F       F
Bank Sta=4974.6,5025.6
XS Rating Curve= 0 ,0
Exp/Cntr=0.3,0.1