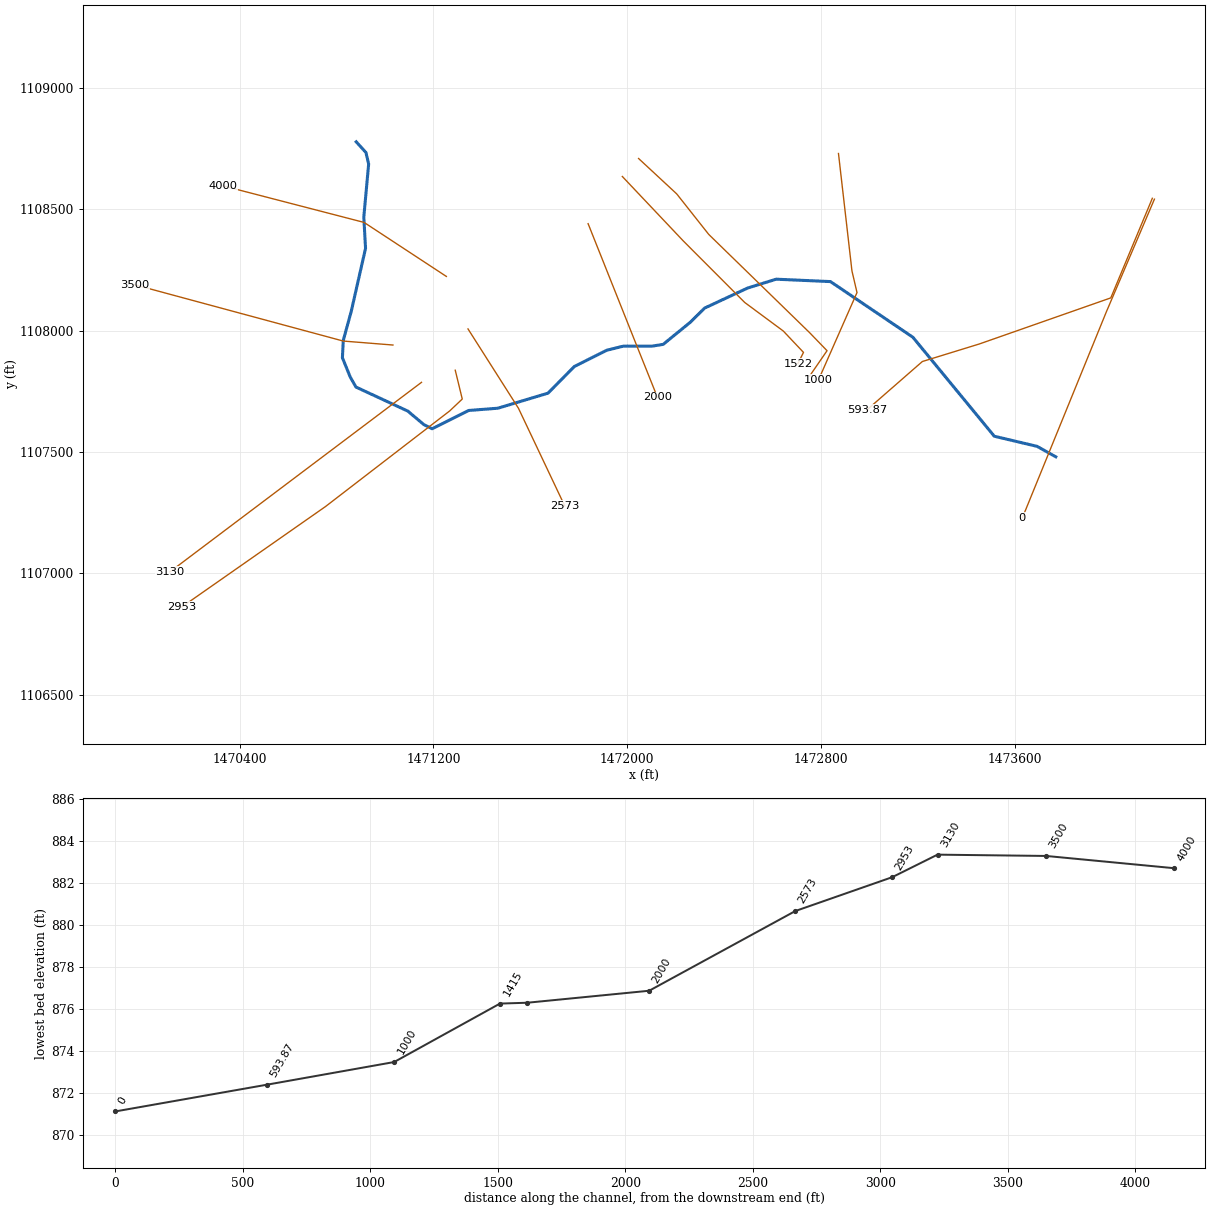
--- Cannon Creek.prj (project) ---

Proj Title=Cannon Creek Limited Detail Study
Current Plan=p16
Default Exp/Contr=0.3,0.1
English Units
Geom File=g01
Geom File=g02
Geom File=g09
Geom File=g03
Flow File=f01
Flow File=f02
Flow File=f03
Flow File=f04
Plan File=p01
Plan File=p06
Plan File=p02
Plan File=p05
Plan File=p04
Plan File=p11
Plan File=p16
Plan File=p17
Plan File=p18
Plan File=p03
Y Axis Title=Elevation
X Axis Title(PF)=Main Channel Distance
X Axis Title(XS)=Station
BEGIN DESCRIPTION:
Cannon Creek
END DESCRIPTION:
DSS File=dss
DSS Export Rating Curves= 0
DSS Export Rating Curve Sorted= 0
DSS Export Volume Flow Curves= 0
DXF OffsetX= 0
DXF OffsetY= 0
DXF ScaleX= 1
DXF ScaleY= 10

--- Cannon Creek.p16 (plan) ---

Plan Title=Revised (USGS)
Program Version=6.10
Short Identifier=Rev_USGS
Geom File=g03
Flow File=f02
Subcritical Flow
K Sum by GR= 0
Std Step Tol= 0.01
Critical Tol= 0.01
Num of Std Step Trials= 20
Max Error Tol= 0.3
Flow Tol Ratio= 0.001
Split Flow NTrial= 30
Split Flow Tol= 0.02
Split Flow Ratio= 0.02
Log Output Level= 0
Friction Slope Method= 1
Unsteady Friction Slope Method= 2
Unsteady Bridges Friction Slope Method= 1
Parabolic Critical Depth
Global Vel Dist= 0 , 0 , 0
Global Log Level= 0
CheckData=True
Encroach Param=-1 ,0,0, 0
BEGIN DESCRIPTION:
100Year Run
END DESCRIPTION:
Computation Interval=1HOUR
Output Interval=1HOUR
Instantaneous Interval=1HOUR
Mapping Interval=1HOUR
Computation Time Step Use Courant=        0
Computation Time Step Use Time Series=    0
Computation Time Step Count To Double=0
Computation Time Step Max Doubling=0
Computation Time Step Max Halving=0
Computation Time Step Residence Courant=0
Run HTab= 0
Run UNet= 0
Run Sediment= 0
Run PostProcess= 0
Run WQNet= 0
Run RASMapper= 0
UNET Theta= 1
UNET Theta Warmup= 1
UNET ZTol= 0.02
UNET ZSATol= 0.05
UNET MxIter= 20
UNET Max Iter WO Improvement= 0
UNET MaxInSteps= 0
UNET DtIC= 0
UNET DtMin= 0
UNET MaxCRTS= 20
UNET WFStab= 2
UNET SFStab= 1
UNET WFX= 1
UNET SFX= 1
UNET Gravity=32.174
UNET 1D Methodology=Finite Difference
UNET DSS MLevel= 4
UNET Pardiso=0
UNET DZMax Abort= 100
UNET Use Existing IB Tables=-1
UNET Froude Reduction=False
UNET Froude Limit= 1
UNET Froude Power= 10
UNET D1 Cores= 0
UNET WindReference=Eulerian
UNET WindDragFormulation=Hsu (1988)
UNET D2 Coriolis=0
UNET D2 Cores= 0
UNET D2 Theta= 1
UNET D2 Theta Warmup= 1
UNET D2 Z Tol= 0.01
UNET D2 Volume Tol= 0.01
UNET D2 Max Iterations= 20
UNET D2 Equation= 0
UNET D2 RampUpFraction=0.1
UNET D2 TimeSlices= 1
UNET D2 Turbulence Formulation=Non-Conservative (original)
UNET D2 Eddy Viscosity=0.3
UNET D2 Transverse Eddy Viscosity=0.1
UNET D2 Smagorinsky Mixing=0
UNET D2 BCVolumeCheck=0
UNET D2 Cores=0
UNET D2 SolverType=PARDISO (Direct)
UNET D2 Minimum Iterations= 2147483647
UNET D2 Maximum Iterations= 2147483647
UNET D2 Restart Number= 10
UNET D2 Relaxation Coeff=1.3
UNET D2 SOR Precondition Iterations= 10
UNET D2 ILUT Maximum Fill= 8
UNET D2 ILUT Tolerance=1E-08
UNET D1D2 MaxIter= 0
UNET D1D2 ZTol=0.01
UNET D1D2 QTol=0.1
UNET D1D2 MinQTol=1
Write IC File= 0
Write IC File at Fixed DateTime=0
Write IC File at Sim End=0
Echo Input=False
Echo Parameters=False
Echo Output=False
Write Detailed= 0
HDF Write Warmup=0
HDF Write Time Slices=0
HDF Flush=0
HDF Compression= 1
HDF Chunk Size= 1
HDF Spatial Parts= 1
HDF Use Max Rows=0
HDF Fixed Rows= 1
Calibration Method= 0
Calibration Iterations= 20
Calibration Max Change=0.05
Calibration Tolerance=0.2
Calibration Maximum=1.5
Calibration Minimum=0.5
Calibration Optimization Method= 1
WQ AD Non Conservative
WQ ULTIMATE=-1
WQ Max Comp Step=1HOUR
WQ Output Interval=15MIN
WQ Output Selected Increments= 0
WQ Output face flow=0
WQ Output face velocity=0
WQ Output face area=0
WQ Output face dispersion=0
WQ Output cell volume=0
WQ Output cell surface area=0
WQ Output cell continuity=0
WQ Output cumulative cell continuity=0
WQ Output face conc=0
WQ Output face dconc_dx=0
WQ Output face courant=0
WQ Output face peclet=0
WQ Output face adv mass=0
WQ Output face disp mass=0
WQ Output cell mass=0
WQ Output cell source sink temp=0
WQ Output nsm pathways=0
WQ Output nsm derived pathways=0
WQ Create Restart=0
WQ Fixed Restart=0
WQ System Summary=0
WQ Write To DSS=0
Sorting and Armoring Iterations= 10
XS Update Threshold= 0.02
Bed Roughness Predictor= 0
Hydraulics Update Threshold= 0.02
Energy Slope Method= 1
Volume Change Method= 1
Sediment Retention Method= 0
Sediment TS Multiplier= 1
Warm Up Method= 0
XS Weighting Method= 0
Number of US Weighted Cross Sections= 1
Number of DS Weighted Cross Sections= 1
Upstream XS Weight=0
Main XS Weight=1
Downstream XS Weight=0
Number of DS XS's Weighted with US Boundary= 1
Upstream Boundary Weight= 1
Weight of XSs Associated with US Boundary= 0
Number of US XS's Weighted with DS Boundary= 1
Downstream Boundary Weight= 0.5
Weight of XSs Associated with DS Boundary= 0.5
Percentile Method= 0
Sediment Output Level= 3
Mass or Volume Output= 0
Output Increment Type= 1
Profile and TS Output Increment= 1
Transport Output Increment 1
XS Output Flag= 0
XS Output Increment= 10
Read HDF5 Sediment Hotstart= 0
Sediment Hotstart Type= 0
Write Gradation File= 0
Read Gradation Hotstart= 0
Write HDF5 File= 1
Write Binary Output= 1
Write DSS Sediment File= 0
DSS Sediment Output Type= 1
SV Curve= 0
Specific Gage Flag= 0
Subcell Erosion Methods= 0
Subcell Deposition Methods= 0
Advection Scheme= 1
Matrix Solver= 0
Implicit Weighting Factor= 1
Maximum Outer Loop Convergence Iterations= 5
Convergence Maximum Absolute= 0.001
Convergence RMSE= 0.0001
Grain Fractions Max Abs Error= 0.001
Max Subgrid Regions= 1
Max Subgrid Length Scale= 3.402823E+38
Initial Layer Thickness= 3.402823E+38
Min Layer Thickness= 3.402823E+38
Max Layer Thickness= 3.402823E+38
Number of Layers= 5

--- Cannon Creek.p01 (plan) ---

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Plan Title=100-Year Single
Short Identifier=100Year
Geom File=g02
Flow File=f01

--- Cannon Creek.p02 (plan) ---

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Plan Title=Corrected (FEMA)
Short Identifier=Cor_FEMA
Geom File=g01
Flow File=f01

--- Cannon Creek.p03 (plan) ---

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Plan Title=Effective
Short Identifier=Effective
Geom File=g02
Flow File=f01

--- Cannon Creek.p04 (plan) ---

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Plan Title=Sensitivity-3
Short Identifier=Sen-3
Geom File=g09
Flow File=f04

--- Cannon Creek.p05 (plan) ---

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Plan Title=Sensitivity+3
Short Identifier=Sen+3
Geom File=g09
Flow File=f03

--- Cannon Creek.p06 (plan) ---

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Plan Title=Sensitivity
Short Identifier=Sen
Geom File=g09
Flow File=f01

--- Cannon Creek.p11 (plan) ---

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Plan Title=Revised (FEMA)
Short Identifier=Rev_FEMA
Geom File=g03
Flow File=f01

--- Cannon Creek.p17 (plan) ---

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Plan Title=Corrected (USGS)
Short Identifier=Cor_USGS
Geom File=g01
Flow File=f02

--- Cannon Creek.p18 (plan) ---

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Plan Title=Unrestricted (USGS)
Short Identifier=UnR_USGS
Geom File=g09
Flow File=f02

--- Cannon Creek.f02 (steady flow) ---

Flow Title=USGS Flows
Program Version=6.10
Number of Profiles= 5
Profile Names=10% AEP,4% AEP,2% AEP,1% AEP,0.2% AEP
River Rch & RM=Cannon Creek,Reach-1         ,4000
    1120    1480    1810    2100    2850
Boundary for River Rch & Prof#=Cannon Creek,Reach-1         , 1
Up Type= 0
Dn Type= 3
Dn Slope=0.0067
DSS Import GetInterval= 0
DSS Import GetPeak= 0
DSS Import FillOption= 0

--- Cannon Creek.f01 (steady flow) ---

Flow Title=100-year Single
Program Version=6.10
Number of Profiles= 1
Profile Names=100-year
River Rch & RM=Cannon Creek,Reach-1         ,4000
    1552
Boundary for River Rch & Prof#=Cannon Creek,Reach-1         , 1
Up Type= 0
Dn Type= 3
Dn Slope=0.0067
DSS Import GetInterval= 0
DSS Import GetPeak= 0
DSS Import FillOption= 0

--- Cannon Creek.f03 (steady flow) ---

Flow Title=Sensitivity +3
Program Version=6.10
Number of Profiles= 1
Profile Names=1% AEP
River Rch & RM=Cannon Creek,Reach-1         ,4000
    1522
Boundary for River Rch & Prof#=Cannon Creek,Reach-1         , 1
Up Type= 0
Dn Type= 1
Dn Known WS=879.87
DSS Import GetInterval= 0
DSS Import GetPeak= 0
DSS Import FillOption= 0

--- Cannon Creek.f04 (steady flow) ---

Flow Title=Sensitivity -3
Program Version=6.10
Number of Profiles= 1
Profile Names=1% AEP
River Rch & RM=Cannon Creek,Reach-1         ,4000
    1522
Boundary for River Rch & Prof#=Cannon Creek,Reach-1         , 1
Up Type= 0
Dn Type= 1
Dn Known WS=873.97
DSS Import GetInterval= 0
DSS Import GetPeak= 0
DSS Import FillOption= 0

--- Cannon Creek.g03 (geometry) ---

Geom Title=Revised - 150'
Program Version=6.10

River Reach=Cannon Creek    ,Reach-1
Reach XY= 30
      1470881.43      1108777.89      1470921.55      1108733.76
      1470932.79      1108686.42      1470912.73      1108467.75
      1470919.95      1108338.97       1470860.9      1108079.34
      1470828.07      1107959.77      1470824.43      1107888.39
      1470856.73      1107808.68      1470880.47      1107767.39
      1471094.54      1107668.28       1471160.6      1107612.79
      1471194.96      1107595.61      1471345.59      1107670.93
      1471465.84      1107680.17      1471673.29      1107742.28
      1471781.65      1107851.95      1471915.28      1107918.92
      1471984.94      1107936.16      1472104.17      1107936.16
      1472148.69      1107943.34      1472260.74      1108034.56
      1472319.63      1108092.73      1472497.03      1108175.33
      1472615.01      1108211.83      1472839.28      1108201.97
      1473179.37      1107972.78      1473515.56      1107564.79
      1473692.12      1107523.13    1473769.5699    1107479.9626

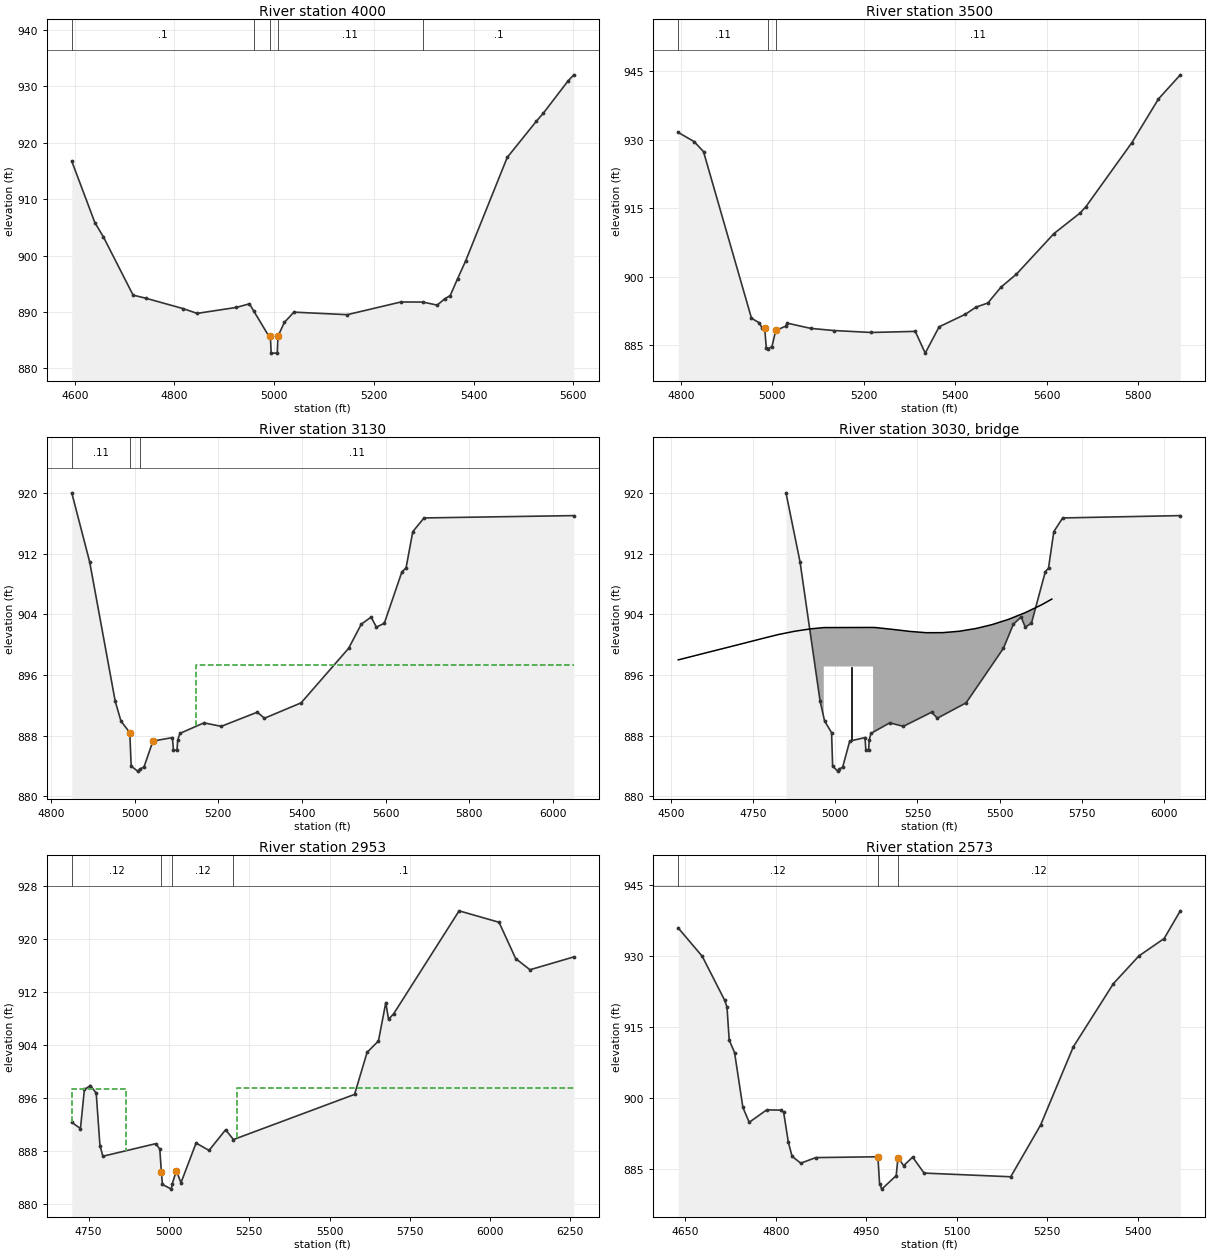
Type RM Length L Ch R = 1 ,4000    ,500,500,500
BEGIN DESCRIPTION:
Cannon Creek 8.0
END DESCRIPTION:
XS GIS Cut Line= 3
      1471253.59      1108223.22      1470913.96      1108445.72
      1470332.14      1108596.32
#Sta/Elev= 30
    4594  916.75  4640.3  905.86  4657.5  903.31    4717  892.99  4742.6  892.44
  4817.6  890.59  4845.4  889.75  4924.2  890.81  4950.3  891.45  4959.3  890.12
  4990.1   885.6  4992.4   885.7  4993.9   882.7  5006.1   882.7  5007.6   885.7
  5020.3  888.14  5039.5  889.97  5146.4  889.52    5254  891.77  5298.1  891.76
  5326.9  891.22  5341.7  892.31  5353.1  892.92  5367.9  895.92  5383.7     899
  5467.4  917.42  5525.9  923.85    5540  925.29  5589.8  931.03    5601  932.07
#Mann= 5 ,-1,0
    4594      .1       0  4959.3     .11       0  4992.4     .04       0
  5007.6     .11       0  5298.1      .1       0
Bank Sta=4992.4,5007.6
XS Rating Curve= 0 ,0
Exp/Cntr=0.3,0.1

Type RM Length L Ch R = 1 ,3500    ,426,426,426
BEGIN DESCRIPTION:
Cannon Creek 7.0
END DESCRIPTION:
XS GIS Cut Line= 3
      1471033.12      1107940.57      1470827.83      1107956.96
      1469965.78      1108189.21
#Sta/Elev= 30
  4794.1  931.59    4829  929.58  4849.4  927.39  4954.4  890.92 4971.47 889.916
 4977.07 888.871 4983.23  888.88 4986.73 884.481 4991.27 884.289 4999.25 884.727
 5007.37 888.244 5029.01 889.167 5032.55 889.846  5083.8   888.7  5133.9  888.23
  5216.5   887.8  5312.8  888.04  5334.6  883.28    5365  889.04  5422.6   891.8
  5445.7  893.35  5471.6  894.25  5500.7  897.76  5533.9  900.54  5616.3  909.45
  5673.3  913.94  5686.3  915.35  5786.9  929.37  5844.9  938.91  5892.8   944.2
#Mann= 3 ,-1,0
  4794.1     .11       0 4991.27     .04       0 5007.37     .11       0
Bank Sta=4983.23,5007.37
XS Rating Curve= 0 ,0
Exp/Cntr=0.5,0.3

Type RM Length L Ch R = 1 ,3130    ,177.72,177.72,177.72
XS GIS Cut Line= 2
     1471151.004    1107786.8875      1470112.28      1107006.04
#Sta/Elev= 30
    4850     920 4892.77 910.901 4953.83 892.551 4967.57 889.936 4988.73 888.409
 4991.96 884.011 5007.24 883.342 5012.53 883.613 5022.59 883.885 5043.97 887.299
 5090.52 887.761 5093.08 886.101 5101.49 886.101 5103.24 887.441  5108.6 888.315
 5165.89 889.699 5207.18  889.24 5293.32 891.104 5310.56  890.31 5398.17 892.336
 5511.77 899.524 5541.98   902.7  5565.5 903.632 5578.11 902.311 5596.98 902.816
 5639.19 909.611  5648.9 910.086 5665.06 914.889 5691.93 916.692    6050     917
#Mann= 3 ,-1,0
    4850     .11       0 4988.73     .04       0 5012.53     .11       0
#XS Ineff= 2 , 0
       0    4932  897.32    5148       0  897.32
Permanent Ineff=
       F       F
Bank Sta=4988.73,5043.97
XS Rating Curve= 0 ,0
Exp/Cntr=0.5,0.3

Type RM Length L Ch R = 3 ,3030    ,,,
BEGIN DESCRIPTION:
Walhalla Hwy (Cannon Creek xing)
Structure ID: LDS_CNC_02
Approximate Survey Structure
END DESCRIPTION:
Bridge Culvert--1,0,-1,-1, 0
Deck Dist Width WeirC Skew NumUp NumDn MinLoCord MaxHiCord MaxSubmerge Is_Ogee
33,46.25,3,0, 59, 59, , , , 0, 1,1,,
4522.0884526.8864527.0034576.5744577.0034613.3664626.5144627.0034675.5684677.002
 4725.494727.0014776.332    47774795.6674795.6674826.591    48274876.828    4877
4884.471 4887.814896.4894926.733    49274927.2674956.092    4965    51155126.892
5126.9995176.9995176.9995196.3785199.2755226.0085226.9995275.0595276.9985324.978
5326.9965328.9825376.9955378.1155409.8225426.995 5476.575476.9955502.966 5526.73
5526.9955565.6625565.662 5576.865576.9955615.8775626.9955627.0385658.928
     898 898.048 898.049 898.593 898.598     899 899.142 899.148 899.677 899.693
 900.226 900.243 900.789 900.797     901     901 901.329 901.334 901.769 901.771
 901.819 901.841 901.897  902.09 902.092 902.093 902.213  902.25 902.268 902.235
 902.235     902     902 901.903 901.889  901.75 901.745 901.583 901.576 901.583
 901.583  901.59 901.765 901.773     902 902.118 902.634 902.639     903 903.328
 903.331     904     904 904.193 904.195     905  905.23 905.231     906
                                                                                
                                                                                
                                                         897.125 897.118
                                                                                
                                                                                
                                                                        
4522.0884526.8864527.0034576.5744577.0034613.3664626.5144627.0034675.5684677.002
 4725.494727.0014776.332    47774795.6674795.6674826.591    48274876.828    4877
4884.471 4887.814896.4894926.733    49274927.2674956.092    4965    51155126.892
5126.9995176.9995176.9995196.3785199.2755226.0085226.9995275.0595276.9985324.978
5326.9965328.9825376.9955378.1155409.8225426.995 5476.575476.9955502.966 5526.73
5526.9955565.6625565.662 5576.865576.9955615.8775626.9955627.0385658.928
     898 898.048 898.049 898.593 898.598     899 899.142 899.148 899.677 899.693
 900.226 900.243 900.789 900.797     901     901 901.329 901.334 901.769 901.771
 901.819 901.841 901.897  902.09 902.092 902.093 902.213  902.25 902.268 902.235
 902.235     902     902 901.903 901.889  901.75 901.745 901.583 901.576 901.583
 901.583  901.59 901.765 901.773     902 902.118 902.634 902.639     903 903.328
 903.331     904     904 904.193 904.195     905  905.23 905.231     906
                                                                                
                                                                                
                                                         897.125 897.118
                                                                                
                                                                                
                                                                        
Pier Skew, UpSta & Num, DnSta & Num=  ,5050, 2 ,5050, 2 , 0 , 0 , 0 ,,
       4       4
     880     900
       4       4
     880     900
Abutment Skew #Up #Dn= , 3 , 3
    4965    4967  4976.5
  893.75  893.75     889
    4965    4967  4976.5
  893.75  893.75     889
Abutment Skew #Up #Dn= , 3 , 3
  5097.5    5113    5115
     886  893.75  893.75
  5097.5    5113    5115
     886  893.75  893.75
BR Coef= 1 , 1 , 0 ,1.25, 0 ,,,0.8,0,2,0,
WSPro=,,,, 1 ,,,, 0 ,,,, 0 ,,,,-1 ,-1 ,-1 , 0 , 0 , 0 , 0 , 0
BC Design=,, 0 ,, 0 ,,,,,,
BC HTab HWMax=921.92
BC Use User HTab Curves=0
BC User HTab FreeFlow(D)= 0

Type RM Length L Ch R = 1 ,2953    ,380,380,380
BEGIN DESCRIPTION:
Cannon Creek 6.0
END DESCRIPTION:
XS GIS Cut Line= 5
      1471290.29      1107836.73      1471319.23      1107718.06
      1471267.13      1107668.86      1470754.83      1107275.22
      1470161.48      1106861.32
#Sta/Elev= 30
  4697.5  892.37 4724.55  891.42  4736.8  897.32 4755.55  897.92 4773.61  896.78
 4785.23  888.84 4794.49  887.24 4959.15  889.14 4971.61  888.31 4976.51   884.8
 4979.86  882.98 5007.59  882.27 5010.32  883.07 5023.17  885.06 5037.52  883.23
 5084.56  889.23 5124.95  888.12 5176.56  891.24 5200.95  889.76 5578.01  896.58
 5617.08  902.93  5652.4  904.65 5675.33  910.46 5683.75  907.93 5699.73  908.75
 5903.56  924.31 6027.92  922.58 6079.68   917.1 6124.21  915.41 6260.82  917.35
#Mann= 4 ,-1,0
  4697.5     .12       0 4976.51    .045       0 5010.32     .12       0
 5200.95      .1       0
#XS Ineff= 2 , 0
       0 4866.53  897.35    5213       0  897.61
Permanent Ineff=
       F       F
Bank Sta=4976.51,5023.17
XS Rating Curve= 0 ,0
Exp/Cntr=0.5,0.3

Type RM Length L Ch R = 1 ,2573    ,573,573,573
BEGIN DESCRIPTION:
Cannon Creek 5.0
END DESCRIPTION:
XS GIS Cut Line= 3
      1471342.91      1108006.94      1471551.21      1107680.02
      1471742.16      1107277.88
#Sta/Elev= 30
    4638  935.99 4677.82     930 4714.98  920.69 4718.86  919.26 4722.55  912.23
 4731.45  909.59 4745.24  897.97 4755.73  894.82 4784.82  897.46 4808.82   897.4
 4812.86  896.94 4820.54  890.67 4826.78  887.61 4841.28  886.16 4866.14  887.34
  4969.2  887.52 4971.95  881.81 4975.58  880.66 4999.51  883.52 5002.49  887.34
 5011.91  885.64 5026.88  887.44  5045.8  884.06  5189.5  883.28  5238.9   894.2
  5293.3  910.81  5359.9  924.22  5402.1  930.07  5443.9  933.75  5470.8  939.63
#Mann= 3 ,-1,0
    4638     .12       0  4969.2    .045       0 5002.49     .12       0
Bank Sta=4969.2,5002.49
XS Rating Curve= 0 ,0
Exp/Cntr=0.3,0.1

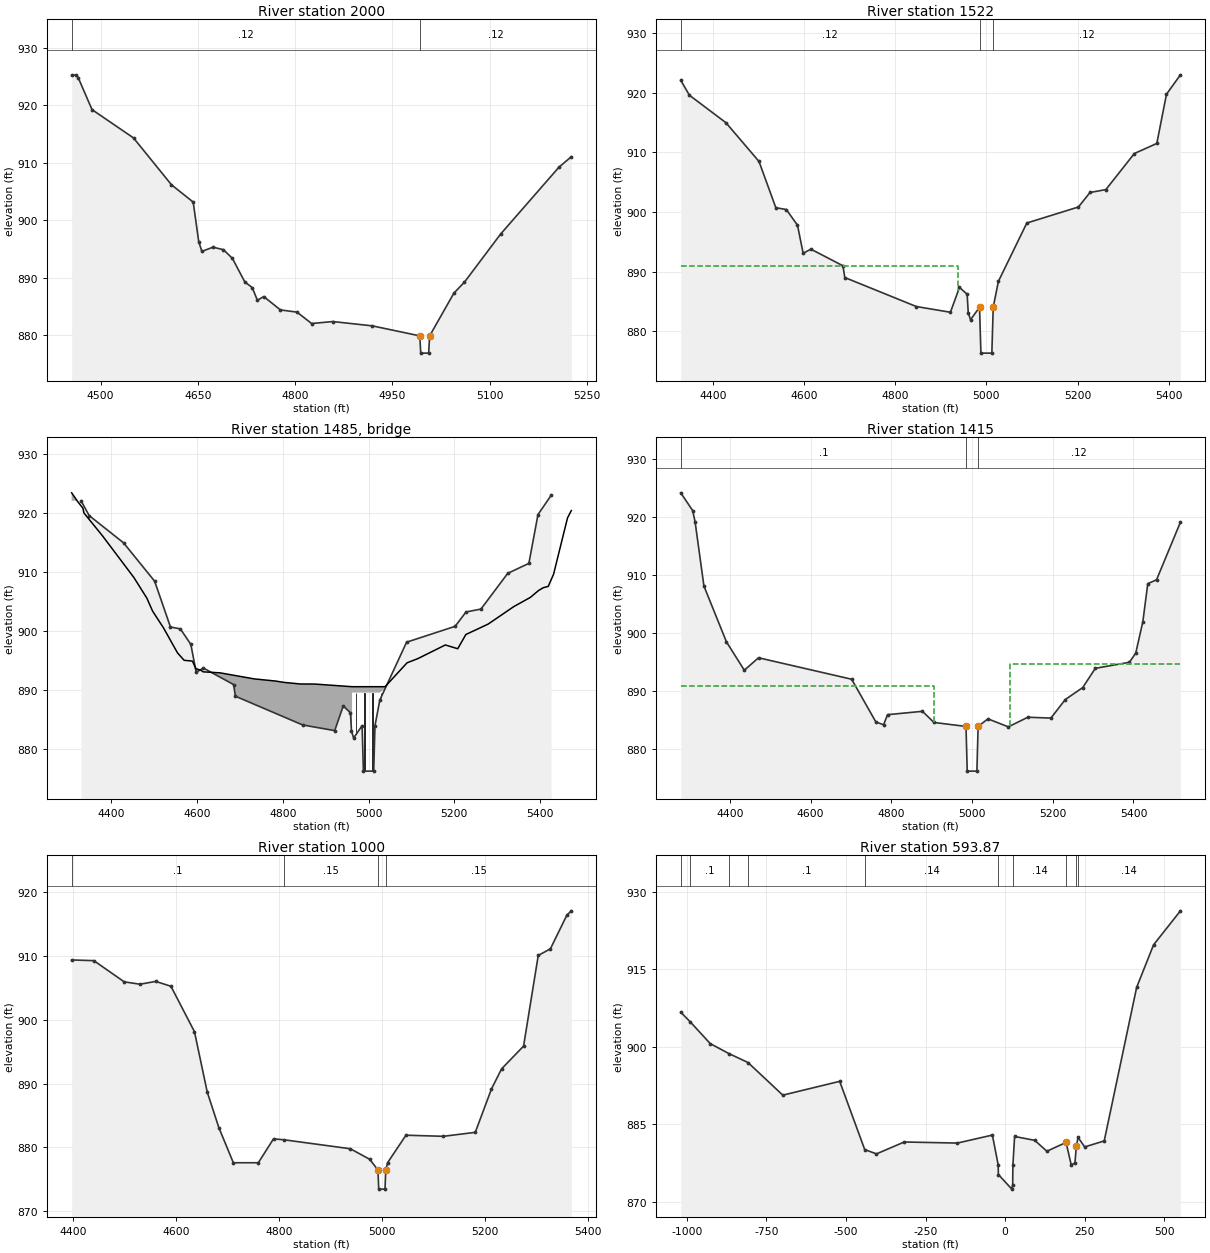
Type RM Length L Ch R = 1 ,2000    ,478,478,478
BEGIN DESCRIPTION:
Cannon Creek 4.0
END DESCRIPTION:
XS GIS Cut Line= 3
      1471838.77       1108440.5      1472040.76      1107934.83
        1472125.        1107725.
#Sta/Elev= 30
  4455.5  925.14  4462.9  925.25 4465.65  924.75 4486.94   919.2 4550.93  914.28
 4609.49  906.13 4642.97  903.13 4651.47  896.26 4656.34  894.55 4673.44  895.29
 4689.64  894.85 4703.43  893.34 4722.55  889.25  4734.1  888.25 4741.94  886.06
 4751.84   886.7 4777.47  884.38 4802.99     884  4825.6  882.02  4858.3  882.36
  4919.2  881.61  4992.4  879.87  4993.9  876.87  5006.1  876.87  5007.6  879.87
  5045.1  887.31  5061.3  889.21    5117  897.56  5207.1   909.2  5226.1  911.01
#Mann= 2 ,-1,0
  4455.5     .12       0  4992.4     .12       0
Bank Sta=4992.4,5007.6
XS Rating Curve= 0 ,0
Exp/Cntr=0.5,0.3

Type RM Length L Ch R = 1 ,1522    ,107,107,107
BEGIN DESCRIPTION:
Cannon Creek 3.5
END DESCRIPTION:
XS GIS Cut Line= 6
      1471980.02        1108635.      1472232.41      1108368.72
       1472484.8      1108116.33      1472644.57      1107998.24
      1472727.93      1107910.25      1472704.77      1107863.94
#Sta/Elev= 30
  4329.9  922.09  4348.8  919.59    4429  914.97 4501.44  908.47 4538.31  900.71
 4561.34   900.4 4585.82  897.77 4598.25  893.06 4615.28  893.75 4685.47  890.96
 4689.56  888.99  4846.4  884.12 4921.19  883.16 4940.99  887.33 4957.81  886.19
 4960.24  883.07 4965.28  881.91    4985     884    4988   876.3    5012   876.3
    5015     884  5026.3  888.34  5088.7  898.14  5201.9  900.83  5227.2  903.26
    5262  903.75  5324.4   909.8  5373.7  911.49  5394.9  919.75  5425.5  923.01
#Mann= 3 ,-1,0
  4329.9     .12       0    4985     .05       0    5015     .12       0
#XS Ineff= 2 , 0
       0    4938  890.84    5062       0  892.46
Permanent Ineff=
       F       F
Bank Sta=4985,5015
XS Rating Curve= 0 ,0
Exp/Cntr=0.5,0.3

Type RM Length L Ch R = 3 ,1485    ,,,
BEGIN DESCRIPTION:
Winchester Mill Rd (Cannon Cr xing)
Structure ID: LDS_CNC_01
Approximate Survey Structure
END DESCRIPTION:
Bridge Culvert--1,0,-1,-1, 0
Deck Dist Width WeirC Skew NumUp NumDn MinLoCord MaxHiCord MaxSubmerge Is_Ogee
23.5,27,3,0, 39, 39, , , , 0, 1,1,,
    4308  4323.1  4334.4  4336.6  4379.4  4452.9  4483.3  4496.7  4522.2  4554.7
  4570.2  4589.5  4597.6    4609  4614.3  4653.7  4733.9  4783.2  4803.2  4841.2
  4874.6  4961.5  4961.5  5038.5  5038.5  5089.8    5115    5179  5207.9  5226.8
  5278.9  5338.3  5377.2    5396  5407.2  5418.8  5431.2  5463.8  5472.6
  923.44  921.86  920.82  920.03   916.2  909.11   905.6   903.4  900.55  896.33
  895.07  894.94  893.65  893.41  893.12  892.95  891.92  891.56  891.33  891.06
  891.05   890.6   890.6   890.6   890.6  894.65  895.36  897.67  897.03  899.44
  901.21  904.16  905.73  906.88  907.37  907.59  909.64   919.2  920.43
   856.3   856.3   856.3   856.3   856.3   856.3   856.3   856.3   856.3   856.3
   856.3   856.3   856.3   856.3   856.3   856.3   856.3   856.3   856.3   856.3
   856.3   856.3   889.6   889.6   856.3   856.3   856.3   856.3   856.3   856.3
   856.3   856.3   856.3   856.3   856.3   856.3   856.3   856.3   856.3
    4308  4323.1  4334.4  4336.6  4379.4  4452.9  4483.3  4496.7  4522.2  4554.7
  4570.2  4589.5  4597.6    4609  4614.3  4653.7  4733.9  4783.2  4803.2  4841.2
  4874.6  4961.5  4961.5  5038.5  5038.5  5089.8    5115    5179  5207.9  5226.8
  5278.9  5338.3  5377.2    5396  5407.2  5418.8  5431.2  5463.8  5472.6
  923.44  921.86  920.82  920.03   916.2  909.11   905.6   903.4  900.55  896.33
  895.07  894.94  893.65  893.41  893.12  892.95  891.92  891.56  891.33  891.06
  891.05   890.6   890.6   890.6   890.6  894.65  895.36  897.67  897.03  899.44
  901.21  904.16  905.73  906.88  907.37  907.59  909.64   919.2  920.43
   856.3   856.3   856.3   856.3   856.3   856.3   856.3   856.3   856.3   856.3
   856.3   856.3   856.3   856.3   856.3   856.3   856.3   856.3   856.3   856.3
   856.3   856.3   889.6   889.6   856.3   856.3   856.3   856.3   856.3   856.3
   856.3   856.3   856.3   856.3   856.3   856.3   856.3   856.3   856.3
Pier Skew, UpSta & Num, DnSta & Num=  ,4971.1, 2 ,4971.1, 2 , 0 , 0 , 0 ,0,0
       1       1
  883.15   889.6
       1       1
  882.99   889.6
Pier Skew, UpSta & Num, DnSta & Num=  ,4990.4, 2 ,4990.4, 2 , 0 , 0 , 0 ,0,0
       1       1
   876.3   889.6
       1       1
  876.05   889.6
Pier Skew, UpSta & Num, DnSta & Num=  ,5009.6, 2 ,5009.6, 2 , 0 , 0 , 0 ,0,0
       1       1
   876.3   889.6
       1       1
  876.05   889.6
Pier Skew, UpSta & Num, DnSta & Num=  ,5028.9, 2 ,5028.9, 2 , 0 , 0 , 0 ,0,0
       1       1
  888.82   889.6
       1       1
  882.24   889.6
Abutment Skew #Up #Dn= , 2 , 2
  4961.5  4965.5
   889.6  883.43
  4961.5  4965.5
   889.6  883.38
Abutment Skew #Up #Dn= , 2 , 2
  5034.5  5038.5
  889.84   889.6
  5034.5  5038.5
  883.86   889.6
BR Coef= 1 , 1 , 0 ,1.25, 0 ,,,0.8,0,2,0,
WSPro=,,,, 1 ,,,, 0 ,,,, 0 ,,,,-1 ,-1 ,-1 , 0 , 0 , 0 , 0 , 0
BC Design=,, 0 ,, 0 ,,,,,,
BC HTab HWMax=923.01
BC Use User HTab Curves=0
BC User HTab FreeFlow(D)= 0

Type RM Length L Ch R = 1 ,1415    ,415,415,415
BEGIN DESCRIPTION:
Cannon Creek 3.0
END DESCRIPTION:
XS GIS Cut Line= 6
      1472047.17       1108709.1      1472204.62      1108563.22
      1472336.61       1108396.5       1472753.4      1107991.29
      1472825.18      1107917.19       1472753.4        1107813.
#Sta/Elev= 30
  4278.1  924.23  4307.7  921.16  4313.6  919.22  4335.5  908.16  4391.3  898.54
  4435.6  893.65 4470.77   895.8 4701.56   892.1 4761.53  884.74 4780.75  884.25
 4790.59  885.99 4877.08  886.57 4905.45  884.65    4985  883.96    4988  876.26
    5012  876.26    5015  883.96  5039.4  885.27  5089.9  883.89  5138.2  885.55
  5195.4   885.4    5231   888.6  5274.2  890.66  5305.5  893.98  5389.9  895.02
  5405.6  896.59  5423.2     902  5435.5  908.57  5457.2  909.24  5516.4  919.17
#Mann= 3 ,-1,0
  4278.1      .1       0    4985     .05       0    5015     .12       0
#XS Ineff= 2 , 0
       0    4905  890.88    5095       0   894.8
Permanent Ineff=
       F       F
Bank Sta=4985,5015
XS Rating Curve= 0 ,0
Exp/Cntr=0.5,0.3

Type RM Length L Ch R = 1 ,1000    ,500,500,500
BEGIN DESCRIPTION:
Cannon Creek 2.0
END DESCRIPTION:
XS GIS Cut Line= 4
      1472872.36       1108729.7      1472927.91      1108246.36
      1472948.82      1108156.77      1472790.55      1107798.44
#Sta/Elev= 30
  4397.6  909.36  4440.7  909.25  4499.7  905.93  4530.3  905.56  4560.8     906
  4590.4  905.24  4636.1  898.13  4660.9  888.68  4683.5   883.1  4711.6  877.61
  4760.1  877.61  4789.6  881.35  4810.5   881.2  4938.8   879.8  4976.2  878.16
  4992.4  876.48  4993.9  873.48  5006.1  873.48  5007.6  876.48  5011.1  877.61
  5046.8  881.92  5119.6  881.75  5181.4  882.37  5212.9  889.17  5232.5  892.31
  5275.2  895.87  5303.7  910.07  5327.3   911.1  5359.1  916.35  5367.9  917.05
#Mann= 4 ,-1,0
  4397.6      .1       0  4810.5     .15       0  4992.4     .05       0
  5007.6     .15       0
Bank Sta=4992.4,5007.6
XS Rating Curve= 0 ,0
Exp/Cntr=0.3,0.1

Type RM Length L Ch R = 1 ,593.87  ,593.87,593.87,593.87
XS GIS Cut Line= 5
    1474168.0512    1108545.2047    1473996.5472    1108134.8212
    1473453.8616    1107944.9426    1473218.6568     1107872.666
    1472989.0978    1107672.7759
#Sta/Elev= 30
-1019.34   906.7 -988.89  904.79 -926.67  900.61 -867.62  898.67 -808.13  896.95
 -698.68  890.62 -519.92   893.3 -441.33  880.08 -404.44  879.23 -317.04  881.54
 -150.11  881.33  -40.11  882.88  -21.86  877.11  -21.21  875.23   20.95   872.4
   23.65  873.28   24.31     877   29.74  882.61   92.94  881.86  131.07  879.75
  191.41  881.45  207.61  877.12  219.32  877.46  223.69   880.7  229.11  882.44
  249.96  880.58  311.32  881.75  413.26  911.52  466.42  919.77  550.83  926.36
#Mann= 10 ,-1,0
-1019.34     .14       0 -988.89      .1       0 -867.62     .14       0
 -808.13      .1       0 -441.33     .14       0  -21.86     .04       0
   24.31     .14       0  191.41     .04       0  223.69      .1       0
  229.11     .14       0
Bank Sta=191.41,223.69
XS Rating Curve= 0 ,0
Exp/Cntr=0.3,0.1

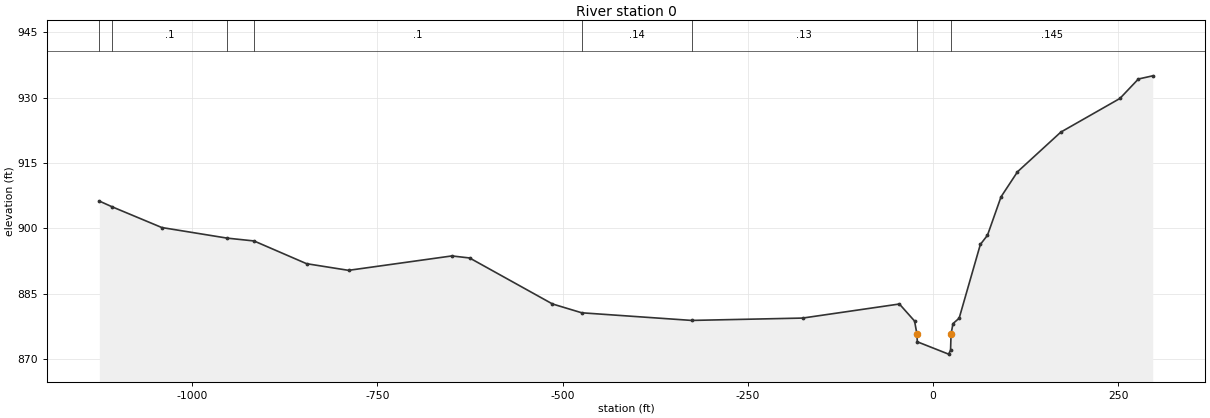
Type RM Length L Ch R = 1 ,0       ,0,0,0
XS GIS Cut Line= 3
    1474176.6263    1108541.5295    1473978.1719    1108077.2451
    1473631.4603     1107228.331
#Sta/Elev= 30
-1125.39  906.28-1108.38  904.98-1041.04   900.2 -952.89  897.77 -916.62  897.12
 -845.65   891.9 -789.02  890.37 -649.54  893.68 -625.53  893.21 -513.71  882.65
 -474.13  880.62 -325.87  878.87 -176.06  879.41  -45.41  882.64  -24.94  878.73
  -21.86  875.84  -21.21  873.96   20.95  871.13   23.65  872.01   24.31  875.73
   26.92  878.14   35.25  879.38   63.87  896.32   73.48  898.43   91.78  907.25
     114     913  172.46  922.11  252.23  929.84  277.18  934.31  296.57  935.04
#Mann= 8 ,-1,0
-1125.39     .14       0-1108.38      .1       0 -952.89     .14       0
 -916.62      .1       0 -474.13     .14       0 -325.87     .13       0
  -21.86     .04       0   24.31    .145       0
Bank Sta=-21.86,24.31
XS Rating Curve= 0 ,0
Exp/Cntr=0.3,0.1
LCMann Table=0

Chan Stop Cuts=-1
Use User Specified Reach Order=0
Composite Channel Slope=5

--- Cannon Creek.g01 (geometry) ---

Geom Title=Corrected Effective
Program Version=6.10

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
River Reach=Cannon Creek    ,Reach-1

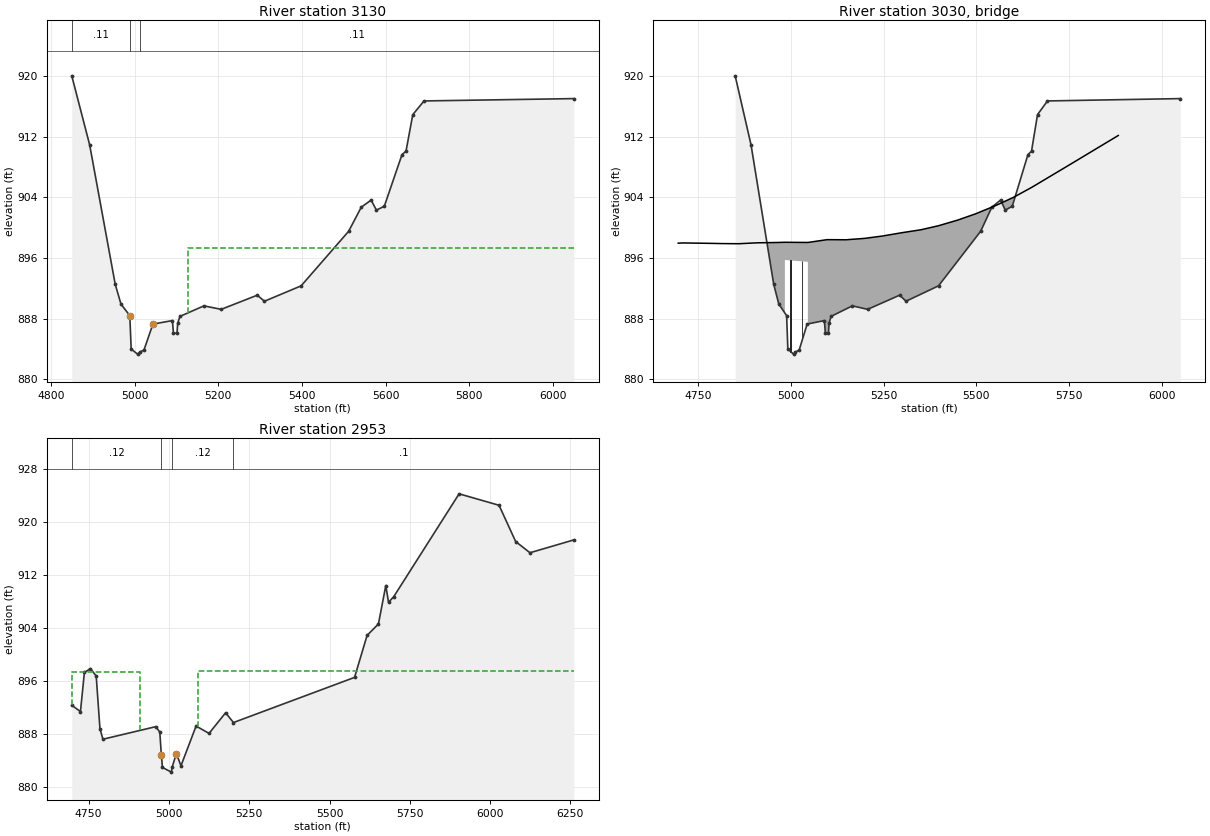
Type RM Length L Ch R = 1 ,3130    ,177.72,177.72,177.72
XS GIS Cut Line= 2
     1471151.004    1107786.8875      1470112.28      1107006.04
#Sta/Elev= 30
    4850     920 4892.77 910.901 4953.83 892.5514967.571 889.936 4988.73 888.409
 4991.96 884.0115007.241 883.342 5012.53 883.6135022.591 883.8855043.971 887.299
 5090.52 887.7615093.081 886.101 5101.49 886.101 5103.24 887.441  5108.6 888.315
 5165.89 889.6995207.181  889.245293.319 891.104 5310.56  890.315398.169 892.336
 5511.77 899.524 5541.98   902.7  5565.5 903.6325578.111 902.3115596.981 902.816
 5639.19 909.6115648.899 910.086 5665.06 914.889 5691.93 916.692    6050     917
#Mann= 3 ,-1,0
    4850     .11       0 4988.73     .04       0 5012.53     .11       0
#XS Ineff= 2 , 0
       0    4902  897.32    5128       0  897.32
Permanent Ineff=
       F       F
Bank Sta=4988.73,5043.971
XS Rating Curve= 0 ,0
Exp/Cntr=0.5,0.3

Type RM Length L Ch R = 3 ,3030    ,,,
BEGIN DESCRIPTION:
Walhalla Hwy (Cannon Creek xing)
Structure ID: LDS_CNC_02
Approximate Survey Structure
END DESCRIPTION:
Bridge Culvert--1,0,-1,-1, 0
Deck Dist Width WeirC Skew NumUp NumDn MinLoCord MaxHiCord MaxSubmerge Is_Ogee
82,36,3,0, 130, 130, , , , 0, 1,1,,
4696.501 4709.82 4734.41 4734.82 4759.164759.8194759.9594759.9714784.1594784.971
  4796.5 4809.02 4809.97 4809.98 4810.754811.709 4835.75 4858.41 4859.58 4883.71
 4884.57  4896.5 4909.034909.561 4909.59 4909.59 4934.274934.579  4959.54959.581
 4960.98 4960.994961.0414965.291    49845046.0015046.0015046.161 5070.98 5071.54
5082.729 5095.985097.0095097.089 5097.985121.7595123.169 5146.715147.191 5148.71
 5172.03 5173.71 5182.73 5195.835197.419 5199.16 5222.42 5224.61 5247.15 5247.16
 5269.535272.1615282.7295294.249 5296.87 5299.55 5321.875324.621 5346.81 5347.83
 5350.755372.819 5375.615382.7315395.589 5398.565420.5895423.399 5445.59 5445.71
 5447.54  5450.25472.549 5475.02 5482.735497.559 5497.79 5498.345521.4615523.331
 5546.87 5548.315548.521 5549.975573.5215574.821 5582.735598.509 5599.435599.561
5623.391 5624.56 5648.37  5649.5 5650.05 5674.02 5675.04 5676.035682.729    5700
5700.3415701.201 5725.335726.209 5750.325750.329 5751.04 5751.955776.0315776.851
 5782.735799.8515799.9215823.911 5824.93 5848.035849.2415873.231 5874.225882.729
 897.956 897.987 897.972 897.973 897.959 897.959 897.959 897.959 897.933 897.932
 897.919 897.905 897.904 897.904 897.903 897.905 897.893 897.882 897.884 897.943
 897.942 897.972 898.003 898.003 898.003 898.003 898.022 898.022 898.041 898.041
 898.042 898.042 898.042 898.049 898.075 898.051 898.051 898.051 898.232 898.234
 898.315 898.411 898.418 898.419 898.422 898.413 898.414 898.405 898.405 898.405
 898.488 898.494 898.526 898.573 898.579 898.589 898.741 898.753   898.9   898.9
  899.09  899.11 899.199 899.297 899.317 899.337 899.501 899.523 899.685 899.693
 899.723 899.971 899.999 900.079 900.224  900.26 900.576  900.61 900.928  900.93
 900.956 901.003 901.385 901.429  901.56 901.814 901.818 901.827  902.29 902.327
 902.798 902.826 902.831 902.864 903.391 903.422 903.599 903.952 903.973 903.976
 904.613 904.643  905.28  905.31 905.325 906.022  906.05 906.076 906.272 906.775
 906.784 906.812 907.518 907.546 908.251 908.251 908.272 908.298 909.008 909.032
 909.205 909.709 909.711  910.42 910.451 911.134  911.17 911.866 911.893  912.14
                                                                                
                                                                                
                                                                                
                                  895.74   895.5
                                                                                
                                                                                
                                                                                
                                                                                
                                                                                
                                                                                
                                                                                
                                                                                
                                                                                
4681.501 4694.82 4719.41 4719.82 4744.164744.8194744.9594744.9714769.1594769.971
  4781.5 4794.02 4794.97 4794.98 4795.754796.709 4820.75 4843.41 4844.58 4868.71
 4869.57  4881.5 4894.034894.561 4894.59 4894.59 4919.274919.579  4944.54944.581
 4945.98 4945.994946.0414950.291    49695031.0015031.0015031.161 5055.98 5056.54
5067.729 5080.985082.0095082.089 5082.985106.7595108.169 5131.715132.191 5133.71
 5157.03 5158.71 5167.73 5180.835182.419 5184.16 5207.42 5209.61 5232.15 5232.16
 5254.535257.1615267.7295279.249 5281.87 5284.55 5306.875309.621 5331.81 5332.83
 5335.755357.819 5360.615367.7315380.589 5383.565405.5895408.399 5430.59 5430.71
 5432.54  5435.25457.549 5460.02 5467.735482.559 5482.79 5483.345506.4615508.331
 5531.87 5533.315533.521 5534.975558.5215559.821 5567.735583.509 5584.435584.561
5608.391 5609.56 5633.37  5634.5 5635.05 5659.02 5660.04 5661.035667.729    5685
5685.3415686.201 5710.335711.209 5735.325735.329 5736.04 5736.955761.0315761.851
 5767.735784.8515784.9215808.911 5809.93 5833.035834.2415858.231 5859.225867.729
 897.956 897.987 897.972 897.973 897.959 897.959 897.959 897.959 897.933 897.932
 897.919 897.905 897.904 897.904 897.903 897.905 897.893 897.882 897.884 897.943
 897.942 897.972 898.003 898.003 898.003 898.003 898.022 898.022 898.041 898.041
 898.042 898.042 898.042 898.049 898.075 898.051 898.051 898.051 898.232 898.234
 898.315 898.411 898.418 898.419 898.422 898.413 898.414 898.405 898.405 898.405
 898.488 898.494 898.526 898.573 898.579 898.589 898.741 898.753   898.9   898.9
  899.09  899.11 899.199 899.297 899.317 899.337 899.501 899.523 899.685 899.693
 899.723 899.971 899.999 900.079 900.224  900.26 900.576  900.61 900.928  900.93
 900.956 901.003 901.385 901.429  901.56 901.814 901.818 901.827  902.29 902.327
 902.798 902.826 902.831 902.864 903.391 903.422 903.599 903.952 903.973 903.976
 904.613 904.643  905.28  905.31 905.325 906.022  906.05 906.076 906.272 906.775
 906.784 906.812 907.518 907.546 908.251 908.251 908.272 908.298 909.008 909.032
 909.205 909.709 909.711  910.42 910.451 911.134  911.17 911.866 911.893  912.14
                                                                                
                                                                                
                                                                                
                                  895.74   895.5
                                                                                
                                                                                
                                                                                
                                                                                
                                                                                
                                                                                
                                                                                
                                                                                
                                                                                
Pier Skew, UpSta & Num, DnSta & Num=  ,4999.5, 2 ,4984.5, 2 , 0 , 0 , 0 ,0,0
       1       1
  884.38   896.3
       1       1
  885.27   896.3
Pier Skew, UpSta & Num, DnSta & Num=  ,5030.5, 2 ,5015.5, 2 , 0 , 0 , 0 ,0,0
       1       1
  885.41   896.3
       1       1
  883.87   896.3
Abutment Skew #Up #Dn= , 2 , 2
    4984    4985
  895.74   887.2
    4969    4970
  895.74  885.49
Abutment Skew #Up #Dn= , 2 , 2
    50455046.001
  885.96   895.5
    50305031.001
  884.68   895.5
BR Coef= 1 , 1 , 0 ,1.25, 0 ,,,0.8,0,2,0,
WSPro=,,,, 1 ,,,, 0 ,,,, 0 ,,,,-1 ,-1 ,-1 , 0 , 0 , 0 , 0 , 0
BC Design=,, 0 ,, 0 ,,,,,,
BC HTab HWMax=921.92
BC Use User HTab Curves=0
BC User HTab FreeFlow(D)= 0

Type RM Length L Ch R = 1 ,2953    ,380,380,380
BEGIN DESCRIPTION:
Cannon Creek 6.0
END DESCRIPTION:
XS GIS Cut Line= 5
      1471290.29      1107836.73      1471319.23      1107718.06
      1471267.13      1107668.86      1470754.83      1107275.22
      1470161.48      1106861.32
#Sta/Elev= 30
  4697.5  892.374724.549  891.424736.799  897.324755.549  897.92 4773.61  896.78
4785.229  888.844794.491  887.244959.149  889.14 4971.61  888.31 4976.51   884.8
 4979.86  882.98 5007.59  882.27 5010.32  883.075023.169  885.065037.519  883.23
 5084.56  889.23 5124.95  888.125176.561  891.24 5200.95  889.76 5578.01  896.58
 5617.08  902.935652.399  904.65 5675.33  910.46 5683.75  907.93 5699.73  908.75
5903.559  924.316027.919  922.58 6079.68   917.16124.209  915.416260.819  917.35
#Mann= 4 ,-1,0
  4697.5     .12       0 4976.51    .045       0 5010.32     .12       0
 5200.95      .1       0
#XS Ineff= 2 , 0
       0    4910  897.35    5090       0  897.61
Permanent Ineff=
       F       F
Bank Sta=4976.51,5023.169
XS Rating Curve= 0 ,0
Exp/Cntr=0.5,0.3

--- Cannon Creek.g02 (geometry) ---

Geom Title=Existing Conditions (Effective)
Program Version=6.10

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
River Reach=Cannon Creek    ,Reach-1
Reach XY= 30
      1470881.43      1108777.89      1470921.55      1108733.76
      1470932.79      1108686.42      1470912.73      1108467.75
      1470919.95      1108338.97       1470860.9      1108079.34
      1470828.07      1107959.77      1470824.43      1107888.39
      1470856.73      1107808.68      1470880.47      1107767.39
      1471094.54      1107668.28       1471160.6      1107612.79
      1471194.96      1107595.61      1471345.59      1107670.93
      1471465.84      1107680.17      1471673.29      1107742.28
      1471781.65      1107851.95      1471915.28      1107918.92
      1471984.94      1107936.16      1472104.17      1107936.16
      1472148.69      1107943.34      1472260.74      1108034.56
      1472319.63      1108092.73      1472425.21      1108145.88
      1472497.03      1108175.33      1472615.01      1108211.83
      1472839.28      1108201.97      1473179.37      1107972.78
      1473515.56      1107564.79      1473692.12      1107523.13