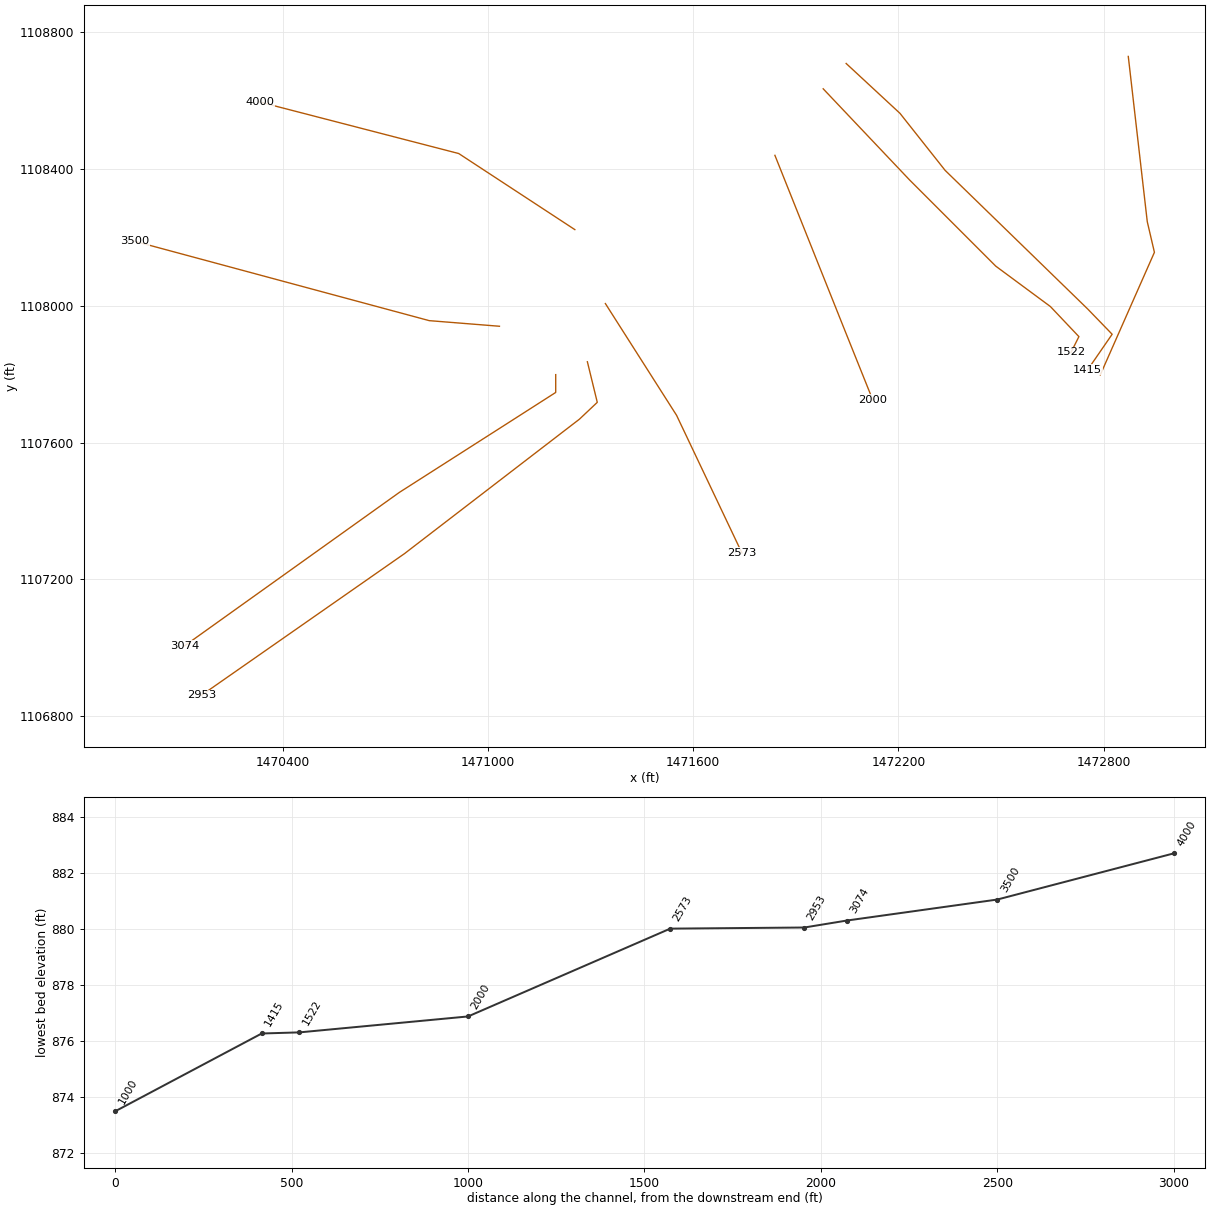
HEC-RAS study Cannon Creek.prj: Cannon Creek Limited Detail Study

--- Cannon Creek.g02 (geometry) --- (continued)

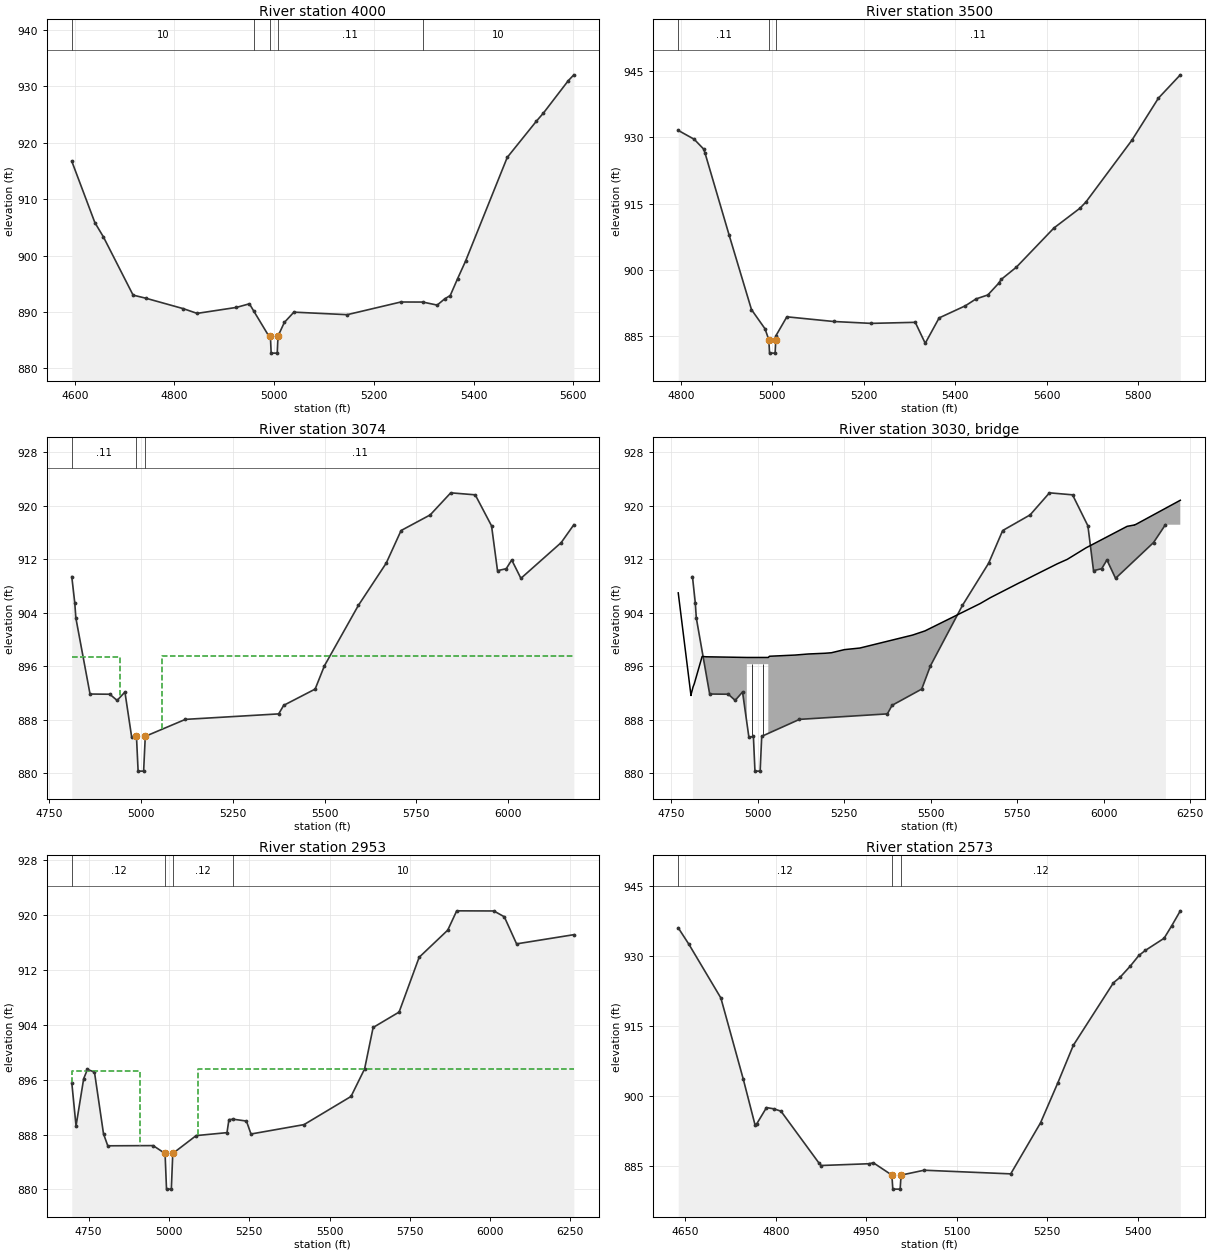
Type RM Length L Ch R = 1 ,4000    ,500,500,500
BEGIN DESCRIPTION:
Cannon Creek 8.0
END DESCRIPTION:
XS GIS Cut Line= 3
      1471253.59      1108223.22      1470913.96      1108445.72
      1470332.14      1108596.32
#Sta/Elev= 30
    4594  916.75  4640.3  905.86  4657.5  903.31    4717  892.99  4742.6  892.44
  4817.6  890.59  4845.4  889.75  4924.2  890.81  4950.3  891.45  4959.3  890.12
  4990.1   885.6  4992.4   885.7  4993.9   882.7  5006.1   882.7  5007.6   885.7
  5020.3  888.14  5039.5  889.97  5146.4  889.52    5254  891.77  5298.1  891.76
  5326.9  891.22  5341.7  892.31  5353.1  892.92  5367.9  895.92  5383.7     899
  5467.4  917.42  5525.9  923.85    5540  925.29  5589.8  931.03    5601  932.07
#Mann= 5 ,-1,0
    4594      10       0  4959.3     .11       0  4992.4     .04       0
  5007.6     .11       0  5298.1      10       0
Bank Sta=4992.4,5007.6
XS Rating Curve= 0 ,0
Exp/Cntr=0.3,0.1

Type RM Length L Ch R = 1 ,3500    ,426,426,426
BEGIN DESCRIPTION:
Cannon Creek 7.0
END DESCRIPTION:
XS GIS Cut Line= 3
      1471033.12      1107940.57      1470827.83      1107956.96
      1469965.78      1108189.21
#Sta/Elev= 30
  4794.1  931.59    4829  929.58  4849.4  927.39  4852.6  926.49  4905.4  907.86
  4954.4  890.92    4984  886.57  4992.4  884.05  4993.9  881.05  5006.1  881.05
  5007.6  884.05  5007.9     885  5031.8  889.29  5133.9  888.23  5216.5   887.8
  5312.8  888.04  5334.6  883.28    5365  889.04  5422.6   891.8  5445.7  893.35
  5471.6  894.25  5495.2  896.89  5500.7  897.76  5533.9  900.54  5616.3  909.45
  5673.3  913.94  5686.3  915.35  5786.9  929.37  5844.9  938.91  5892.8   944.2
#Mann= 3 ,-1,0
  4794.1     .11       0  4992.4     .04       0  5007.6     .11       0
Bank Sta=4992.4,5007.6
XS Rating Curve= 0 ,0
Exp/Cntr=0.5,0.3

Type RM Length L Ch R = 1 ,3074    ,121,121,121
BEGIN DESCRIPTION:
Cannon Creek 6.5
END DESCRIPTION:
XS GIS Cut Line= 5
      1471197.67       1107799.1      1471197.67        1107747.
      1471052.95      1107654.38      1470740.36      1107454.67
      1470112.28      1107006.04
#Sta/Elev= 30
  4811.9  909.39  4820.1  905.45    4823  903.21  4861.6  891.83  4915.5   891.8
  4935.3  890.87  4956.6  892.13  4975.1  885.33    4988   885.5  4992.5   880.3
  5007.5   880.3    5012   885.5  5121.2  888.04  5375.1  888.86  5388.8  890.14
  5474.4  892.57  5499.6  896.05    5592  905.08  5667.8   911.4  5708.3  916.28
  5787.6  918.62  5843.5  921.92  5910.2  921.62  5954.6  916.98  5970.8  910.28
  5994.5  910.57  6009.5  911.88  6034.5  909.13  6144.2  914.48  6178.6  917.15
#Mann= 3 ,-1,0
  4811.9     .11       0    4988    .045       0    5012     .11       0
#XS Ineff= 2 , 0
       0    4943  897.32    5057       0  897.53
Permanent Ineff=
       F       F
Bank Sta=4988,5012
XS Rating Curve= 0 ,0
Exp/Cntr=0.5,0.3

Type RM Length L Ch R = 3 ,3030    ,,,
BEGIN DESCRIPTION:
Walhalla Hwy (Cannon Creek xing)
Structure ID: LDS_CNC_02
Approximate Survey Structure
END DESCRIPTION:
Bridge Culvert--1,0,-1,-1, 0
Deck Dist Width WeirC Skew NumUp NumDn MinLoCord MaxHiCord MaxSubmerge Is_Ogee
26,36,3,0, 36, 36, , , , 0, 1,1,,
  4770.8  4780.9  4807.6  4808.1  4813.6  4817.2  4839.8  4851.9    4969    4969
    5031    5031  5034.4  5108.7    5147  5195.3  5212.2  5213.9  5250.8  5295.7
    5448  5483.7  5643.3  5672.7  5757.8  5766.3  5798.4  5866.3  5894.9  5949.4
  6067.9  6087.9  6088.5  6088.9  6095.3  6221.6
  906.96  902.74  891.61  891.78  892.89  893.37  897.45   897.4   897.3   897.3
   897.3   897.3  897.48  897.66  897.82  897.93     898  898.01  898.47  898.71
  900.65  901.27  905.36  906.24   908.5   908.7  909.55  911.31  911.97   913.7
  916.91   917.1  917.08   917.1  917.26  920.81
   860.3   860.3   860.3   860.3   860.3   860.3   860.3   860.3   860.3   896.3
   896.3   860.3   860.3   860.3   860.3   860.3   860.3   860.3   860.3   860.3
   860.3   860.3   860.3   860.3   860.3   860.3   860.3   860.3   860.3   860.3
   860.3   860.3   860.3   860.3   860.3   860.3
  4770.8  4780.9  4807.6  4808.1  4813.6  4817.2  4839.8  4851.9    4969    4969
    5031    5031  5034.4  5108.7    5147  5195.3  5212.2  5213.9  5250.8  5295.7
    5448  5483.7  5643.3  5672.7  5757.8  5766.3  5798.4  5866.3  5894.9  5949.4
  6067.9  6087.9  6088.5  6088.9  6095.3  6221.6
  906.96  902.74  891.61  891.78  892.89  893.37  897.45   897.4   897.3   897.3
   897.3   897.3  897.48  897.66  897.82  897.93     898  898.01  898.47  898.71
  900.65  901.27  905.36  906.24   908.5   908.7  909.55  911.31  911.97   913.7
  916.91   917.1  917.08   917.1  917.26  920.81
   860.3   860.3   860.3   860.3   860.3   860.3   860.3   860.3   860.3   896.3
   896.3   860.3   860.3   860.3   860.3   860.3   860.3   860.3   860.3   860.3
   860.3   860.3   860.3   860.3   860.3   860.3   860.3   860.3   860.3   860.3
   860.3   860.3   860.3   860.3   860.3   860.3
Pier Skew, UpSta & Num, DnSta & Num=  ,4984.5, 2 ,4984.5, 2 , 0 , 0 , 0 ,0,0
       1       1
  884.38   896.3
       1       1
  885.27   896.3
Pier Skew, UpSta & Num, DnSta & Num=  ,5015.5, 2 ,5015.5, 2 , 0 , 0 , 0 ,0,0
       1       1
  885.41   896.3
       1       1
  883.87   896.3
Abutment Skew #Up #Dn= , 2 , 2
    4969    4970
   896.3   887.2
    4969    4970
   896.3  885.49
Abutment Skew #Up #Dn= , 2 , 2
    5030    5031
  885.96   896.3
    5030    5031
  884.68   896.3
BR Coef= 1 , 1 , 0 ,1.25, 0 ,,,0.8,0,2,0,
WSPro=,,,, 1 ,,,, 0 ,,,, 0 ,,,,-1 ,-1 ,-1 , 0 , 0 , 0 , 0 , 0
BC Design=,, 0 ,, 0 ,,,,,,
BC HTab HWMax=921.92
BC Use User HTab Curves=0
BC User HTab FreeFlow(D)= 0

Type RM Length L Ch R = 1 ,2953    ,380,380,380
BEGIN DESCRIPTION:
Cannon Creek 6.0
END DESCRIPTION:
XS GIS Cut Line= 5
      1471290.29      1107836.73      1471319.23      1107718.06
      1471267.13      1107668.86      1470754.83      1107275.22
      1470161.48      1106861.32
#Sta/Elev= 30
  4697.5   895.6  4710.8  889.27  4734.6  896.17  4746.3  897.51  4768.2  897.13
  4796.3  888.13  4809.6  886.37  4950.8   886.4    4988  885.25  4992.5  880.05
  5007.5  880.05    5012  885.25  5084.8  887.86  5180.8  888.29  5186.9  890.19
  5200.1  890.25  5241.4  889.98  5255.5  888.09  5420.6  889.46    5567  893.57
  5609.3  897.59  5635.8  903.63  5716.7  905.88  5779.1  913.87  5868.1  917.83
  5896.1  920.65  6011.8  920.63  6044.3  919.78  6082.5  915.83  6260.8  917.17
#Mann= 4 ,-1,0
  4697.5     .12       0    4988    .045       0    5012     .12       0
  5200.1      10       0
#XS Ineff= 2 , 0
       0    4910  897.35    5090       0  897.61
Permanent Ineff=
       F       F
Bank Sta=4988,5012
XS Rating Curve= 0 ,0
Exp/Cntr=0.5,0.3

Type RM Length L Ch R = 1 ,2573    ,573,573,573
BEGIN DESCRIPTION:
Cannon Creek 5.0
END DESCRIPTION:
XS GIS Cut Line= 3
      1471342.91      1108006.94      1471551.21      1107680.02
      1471742.16      1107277.88
#Sta/Elev= 30
    4638  935.99  4655.7  932.46  4708.7  920.96  4745.9  903.56  4765.5  893.72
  4768.4  894.04  4784.4  897.48  4796.6  897.21  4808.4  896.71  4870.8  885.71
    4875  885.07  4954.4  885.45  4961.7  885.65  4992.4  883.01  4993.9  880.01
  5006.1  880.01  5007.6  883.01  5045.8  884.06  5189.5  883.28  5238.9   894.2
  5267.5  902.74  5293.3  910.81  5359.9  924.22  5371.1  925.42    5388  927.82
  5402.1  930.07  5412.9  931.16  5443.9  933.75  5456.7  936.46  5470.8  939.63
#Mann= 3 ,-1,0
    4638     .12       0  4992.4    .045       0  5007.6     .12       0
Bank Sta=4992.4,5007.6
XS Rating Curve= 0 ,0
Exp/Cntr=0.3,0.1

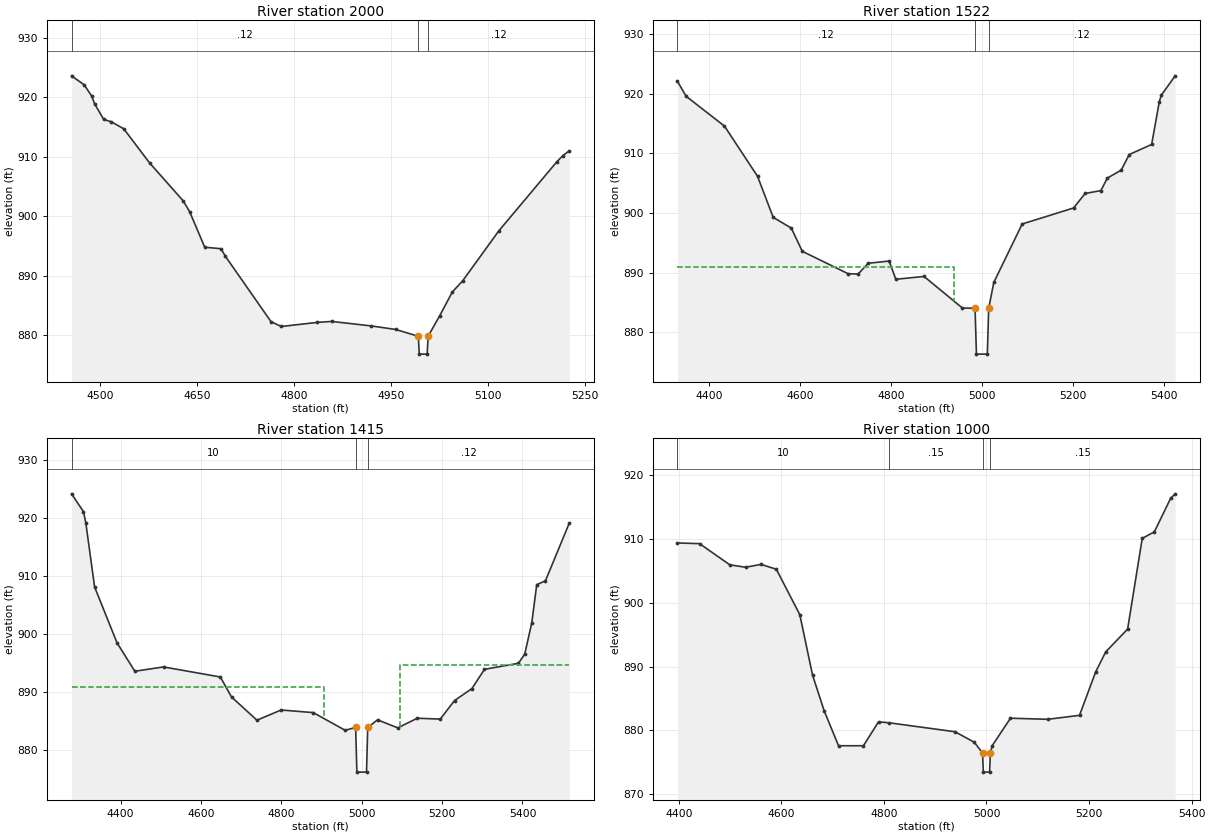
Type RM Length L Ch R = 1 ,2000    ,478,478,478
BEGIN DESCRIPTION:
Cannon Creek 4.0
END DESCRIPTION:
XS GIS Cut Line= 3
      1471838.77       1108440.5      1472040.76      1107934.83
        1472125.        1107725.
#Sta/Elev= 30
  4455.5   923.6    4475  922.09  4486.7  920.21  4491.3  918.88  4505.3  916.28
  4516.8  915.89  4536.3  914.71  4576.3  908.98  4628.4   902.6  4638.3   900.8
  4661.7  894.82  4686.9  894.57  4693.8  893.28  4764.3  882.33  4780.1  881.51
  4836.3   882.2  4858.3  882.36  4919.2  881.61  4957.4  881.01  4992.4  879.87
  4993.9  876.87  5006.1  876.87  5007.6  879.87  5025.4  883.29  5045.1  887.31
  5061.3  889.21    5117  897.56  5207.1   909.2  5216.3   910.2  5226.1  911.01
#Mann= 3 ,-1,0
  4455.5     .12       0  4992.4    .045       0  5007.6     .12       0
Bank Sta=4992.4,5007.6
XS Rating Curve= 0 ,0
Exp/Cntr=0.5,0.3

Type RM Length L Ch R = 1 ,1522    ,107,107,107
BEGIN DESCRIPTION:
Cannon Creek 3.5
END DESCRIPTION:
XS GIS Cut Line= 6
      1471980.02        1108635.      1472232.41      1108368.72
       1472484.8      1108116.33      1472644.57      1107998.24
      1472727.93      1107910.25      1472704.77      1107863.94
#Sta/Elev= 30
  4329.9  922.09  4348.8  919.59  4433.4  914.57  4506.2  906.14  4540.6  899.26
  4580.5  897.45  4604.6  893.56  4705.5   889.8  4727.6  889.74  4749.6  891.55
  4795.8  891.92  4810.6  888.86  4872.7  889.34    4957  884.04    4985     884
    4988   876.3    5012   876.3    5015     884  5026.3  888.34  5088.7  898.14
  5201.9  900.83  5227.2  903.26    5262  903.75  5276.2  905.85  5306.7  907.18
  5324.4   909.8  5373.7  911.49  5390.6  918.68  5394.9  919.75  5425.5  923.01
#Mann= 3 ,-1,0
  4329.9     .12       0    4985     .05       0    5015     .12       0
#XS Ineff= 2 , 0
       0    4938  890.84    5062       0  892.46
Permanent Ineff=
       F       F
Bank Sta=4985,5015
XS Rating Curve= 0 ,0
Exp/Cntr=0.5,0.3

Type RM Length L Ch R = 1 ,1415    ,415,415,415
BEGIN DESCRIPTION:
Cannon Creek 3.0
END DESCRIPTION:
XS GIS Cut Line= 6
      1472047.17       1108709.1      1472204.62      1108563.22
      1472336.61       1108396.5       1472753.4      1107991.29
      1472825.18      1107917.19       1472753.4        1107813.
#Sta/Elev= 30
  4278.1  924.23  4307.7  921.16  4313.6  919.22  4335.5  908.16  4391.3  898.54
  4435.6  893.65  4507.1  894.39  4648.3  892.66  4676.1  889.22  4739.3  885.21
  4799.6  886.97  4879.5  886.52  4958.9  883.47    4985  883.96    4988  876.26
    5012  876.26    5015  883.96  5039.4  885.27  5089.9  883.89  5138.2  885.55
  5195.4   885.4    5231   888.6  5274.2  890.66  5305.5  893.98  5389.9  895.02
  5405.6  896.59  5423.2     902  5435.5  908.57  5457.2  909.24  5516.4  919.17
#Mann= 3 ,-1,0
  4278.1      10       0    4985     .05       0    5015     .12       0
#XS Ineff= 2 , 0
       0    4905  890.88    5095       0   894.8
Permanent Ineff=
       F       F
Bank Sta=4985,5015
XS Rating Curve= 0 ,0
Exp/Cntr=0.5,0.3

Type RM Length L Ch R = 1 ,1000    ,500,500,500
BEGIN DESCRIPTION:
Cannon Creek 2.0
END DESCRIPTION:
XS GIS Cut Line= 4
      1472872.36       1108729.7      1472927.91      1108246.36
      1472948.82      1108156.77      1472790.55      1107798.44
#Sta/Elev= 30
  4397.6  909.36  4440.7  909.25  4499.7  905.93  4530.3  905.56  4560.8     906
  4590.4  905.24  4636.1  898.13  4660.9  888.68  4683.5   883.1  4711.6  877.61
  4760.1  877.61  4789.6  881.35  4810.5   881.2  4938.8   879.8  4976.2  878.16
  4992.4  876.48  4993.9  873.48  5006.1  873.48  5007.6  876.48  5011.1  877.61
  5046.8  881.92  5119.6  881.75  5181.4  882.37  5212.9  889.17  5232.5  892.31
  5275.2  895.87  5303.7  910.07  5327.3   911.1  5359.1  916.35  5367.9  917.05
#Mann= 4 ,-1,0
  4397.6      10       0  4810.5     .15       0  4992.4     .05       0
  5007.6     .15       0
Bank Sta=4992.4,5007.6
XS Rating Curve= 0 ,0
Exp/Cntr=0.3,0.1
LCMann Table=0

--- Cannon Creek.g07 (geometry) ---

Geom Title=Revised - 150'
Program Version=6.10

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
River Reach=Cannon Creek    ,Reach-1