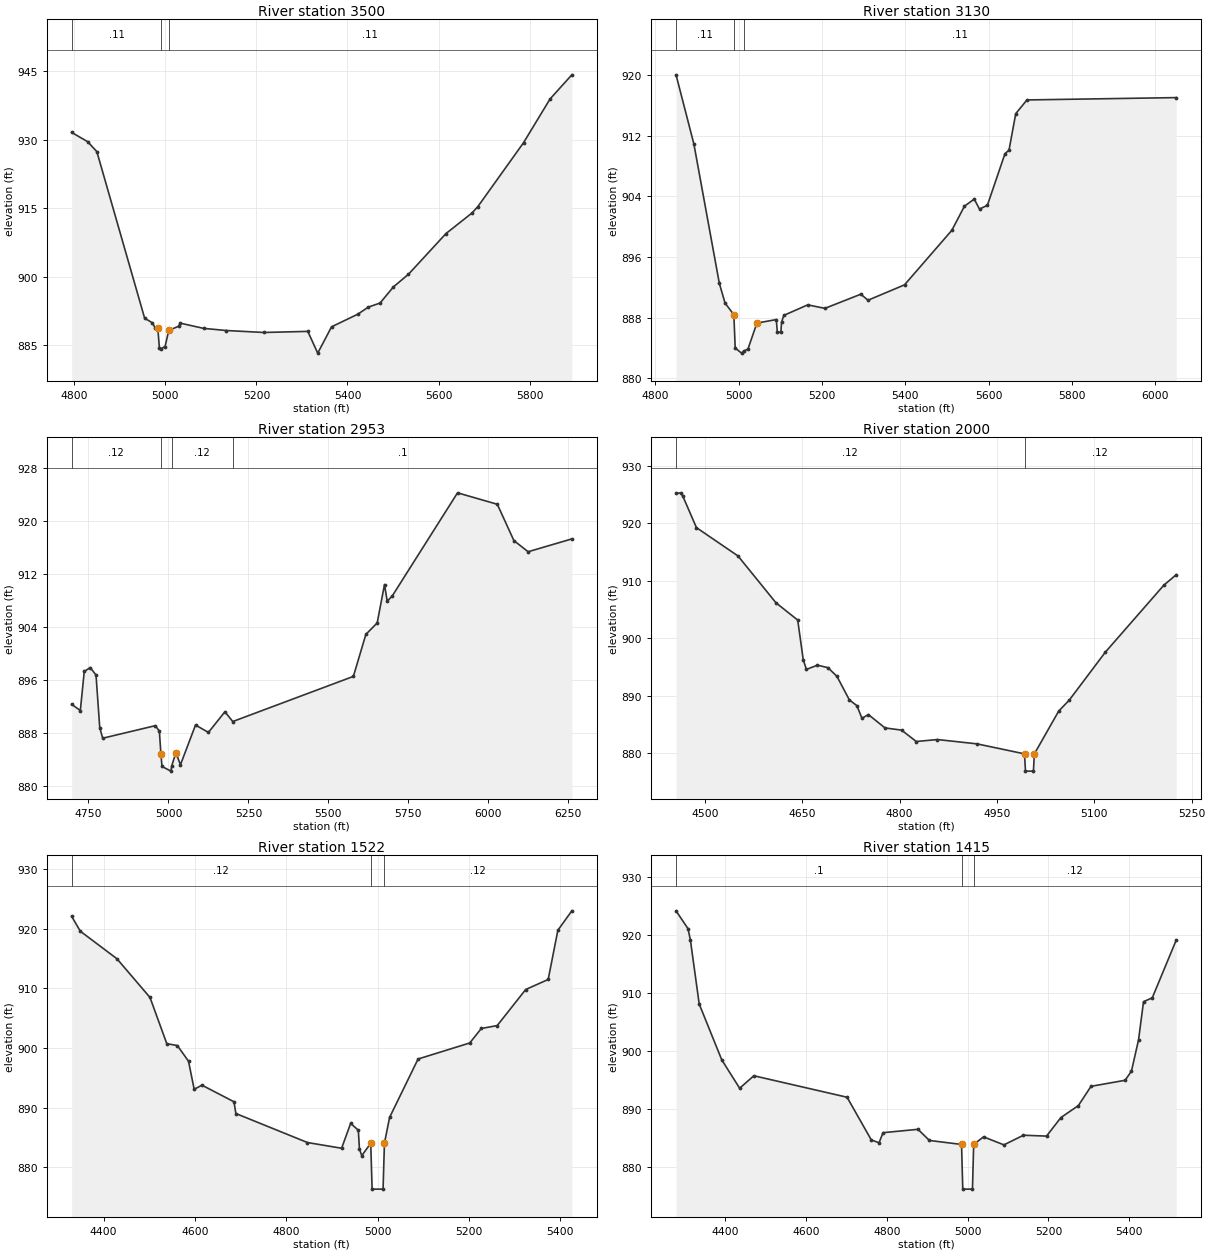
HEC-RAS study Cannon Creek.prj: Cannon Creek Limited Detail Study

--- Cannon Creek.g07 (geometry) --- (continued)

Type RM Length L Ch R = 3 ,3030    ,,,
BEGIN DESCRIPTION:
Walhalla Hwy (Cannon Creek xing)
Structure ID: LDS_CNC_02
Approximate Survey Structure
END DESCRIPTION:
Bridge Culvert--1,0,-1,-1, 0
Deck Dist Width WeirC Skew NumUp NumDn MinLoCord MaxHiCord MaxSubmerge Is_Ogee
33,46.25,3,0, 121, 121, , , , 0, 1,1,,
  4681.5 4694.82 4719.41 4719.82 4744.16 4744.82 4744.96 4744.97 4769.16 4769.97
  4781.5 4794.02 4794.97 4794.98 4795.75 4796.71 4820.75 4843.41 4844.58 4868.71
 4869.57  4881.5 4894.03 4894.56 4894.59 4894.59 4919.27 4919.58  4944.5 4944.58
 4945.98 4945.99 4946.04 4950.29    4965    4965    5115    5115 5131.71 5132.19
 5133.71 5157.03 5158.71 5167.73 5180.83 5182.42 5184.16 5207.42 5209.61 5232.15
 5232.16 5254.53 5257.16 5267.73 5279.25 5281.87 5284.55 5306.87 5309.62 5331.81
 5332.83 5335.75 5357.82 5360.61 5367.73 5380.59 5383.56 5405.59  5408.4 5430.59
 5430.71 5432.54  5435.2 5457.55 5460.02 5467.73 5482.56 5482.79 5483.34 5506.46
 5508.33 5531.87 5533.31 5533.52 5534.97 5558.52 5559.82 5567.73 5583.51 5584.43
 5584.56 5608.39 5609.56 5633.37  5634.5 5635.05 5659.02 5660.04 5661.03 5667.73
    5685 5685.34  5686.2 5710.33 5711.21 5735.32 5735.33 5736.04 5736.95 5761.03
 5761.85 5767.73 5784.85 5784.92 5808.91 5809.93 5833.03 5834.24 5858.23 5859.22
5867.729
 897.956 897.987 897.972 897.973 897.959 897.959 897.959 897.959 897.933 897.932
 897.919 897.905 897.904 897.904 897.903 897.905 897.893 897.882 897.884 897.943
 897.942 897.972 898.003 898.003 898.003 898.003 898.022 898.022 898.041 898.041
 898.042 898.042 898.042 898.049 898.075 898.075 898.051 898.051 898.405 898.405
 898.405 898.488 898.494 898.526 898.573 898.579 898.589 898.741 898.753   898.9
   898.9  899.09  899.11 899.199 899.297 899.317 899.337 899.501 899.523 899.685
 899.693 899.723 899.971 899.999 900.079 900.224  900.26 900.576  900.61 900.928
  900.93 900.956 901.003 901.385 901.429  901.56 901.814 901.818 901.827  902.29
 902.327 902.798 902.826 902.831 902.864 903.391 903.422 903.599 903.952 903.973
 903.976 904.613 904.643  905.28  905.31 905.325 906.022  906.05 906.076 906.272
 906.775 906.784 906.812 907.518 907.546 908.251 908.251 908.272 908.298 909.008
 909.032 909.205 909.709 909.711  910.42 910.451 911.134  911.17 911.866 911.893
  912.14
                                                                                
                                                                                
                                                                                
                                          895.74   895.5
                                                                                
                                                                                
                                                                                
                                                                                
                                                                                
                                                                                
                                                                                
                                                                                
        
  4681.5 4694.82 4719.41 4719.82 4744.16 4744.82 4744.96 4744.97 4769.16 4769.97
  4781.5 4794.02 4794.97 4794.98 4795.75 4796.71 4820.75 4843.41 4844.58 4868.71
 4869.57  4881.5 4894.03 4894.56 4894.59 4894.59 4919.27 4919.58  4944.5 4944.58
 4945.98 4945.99 4946.04 4950.29    4965    4965    5115    5115 5131.71 5132.19
 5133.71 5157.03 5158.71 5167.73 5180.83 5182.42 5184.16 5207.42 5209.61 5232.15
 5232.16 5254.53 5257.16 5267.73 5279.25 5281.87 5284.55 5306.87 5309.62 5331.81
 5332.83 5335.75 5357.82 5360.61 5367.73 5380.59 5383.56 5405.59  5408.4 5430.59
 5430.71 5432.54  5435.2 5457.55 5460.02 5467.73 5482.56 5482.79 5483.34 5506.46
 5508.33 5531.87 5533.31 5533.52 5534.97 5558.52 5559.82 5567.73 5583.51 5584.43
 5584.56 5608.39 5609.56 5633.37  5634.5 5635.05 5659.02 5660.04 5661.03 5667.73
    5685 5685.34  5686.2 5710.33 5711.21 5735.32 5735.33 5736.04 5736.95 5761.03
 5761.85 5767.73 5784.85 5784.92 5808.91 5809.93 5833.03 5834.24 5858.23 5859.22
5867.729
 897.956 897.987 897.972 897.973 897.959 897.959 897.959 897.959 897.933 897.932
 897.919 897.905 897.904 897.904 897.903 897.905 897.893 897.882 897.884 897.943
 897.942 897.972 898.003 898.003 898.003 898.003 898.022 898.022 898.041 898.041
 898.042 898.042 898.042 898.049 898.075 898.075 898.051 898.051 898.405 898.405
 898.405 898.488 898.494 898.526 898.573 898.579 898.589 898.741 898.753   898.9
   898.9  899.09  899.11 899.199 899.297 899.317 899.337 899.501 899.523 899.685
 899.693 899.723 899.971 899.999 900.079 900.224  900.26 900.576  900.61 900.928
  900.93 900.956 901.003 901.385 901.429  901.56 901.814 901.818 901.827  902.29
 902.327 902.798 902.826 902.831 902.864 903.391 903.422 903.599 903.952 903.973
 903.976 904.613 904.643  905.28  905.31 905.325 906.022  906.05 906.076 906.272
 906.775 906.784 906.812 907.518 907.546 908.251 908.251 908.272 908.298 909.008
 909.032 909.205 909.709 909.711  910.42 910.451 911.134  911.17 911.866 911.893
  912.14
                                                                                
                                                                                
                                                                                
                                          895.74   895.5
                                                                                
                                                                                
                                                                                
                                                                                
                                                                                
                                                                                
                                                                                
                                                                                
        
Pier Skew, UpSta & Num, DnSta & Num=  ,5055, 2 ,5055, 2 , 0 , 0 , 0 ,,
       4       4
     880   895.5
       4       4
     880   895.5
Abutment Skew #Up #Dn= , 3 , 3
    4965    4967    4980
   893.5   893.5   885.5
    4965    4967    4980
   893.5   893.5   885.5
Abutment Skew #Up #Dn= , 3 , 3
    5101    5113    5115
   883.5   893.5   893.5
    5101    5113    5115
   883.5   893.5   893.5
BR Coef= 1 , 1 , 0 ,1.25, 0 ,,,0.8,0,2,0,
WSPro=,,,, 1 ,,,, 0 ,,,, 0 ,,,,-1 ,-1 ,-1 , 0 , 0 , 0 , 0 , 0
BC Design=,, 0 ,, 0 ,,,,,,
BC HTab HWMax=921.92
BC Use User HTab Curves=0
BC User HTab FreeFlow(D)= 0

--- Cannon Creek.g09 (geometry) ---

Geom Title=Unrestricted Conditions
Program Version=6.10

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
River Reach=Cannon Creek    ,Reach-1

Type RM Length L Ch R = 1 ,3500    ,426,426,426
BEGIN DESCRIPTION:
Cannon Creek 7.0
END DESCRIPTION:
XS GIS Cut Line= 3
      1471033.12      1107940.57      1470827.83      1107956.96
      1469965.78      1108189.21
#Sta/Elev= 30
  4794.1  931.59    4829  929.58  4849.4  927.39  4954.4  890.92 4971.47 889.916
 4977.07 888.871 4983.23  888.88 4986.73 884.481 4991.27 884.289 4999.25 884.727
 5007.37 888.244 5029.01 889.167 5032.55 889.846  5083.8   888.7  5133.9  888.23
  5216.5   887.8  5312.8  888.04  5334.6  883.28    5365  889.04  5422.6   891.8
  5445.7  893.35  5471.6  894.25  5500.7  897.76  5533.9  900.54  5616.3  909.45
  5673.3  913.94  5686.3  915.35  5786.9  929.37  5844.9  938.91  5892.8   944.2
#Mann= 3 ,-1,0
  4794.1     .11       0 4991.27     .04       0 5007.37     .11       0
Bank Sta=4983.23,5007.37
XS Rating Curve= 0 ,0
Exp/Cntr=0.3,0.1

Type RM Length L Ch R = 1 ,3130    ,177.72,177.72,177.72
XS GIS Cut Line= 2
     1471151.004    1107786.8875      1470112.28      1107006.04
#Sta/Elev= 30
    4850     920 4892.77 910.901 4953.83 892.551 4967.57 889.936 4988.73 888.409
 4991.96 884.011 5007.24 883.342 5012.53 883.613 5022.59 883.885 5043.97 887.299
 5090.52 887.761 5093.08 886.101 5101.49 886.101 5103.24 887.441  5108.6 888.315
 5165.89 889.699 5207.18  889.24 5293.32 891.104 5310.56  890.31 5398.17 892.336
 5511.77 899.524 5541.98   902.7  5565.5 903.632 5578.11 902.311 5596.98 902.816
 5639.19 909.611  5648.9 910.086 5665.06 914.889 5691.93 916.692    6050     917
#Mann= 3 ,-1,0
    4850     .11       0 4988.73     .04       0 5012.53     .11       0
#XS Ineff= 2 , 0
Permanent Ineff=
       F       F
Bank Sta=4988.73,5043.97
XS Rating Curve= 0 ,0
Exp/Cntr=0.3,0.1

Type RM Length L Ch R = 1 ,2953    ,380,380,380
BEGIN DESCRIPTION:
Cannon Creek 6.0
END DESCRIPTION:
XS GIS Cut Line= 5
      1471290.29      1107836.73      1471319.23      1107718.06
      1471267.13      1107668.86      1470754.83      1107275.22
      1470161.48      1106861.32
#Sta/Elev= 30
  4697.5  892.37 4724.55  891.42  4736.8  897.32 4755.55  897.92 4773.61  896.78
 4785.23  888.84 4794.49  887.24 4959.15  889.14 4971.61  888.31 4976.51   884.8
 4979.86  882.98 5007.59  882.27 5010.32  883.07 5023.17  885.06 5037.52  883.23
 5084.56  889.23 5124.95  888.12 5176.56  891.24 5200.95  889.76 5578.01  896.58
 5617.08  902.93  5652.4  904.65 5675.33  910.46 5683.75  907.93 5699.73  908.75
 5903.56  924.31 6027.92  922.58 6079.68   917.1 6124.21  915.41 6260.82  917.35
#Mann= 4 ,-1,0
  4697.5     .12       0 4976.51    .045       0 5010.32     .12       0
 5200.95      .1       0
#XS Ineff= 2 , 0
Permanent Ineff=
       F       F
Bank Sta=4976.51,5023.17
XS Rating Curve= 0 ,0
Exp/Cntr=0.3,0.1

Type RM Length L Ch R = 1 ,2000    ,478,478,478
BEGIN DESCRIPTION:
Cannon Creek 4.0
END DESCRIPTION:
XS GIS Cut Line= 3
      1471838.77       1108440.5      1472040.76      1107934.83
        1472125.        1107725.
#Sta/Elev= 30
  4455.5  925.14  4462.9  925.25 4465.65  924.75 4486.94   919.2 4550.93  914.28
 4609.49  906.13 4642.97  903.13 4651.47  896.26 4656.34  894.55 4673.44  895.29
 4689.64  894.85 4703.43  893.34 4722.55  889.25  4734.1  888.25 4741.94  886.06
 4751.84   886.7 4777.47  884.38 4802.99     884  4825.6  882.02  4858.3  882.36
  4919.2  881.61  4992.4  879.87  4993.9  876.87  5006.1  876.87  5007.6  879.87
  5045.1  887.31  5061.3  889.21    5117  897.56  5207.1   909.2  5226.1  911.01
#Mann= 2 ,-1,0
  4455.5     .12       0  4992.4     .12       0
Bank Sta=4992.4,5007.6
XS Rating Curve= 0 ,0
Exp/Cntr=0.3,0.1

Type RM Length L Ch R = 1 ,1522    ,107,107,107
BEGIN DESCRIPTION:
Cannon Creek 3.5
END DESCRIPTION:
XS GIS Cut Line= 6
      1471980.02        1108635.      1472232.41      1108368.72
       1472484.8      1108116.33      1472644.57      1107998.24
      1472727.93      1107910.25      1472704.77      1107863.94
#Sta/Elev= 30
  4329.9  922.09  4348.8  919.59    4429  914.97 4501.44  908.47 4538.31  900.71
 4561.34   900.4 4585.82  897.77 4598.25  893.06 4615.28  893.75 4685.47  890.96
 4689.56  888.99  4846.4  884.12 4921.19  883.16 4940.99  887.33 4957.81  886.19
 4960.24  883.07 4965.28  881.91    4985     884    4988   876.3    5012   876.3
    5015     884  5026.3  888.34  5088.7  898.14  5201.9  900.83  5227.2  903.26
    5262  903.75  5324.4   909.8  5373.7  911.49  5394.9  919.75  5425.5  923.01
#Mann= 3 ,-1,0
  4329.9     .12       0    4985     .05       0    5015     .12       0
#XS Ineff= 2 , 0
Permanent Ineff=
       F       F
Bank Sta=4985,5015
XS Rating Curve= 0 ,0
Exp/Cntr=0.3,0.1

Type RM Length L Ch R = 1 ,1415    ,415,415,415
BEGIN DESCRIPTION:
Cannon Creek 3.0
END DESCRIPTION:
XS GIS Cut Line= 6
      1472047.17       1108709.1      1472204.62      1108563.22
      1472336.61       1108396.5       1472753.4      1107991.29
      1472825.18      1107917.19       1472753.4        1107813.
#Sta/Elev= 30
  4278.1  924.23  4307.7  921.16  4313.6  919.22  4335.5  908.16  4391.3  898.54
  4435.6  893.65 4470.77   895.8 4701.56   892.1 4761.53  884.74 4780.75  884.25
 4790.59  885.99 4877.08  886.57 4905.45  884.65    4985  883.96    4988  876.26
    5012  876.26    5015  883.96  5039.4  885.27  5089.9  883.89  5138.2  885.55
  5195.4   885.4    5231   888.6  5274.2  890.66  5305.5  893.98  5389.9  895.02
  5405.6  896.59  5423.2     902  5435.5  908.57  5457.2  909.24  5516.4  919.17
#Mann= 3 ,-1,0
  4278.1      .1       0    4985     .05       0    5015     .12       0
#XS Ineff= 2 , 0
Permanent Ineff=
       F       F
Bank Sta=4985,5015
XS Rating Curve= 0 ,0
Exp/Cntr=0.3,0.1

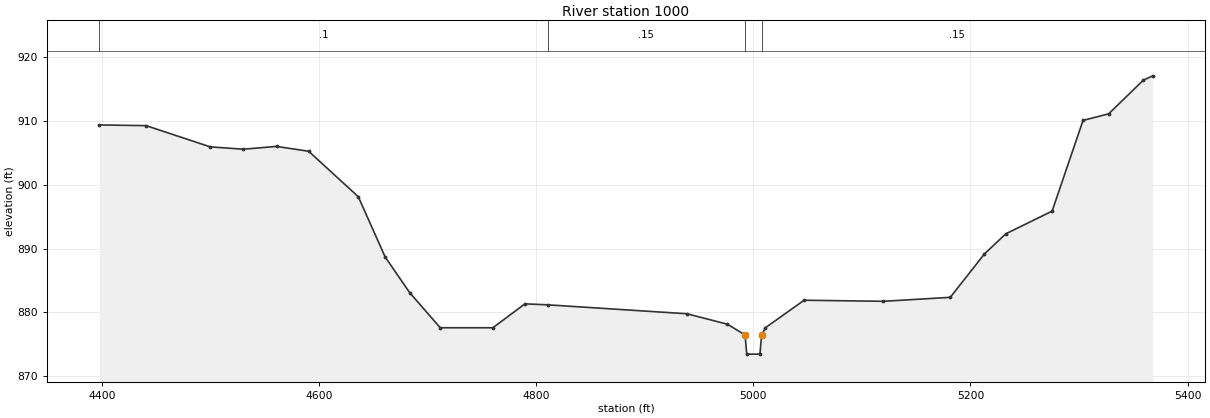
Type RM Length L Ch R = 1 ,1000    ,406,406,406
BEGIN DESCRIPTION:
Cannon Creek 2.0
END DESCRIPTION:
XS GIS Cut Line= 4
      1472872.36       1108729.7      1472927.91      1108246.36
      1472948.82      1108156.77      1472790.55      1107798.44
#Sta/Elev= 30
  4397.6  909.36  4440.7  909.25  4499.7  905.93  4530.3  905.56  4560.8     906
  4590.4  905.24  4636.1  898.13  4660.9  888.68  4683.5   883.1  4711.6  877.61
  4760.1  877.61  4789.6  881.35  4810.5   881.2  4938.8   879.8  4976.2  878.16
  4992.4  876.48  4993.9  873.48  5006.1  873.48  5007.6  876.48  5011.1  877.61
  5046.8  881.92  5119.6  881.75  5181.4  882.37  5212.9  889.17  5232.5  892.31
  5275.2  895.87  5303.7  910.07  5327.3   911.1  5359.1  916.35  5367.9  917.05
#Mann= 4 ,-1,0
  4397.6      .1       0  4810.5     .15       0  4992.4     .05       0
  5007.6     .15       0
Bank Sta=4992.4,5007.6
XS Rating Curve= 0 ,0
Exp/Cntr=0.3,0.1