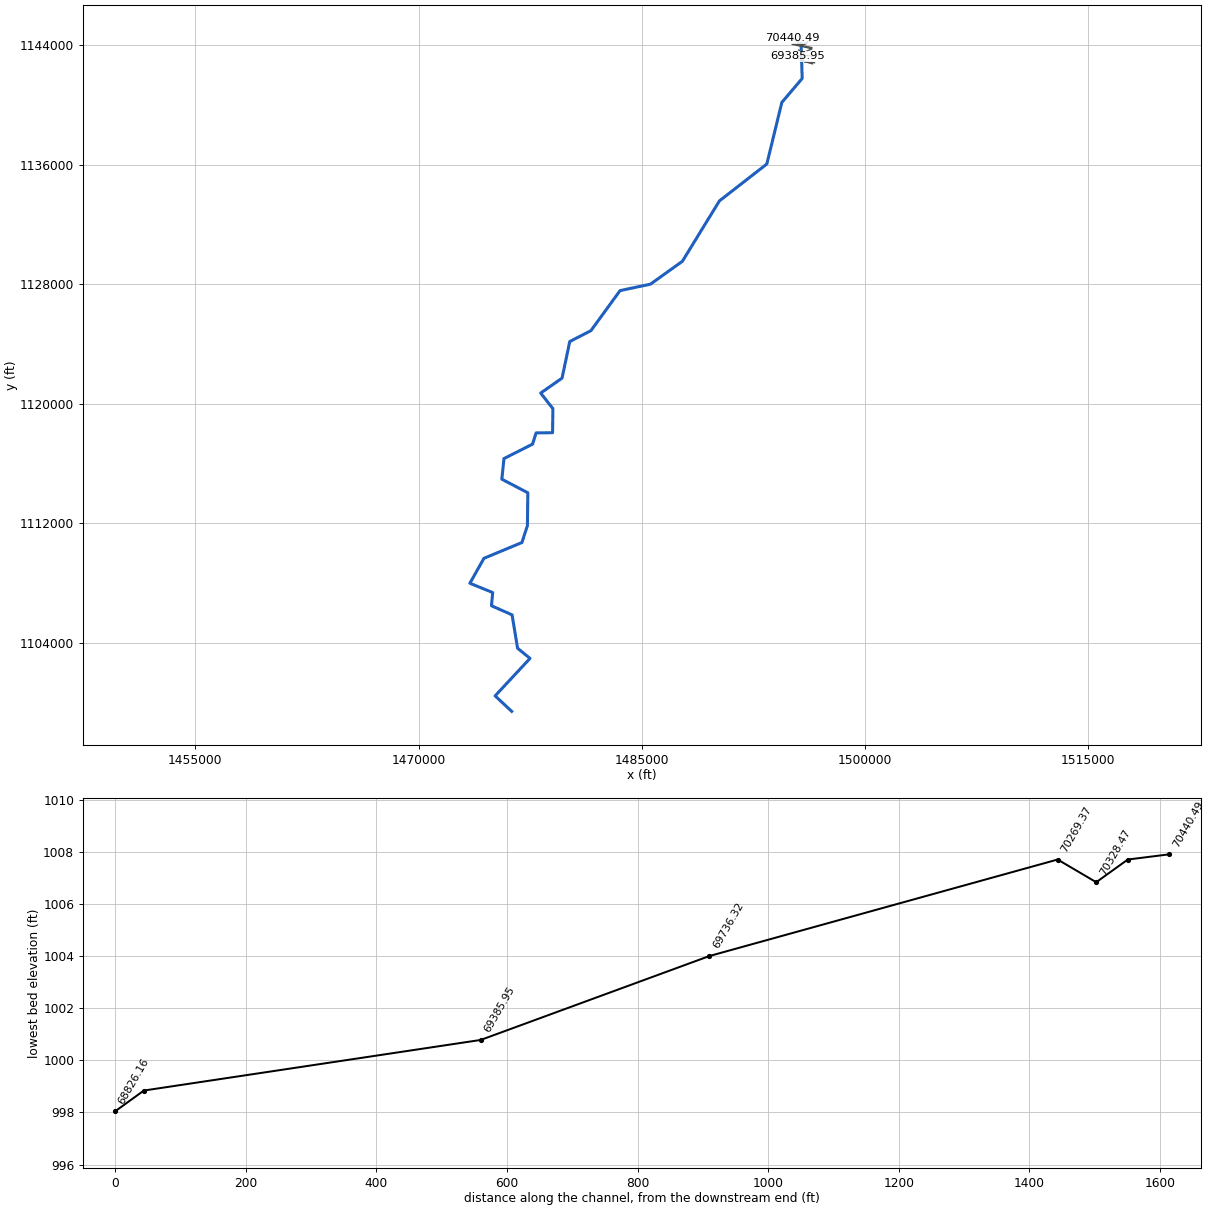
--- 12mile_Combined.prj (project) ---

Proj Title=12mile Creek Combined Model
Current Plan=p04
Default Exp/Contr=0.3,0.1
English Units
Geom File=g01
Geom File=g05
Geom File=g03
Geom File=g07
Flow File=f01
Flow File=f02
Plan File=p01
Plan File=p02
Plan File=p07
Plan File=p03
Plan File=p05
Plan File=p06
Plan File=p04
Y Axis Title=Elevation
X Axis Title(PF)=Main Channel Distance
X Axis Title(XS)=Station
BEGIN DESCRIPTION:
12Mile Creek Combined Model
END DESCRIPTION:
DSS Export Rating Curves= 0
DSS Export Rating Curve Sorted= 0
DSS Export Volume Flow Curves= 0
DXF Filename=..\..\..\PreRAS\12MileCreek_DS.
DXF OffsetX= 0
DXF OffsetY= 0
DXF ScaleX= 1
DXF ScaleY= 10

--- 12mile_Combined.p04 (plan) ---

Plan Title=Revised
Program Version=6.10
Short Identifier=Rev
Geom File=g07
Flow File=f01
Subcritical Flow
K Sum by GR= 0
Std Step Tol= 0.01
Critical Tol= 0.01
Num of Std Step Trials= 20
Max Error Tol= 0.33
Flow Tol Ratio= 0.001
Split Flow NTrial= 30
Split Flow Tol= 0.02
Split Flow Ratio= 0.02
Log Output Level= 0
Friction Slope Method= 1
Unsteady Friction Slope Method= 2
Unsteady Bridges Friction Slope Method= 1
Calc Critical at every XS
Parabolic Critical Depth
Global Vel Dist= 0 , 0 , 0
Global Log Level= 0
CheckData=True
Encroach Param=-1 ,0,0, 2
Encroach River=Twelvemile Crk
Encroach Reach=Reach1
Encroach Node=70440.49
       1    -100      50
Encroach Node=70376.80
       1    -100      50
Encroach Node=70328.47
       1    -100      20
Encroach Node=70269.37
       1    -100       9
Encroach Node=69736.32
       1    -100      25
Encroach Node=69385.95
       1     -35      50
Encroach Node=68870.30
       1     -55      55
Encroach Node=68826.16
       1     -65      55
Encroach Node=68786.58
       1     -65      55
Encroach Node=68294.69
       1     -60      30
Encroach Node=67801.64
       1    -100      15
Encroach Node=67739.63
       1     -85      30
Encroach Node=67703.08
       1     -30      30
Encroach Node=67500.99
       1     -30      80
Encroach Node=67056.64
       1    -100      30
Encroach Node=66632.52
       1     -55      55
Encroach Node=65990.51
       1     -12     140
Encroach Node=65446.48
       1    -100     100
Encroach Node=65040.18
       1     -75     100
Encroach Node=64958.98
       1    -135   18.34
Encroach Node=64909.54
       1    -135   18.73
Encroach Node=64559.46
       1    -160      50
Encroach Node=64221.28
       1    -155      25
Encroach Node=63741.97
       1    -130      50
Encroach Node=63206.37
       1    -100      30
Encroach Node=62495.72
       1    -150      30
Encroach Node=61909.51
       1    -150      35
Encroach Node=61363.06
       1    -130      90
Encroach Node=61315.64
       1  -76.46   97.88
Encroach Node=61243.81
       1  -76.46   97.88
Encroach Node=60836.99
       1    -150     150
Encroach Node=59995.94
       1    -100     175
Encroach Node=58892.79
       1    -300     300
Encroach Node=58127.97
       1    -150     400
Encroach Node=57013.17
       1    -450     150
Encroach Node=56350.66
       1    -250     250
Encroach Node=55746.43
       1    -250     250
Encroach Node=55257.40
       1    -450     300
Encroach Node=55042.27
       1    -450     600
Encroach Node=54857.69
       1     -45      45
Encroach Node=54802.28
       1     -66   63.83
Encroach Node=54108.83
       1     -75      75
Encroach Node=53458.67
       1    -125      55
Encroach Node=52931.33
       1    -250      55
Encroach Node=52619.52
       1    -180      50
Encroach Node=52534.89
       1    -225      60
Encroach Node=52495.01
       1    -225      60
Encroach Node=52202.20
       1    -250      50
Encroach Node=51597.62
       1    -180      50
Encroach Node=51052.63
       1    -200      50
Encroach Node=50682.11
       1    -110      50
Encroach Node=50248.03
       1    -110      25
Encroach Node=49759.58
       1    -125      75
Encroach Node=49184.70
       1     -50     100
Encroach Node=48667.24
       1     -30     100
Encroach Node=48191.72
       1     -25      40
Encroach Node=47777.40
       1  -25.86     100
Encroach Node=47351.72
       1  -24.77      55
Encroach Node=47108.14
       1  -24.77   24.34
Encroach Node=46907.61
       1  -24.77   24.34
Encroach Node=46569.62
       1  -37.24   24.74
Encroach Node=46320.07
       1     -46      50
Encroach Node=45651.45
       1    -150     150
Encroach Node=44967.12
       1     -60      60
Encroach Node=44869.64
       1   -60.5      60
Encroach Node=44509.05
       1     -80     145
Encroach Node=44261.92
       1    -100     155
Encroach Node=43748.34
       1    -300     250
Encroach Node=43282.02
       1    -270     200
Encroach Node=42648.41
       1    -130     250
Encroach Node=42039.68
       1    -200     320
Encroach Node=41492.55
       1 -256.12     250
Encroach Node=40871.32
       1    -339     235
Encroach Node=40177.37
       1    -392     286
Encroach Node=39503.83
       1    -345     280
Encroach Node=39031.68
       1  -327.1     486
Encroach Node=38316.38
       1 -308.02  213.56
Encroach Node=37808.08
       1  -122.7  197.21
Encroach Node=37715.06
       1    -120     120
Encroach Node=37658.21
       1     -85      58
Encroach Node=37589.67
       1     -80      65
Encroach Node=37232.94
       1    -130     155
Encroach Node=36811.42
       1    -125     125
Encroach Node=36537.53
       1    -100     100
Encroach Node=36420.89
       1     -85      85
Encroach Node=36314.16
       1     -85      85
Encroach Node=35775.00
       1    -225     125
Encroach Node=35163.07
       1    -100     100
Encroach Node=34601.97
       1     -35      55
Encroach Node=34099.12
       1     -75      34
Encroach Node=33621.93
       1     -90      50
Encroach Node=33559.18
       1  -94.82      71
Encroach Node=33511.66
       1     -95     100
Encroach Node=33408.90
       1     -95     100
Encroach Node=32969.85
       1    -265     150
Encroach Node=32399.51
       1    -500     300
Encroach Node=31726.87
       1     -40     250
Encroach Node=31245.50
       1     -40     250
Encroach Node=30995.08
       1     -60     250
Encroach Node=30530.72
       1     -60      70
Encroach Node=30045.32
       1     -55      55
Encroach Node=29893.68
       1    -104      86
Encroach Node=29787.76
       1     -75      50
Encroach Node=29585.08
       1     -60      25
Encroach Node=29060.25
       1     -25      95
Encroach Node=28506.38
       1     -35      35
Encroach Node=27809.50
       1    -120     120
Encroach Node=27118.91
       1    -450     200
Encroach Node=26494.56
       1    -400     500
Encroach Node=25913.01
       1    -175     250
Encroach Node=25802.52
       1    -140     130
Encroach Node=25664.88
       1    -140     130
Encroach Node=24419.09
       1    -140     240
Encroach Node=23733.89
       1    -100     350
Encroach Node=23164.62
       1    -180     550
Encroach Node=22405.28
       1    -150     550
Encroach Node=21759.82
       1    -400     400
Encroach Node=21211.30
       1    -550     250
Encroach Node=20666.59
       1    -400     400
Encroach Node=20101.98
       1     -60     500
Encroach Node=19986.16
       1     -75     150
Encroach Node=19771
       1    -100     275
Encroach Node=19421.91
       1    -100     600
Encroach Node=18956.20
       1    -100     640
Encroach Node=18916.08
       1    -100     640
Encroach Node=18484.49
       1     -70     555
Encroach Node=17875.39
       1  -38.48  474.93
Encroach Node=17148.99
       1     -70     535
Encroach Node=16370.95
       1     -70     493
Encroach Node=15951.14
       1     -71  645.63
Encroach Node=15279.92
       1     -45      95
Encroach Node=14742.98
       1    -400     222
Encroach Node=14125.66
       1    -400     250
Encroach Node=13505.45
       1    -350      40
Encroach Node=12835.75
       1    -200      45
Encroach Node=12309.70
       1    -200      62
Encroach Node=11696.94
       1     -70      75
Encroach Node=11145.04
       1 -127.78      44
Encroach Node=10702.05
       1  -70.32      55
Encroach Node=10289.46
       1  -76.94   80.81
Encroach Node=9928.911
       1    -133   63.09
Encroach Node=9419.652
       1     -55     155
Encroach Node=8802.301
       1    -130      55
Encroach Node=8710.185
       1     -56      95
Encroach Node=8606.466
       1     -30      95
Encroach Node=8301.730
       1     -88      90
Encroach Node=7698.357
       1    -200      35
Encroach Node=7019.528
       1    -322     222
Encroach Node=6575.087
       1    -322     222
Encroach Node=5628.286
       1     -80     225
Encroach Node=4987.521
       1     -80   56.54
Encroach Node=4618.135
       1  -66.88   41.29
Encroach Node=4099.218
       1     -66      66
Encroach Node=3553.867
       1     -66      66
Encroach Node=3092.122
       1     -85      66
Encroach Node=2604.736
       1    -210      65
Encroach Node=2258.369
       1    -375      65
Encroach Node=1695.569
       1    -210      96
Encroach Node=969.1144
       1    -145      30
Encroach Node=443.4068
       1     -65     175
Encroach Node=99.87141
       1     -94      55
Computation Interval=1HOUR
Output Interval=1HOUR
Instantaneous Interval=1HOUR
Mapping Interval=1HOUR
Computation Time Step Use Courant=        0
Computation Time Step Use Time Series=    0
Computation Time Step Count To Double=0
Computation Time Step Max Doubling=0
Computation Time Step Max Halving=0
Computation Time Step Residence Courant=0
Run HTab= 0
Run UNet= 0
Run Sediment= 0
Run PostProcess= 0
Run WQNet= 0
Run RASMapper= 0
UNET Theta= 1
UNET Theta Warmup= 1
UNET ZTol= 0.02
UNET ZSATol= 0.1
UNET MxIter= 20
UNET Max Iter WO Improvement= 0
UNET MaxInSteps= 20
UNET DtIC= 0
UNET DtMin= 0
UNET MaxCRTS= 20
UNET WFStab= 2
UNET SFStab= 1
UNET WFX= 1
UNET SFX= 1
UNET Gravity=32.174
UNET 1D Methodology=Finite Difference
UNET DSS MLevel= 4
UNET Pardiso=0
UNET DZMax Abort= 100
UNET Use Existing IB Tables=-1
UNET Froude Reduction=False
UNET Froude Limit= 1
UNET Froude Power= 10
UNET D1 Cores= 0
UNET WindReference=Eulerian
UNET WindDragFormulation=Hsu (1988)
UNET D2 Coriolis=0
UNET D2 Cores= 0
UNET D2 Theta= 1
UNET D2 Theta Warmup= 1
UNET D2 Z Tol= 0.01
UNET D2 Volume Tol= 0.01
UNET D2 Max Iterations= 20
UNET D2 Equation= 0
UNET D2 RampUpFraction=0.1
UNET D2 TimeSlices= 1
UNET D2 Turbulence Formulation=Non-Conservative (original)
UNET D2 Eddy Viscosity=0.3
UNET D2 Transverse Eddy Viscosity=0.1
UNET D2 Smagorinsky Mixing=0
UNET D2 BCVolumeCheck=0
UNET D2 Cores=0
UNET D2 SolverType=PARDISO (Direct)
UNET D2 Minimum Iterations= 2147483647
UNET D2 Maximum Iterations= 2147483647
UNET D2 Restart Number= 10
UNET D2 Relaxation Coeff=1.3
UNET D2 SOR Precondition Iterations= 10
UNET D2 ILUT Maximum Fill= 8
UNET D2 ILUT Tolerance=1E-08
UNET D1D2 MaxIter= 0
UNET D1D2 ZTol=0.01
UNET D1D2 QTol=0.1
UNET D1D2 MinQTol=1
Write IC File= 0
Write IC File at Fixed DateTime=0
Write IC File at Sim End=0
Echo Input=False
Echo Parameters=False
Echo Output=False
Write Detailed= 0
HDF Write Warmup=0
HDF Write Time Slices=0
HDF Flush=0
HDF Compression= 1
HDF Chunk Size= 1
HDF Spatial Parts= 1
HDF Use Max Rows=0
HDF Fixed Rows= 1
Calibration Method= 0
Calibration Iterations= 20
Calibration Max Change=0.05
Calibration Tolerance=0.2
Calibration Maximum=1.5
Calibration Minimum=0.5
Calibration Optimization Method= 1
WQ AD Non Conservative
WQ ULTIMATE=-1
WQ Max Comp Step=1HOUR
WQ Output Interval=15MIN
WQ Output Selected Increments= 0
WQ Output face flow=0
WQ Output face velocity=0
WQ Output face area=0
WQ Output face dispersion=0
WQ Output cell volume=0
WQ Output cell surface area=0
WQ Output cell continuity=0
WQ Output cumulative cell continuity=0
WQ Output face conc=0
WQ Output face dconc_dx=0
WQ Output face courant=0
WQ Output face peclet=0
WQ Output face adv mass=0
WQ Output face disp mass=0
WQ Output cell mass=0
WQ Output cell source sink temp=0
WQ Output nsm pathways=0
WQ Output nsm derived pathways=0
WQ Create Restart=0
WQ Fixed Restart=0
WQ System Summary=0
WQ Write To DSS=0
Sorting and Armoring Iterations= 10
XS Update Threshold= 0.02
Bed Roughness Predictor= 0
Hydraulics Update Threshold= 0.02
Energy Slope Method= 1
Volume Change Method= 0
Sediment Retention Method= 0
Sediment TS Multiplier= 1
Warm Up Method= 0
XS Weighting Method= 0
Number of US Weighted Cross Sections= 1
Number of DS Weighted Cross Sections= 1
Upstream XS Weight=0.25
Main XS Weight=0.5
Downstream XS Weight=0.25
Number of DS XS's Weighted with US Boundary= 1
Upstream Boundary Weight= 1
Weight of XSs Associated with US Boundary= 0
Number of US XS's Weighted with DS Boundary= 1
Downstream Boundary Weight= 0.5
Weight of XSs Associated with DS Boundary= 0.5
Percentile Method= 0
Sediment Output Level= 4
Mass or Volume Output= 0
Output Increment Type= 1
Profile and TS Output Increment= 10
Transport Output Increment 1
XS Output Flag= 0
XS Output Increment= 10
Read HDF5 Sediment Hotstart= 0
Sediment Hotstart Type= 0
Write Gradation File= 0
Read Gradation Hotstart= 0
Write HDF5 File= 1
Write Binary Output= 1
Write DSS Sediment File= 0
DSS Sediment Output Type= 1
SV Curve= 0
Specific Gage Flag= 0
Subcell Erosion Methods= 0
Subcell Deposition Methods= 0
Advection Scheme= 1
Matrix Solver= 0
Implicit Weighting Factor= 1
Maximum Outer Loop Convergence Iterations= 5
Convergence Maximum Absolute= 0.001
Convergence RMSE= 0.0001
Grain Fractions Max Abs Error= 0.001
Max Subgrid Regions= 1
Max Subgrid Length Scale= 3.402823E+38
Initial Layer Thickness= 3.402823E+38
Min Layer Thickness= 3.402823E+38
Max Layer Thickness= 3.402823E+38
Number of Layers= 5

--- 12mile_Combined.p01 (plan) ---

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Plan Title=Multiprofile
Program Version=4.10
Short Identifier=Multi
Geom File=g01
Flow File=f01
Encroach Param=-1 ,0,0, 0
UNET Convert EG Bridges=-1
UNET Time Slicing=0,0, 5
UNET Junction Losses=0
WQ Output cell source sink nsm=0
WQ Output MaxMinRange=-1
WQ Daily Max Min Mean=-1
WQ Daily Range=0
WQ Daily Time=0
WQ Use Fixed Temperature=0
Disregard all LS=0
Disregard all Conn=0
Disregard all Breaches=0
Disregard all Pumps=0

--- 12mile_Combined.p02 (plan) ---

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Plan Title=floodway
Program Version=4.10
Short Identifier=FW
Geom File=g01
Flow File=f02
Encroach Node=19880.48
UNET Convert EG Bridges=-1
UNET Time Slicing=0,0, 5
UNET Junction Losses=0
WQ Output cell source sink nsm=0
WQ Output MaxMinRange=-1
WQ Daily Max Min Mean=-1
WQ Daily Range=0
WQ Daily Time=0
WQ Use Fixed Temperature=0
Disregard all LS=0
Disregard all Conn=0
Disregard all Breaches=0
Disregard all Pumps=0

--- 12mile_Combined.p03 (plan) ---

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Plan Title=Corrected Effective
Short Identifier=COR
Geom File=g05
Flow File=f01

--- 12mile_Combined.p05 (plan) ---

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Plan Title=Corrected EffectiveFW
Short Identifier=CORFW
Geom File=g05
Flow File=f02

--- 12mile_Combined.p06 (plan) ---

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Plan Title=RevisedFW
Short Identifier=RevFW
Geom File=g07
Flow File=f02

--- 12mile_Combined.p07 (plan) ---

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Plan Title=Unrestricted
Short Identifier=Unrestrict
Geom File=g03
Flow File=f01

--- 12mile_Combined.f01 (steady flow) ---

Flow Title=Multiprofile
Program Version=6.10
Number of Profiles= 5
Profile Names=10pct,4pct,2pct,1pct,02pct
River Rch & RM=Twelvemile Crk,Reach1          ,70440.49
     477     642     787     924    1272
River Rch & RM=Twelvemile Crk,Reach1          ,69736.32
     622     833    1020    1194    1635
River Rch & RM=Twelvemile Crk,Reach1          ,67500.99
     699     935    1143    1336    1826
River Rch & RM=Twelvemile Crk,Reach1          ,64559.46
     722     964    1179    1378    1882
River Rch & RM=Twelvemile Crk,Reach1          ,62495.72
     872    1160    1416    1652    2248
River Rch & RM=Twelvemile Crk,Reach1          ,60836.99
    1184    1571    1905    2223    3010
River Rch & RM=Twelvemile Crk,Reach1          ,57013.17
    1300    1722    2088    2433    3289
River Rch & RM=Twelvemile Crk,Reach1          ,54108.83
    1415    1871    2267    2638    3562
River Rch & RM=Twelvemile Crk,Reach1          ,52202.20
    1543    2036    2466    2866    3863
River Rch & RM=Twelvemile Crk,Reach1          ,44509.05
    1886    2478    2997    3476    4669
River Rch & RM=Twelvemile Crk,Reach1          ,43748.34
    1987    2609    3155    3656    4906
River Rch & RM=Twelvemile Crk,Reach1          ,39031.68
    2113    2771    3348    3878    5198
River Rch & RM=Twelvemile Crk,Reach1          ,37232.94
    2124    2784    3365    3896    5222
River Rch & RM=Twelvemile Crk,Reach1          ,35775.00
    2143    2809    3395    3930    5267
River Rch & RM=Twelvemile Crk,Reach1          ,34099.12
    3572    4651    5580    6449    8573
River Rch & RM=Twelvemile Crk,Reach1          ,32969.85
    3578    4659    5589    6459    8587
River Rch & RM=Twelvemile Crk,Reach1          ,31245.50
    3645    4744    5690    6574    8736
River Rch & RM=Twelvemile Crk,Reach1          ,29060.25
    3711    4828    5791    6689    8886
River Rch & RM=Twelvemile Crk,Reach1          ,24419.09
    3764    4895    5872    6780    9005
River Rch & RM=Twelvemile Crk,Reach1          ,22405.28
    4650    6019    7212    8300   10979
River Rch & RM=Twelvemile Crk,Reach1          ,19421.91
    4705    6088    7294    8394   11101
River Rch & RM=Twelvemile Crk,Reach1          ,14125.66
    5063    6541    7834    9006   11893
River Rch & RM=Twelvemile Crk,Reach1          ,8301.730
    5081    6564    7861    9036   11933
River Rch & RM=Twelvemile Crk,Reach1          ,5628.286
    5871    7562    9048   10379   13670
River Rch & RM=Twelvemile Crk,Reach1          ,1695.569
    5904    7604    9097   10436   13742
Boundary for River Rch & Prof#=Twelvemile Crk,Reach1          , 1
Up Type= 0
Dn Type= 3
Dn Slope=0.0043
Boundary for River Rch & Prof#=Twelvemile Crk,Reach1          , 2
Up Type= 0
Dn Type= 3
Dn Slope=0.0043
Boundary for River Rch & Prof#=Twelvemile Crk,Reach1          , 3
Up Type= 0
Dn Type= 3
Dn Slope=0.0043
Boundary for River Rch & Prof#=Twelvemile Crk,Reach1          , 4
Up Type= 0
Dn Type= 1
Dn Known WS=871.26
Boundary for River Rch & Prof#=Twelvemile Crk,Reach1          , 5
Up Type= 0
Dn Type= 3
Dn Slope=0.0043
Gate Openings=Twelvemile Crk  ,Reach1          ,54962.12,Gate #1                         ,
    2.66       1    2.66       1    2.66       1    2.66       1    2.66       1
DSS Import GetInterval= 0
DSS Import GetPeak= 0
DSS Import FillOption= 0

--- 12mile_Combined.f02 (steady flow) ---

Flow Title=Floodway
Program Version=4.10
Number of Profiles= 2
Profile Names=1pct,FW
River Rch & RM=Twelvemile Crk,Reach1          ,70440.49
     924     924
River Rch & RM=Twelvemile Crk,Reach1          ,69736.32
    1194    1194
River Rch & RM=Twelvemile Crk,Reach1          ,67500.99
    1336    1336
River Rch & RM=Twelvemile Crk,Reach1          ,64559.46
    1378    1378
River Rch & RM=Twelvemile Crk,Reach1          ,62495.72
    1652    1652
River Rch & RM=Twelvemile Crk,Reach1          ,60836.99
    2223    2223
River Rch & RM=Twelvemile Crk,Reach1          ,57013.17
    2433    2433
River Rch & RM=Twelvemile Crk,Reach1          ,54108.83
    2638    2638
River Rch & RM=Twelvemile Crk,Reach1          ,52202.20
    2866    2866
River Rch & RM=Twelvemile Crk,Reach1          ,44509.05
    3476    3476
River Rch & RM=Twelvemile Crk,Reach1          ,43748.34
    3656    3656
River Rch & RM=Twelvemile Crk,Reach1          ,39031.68
    3878    3878
River Rch & RM=Twelvemile Crk,Reach1          ,37232.94
    3896    3896
River Rch & RM=Twelvemile Crk,Reach1          ,35775.00
    3930    3930
River Rch & RM=Twelvemile Crk,Reach1          ,34099.12
    6449    6449
River Rch & RM=Twelvemile Crk,Reach1          ,32969.85
    6459    6459
River Rch & RM=Twelvemile Crk,Reach1          ,31245.50
    6574    6574
River Rch & RM=Twelvemile Crk,Reach1          ,29060.25
    6689    6689
River Rch & RM=Twelvemile Crk,Reach1          ,24419.09
    6780    6780
River Rch & RM=Twelvemile Crk,Reach1          ,22405.28
    8300    8300
River Rch & RM=Twelvemile Crk,Reach1          ,19421.91
    8394    8394
River Rch & RM=Twelvemile Crk,Reach1          ,14125.66
    9006    9006
River Rch & RM=Twelvemile Crk,Reach1          ,8301.730
    9036    9036
River Rch & RM=Twelvemile Crk,Reach1          ,5628.286
   10379   10379
River Rch & RM=Twelvemile Crk,Reach1          ,1695.569
   10436   10436
Boundary for River Rch & Prof#=Twelvemile Crk,Reach1          , 1
Up Type= 0
Dn Type= 1
Dn Known WS=871.26
Boundary for River Rch & Prof#=Twelvemile Crk,Reach1          , 2
Up Type= 0
Dn Type= 1
Dn Known WS=872.26
Gate Openings=Twelvemile Crk  ,Reach1          ,54962.12,Gate #1     ,
    2.66       1    2.66       1
DSS Import GetInterval= 0
DSS Import GetPeak= 0
DSS Import FillOption= 0

--- 12mile_Combined.g07 (geometry) ---

Geom Title=Revised
Program Version=6.10

River Reach=Twelvemile Crk  ,Reach1
Reach XY= 30
   1495702.64272   1144105.79495   1495774.82316   1141775.57021
   1494407.19488   1140169.31463   1493399.38025   1136049.94882
   1490213.22343   1133578.28806   1487724.90256    1129534.0853
   1485578.80446   1128003.09252   1483539.30577   1127574.01115
   1481581.74803   1124891.32415   1480159.31266   1124163.01608
   1479643.35433   1121715.21588   1478206.60564   1120714.41699
   1479025.94488   1119673.73491   1479005.96588    1118060.0771
   1477899.08497   1118049.17487   1477663.63615    1117298.2628
   1475741.39272   1116327.16535   1475597.10039   1114948.85663
   1477342.69587   1114038.23261   1477315.31824   1111837.94816
   1476946.06135    1110707.9626   1474394.54823   1109651.75591
    1473451.3645   1107984.01739   1474983.38386   1107358.12927
   1474901.92356   1106477.34711   1476285.87008   1105865.80217
   1476654.13386   1103632.08038   1477490.35531   1102952.16175
   1475146.33957   1100442.61713   1476259.42356   1099408.11581

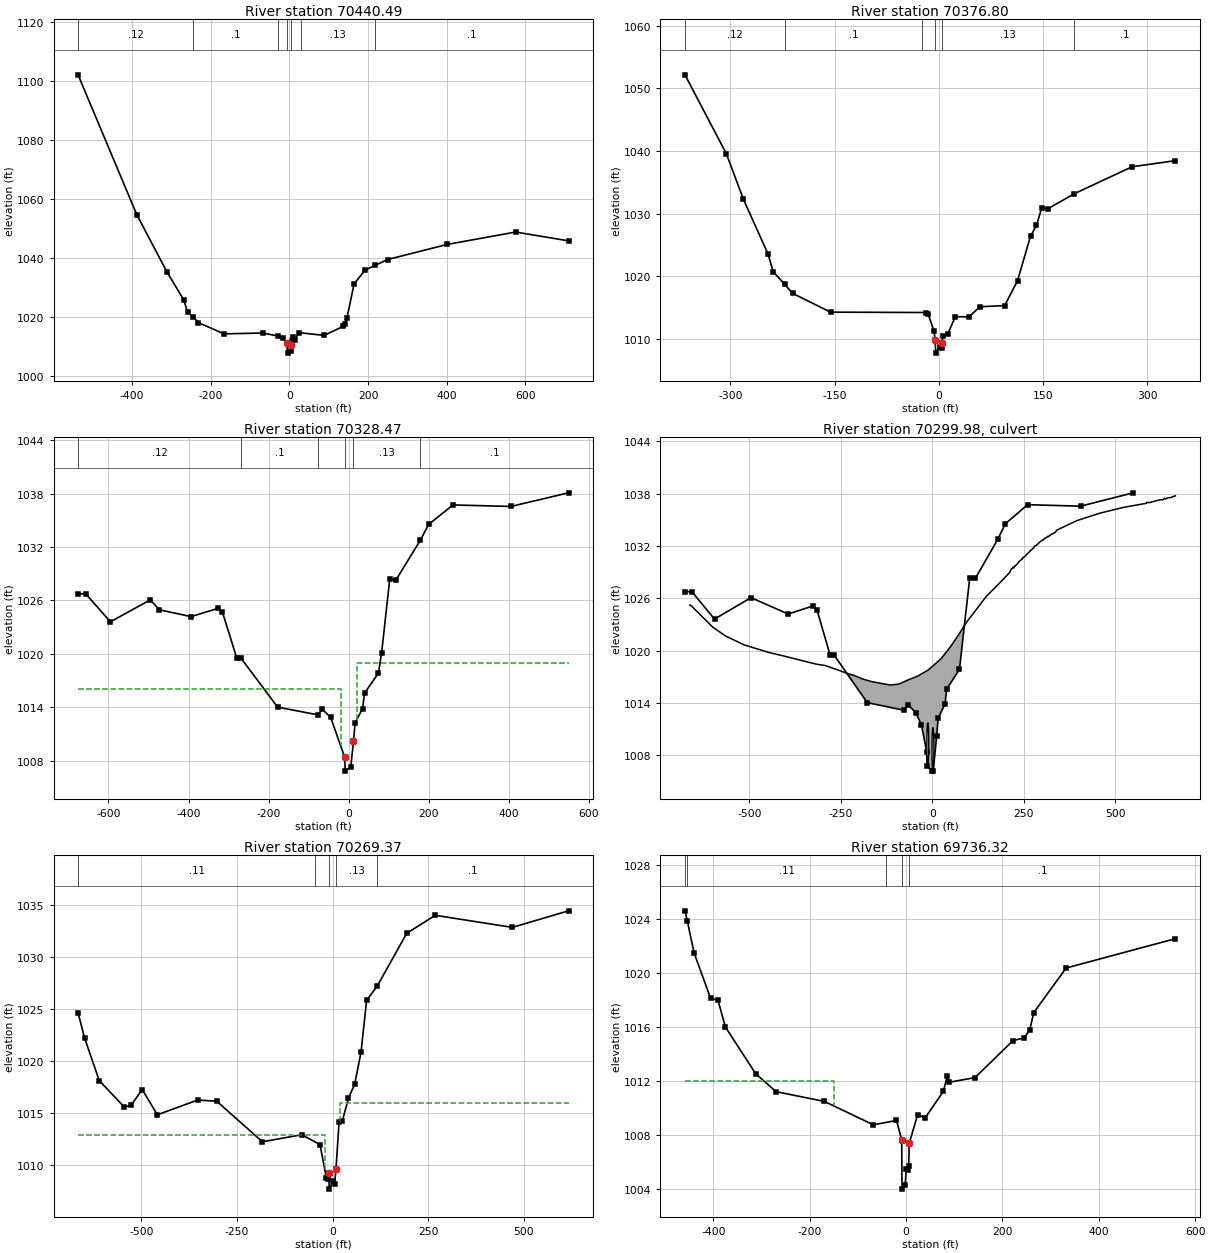
Type RM Length L Ch R = 1 ,70440.49,20.57367,63.69299,100.789
XS GIS Cut Line= 6
   1496196.42946   1144264.92651   1495864.62434   1144066.57251
   1495691.79396   1144089.90846   1495474.47999   1144232.11056
   1495397.90945   1144284.61614   1495119.33891   1144468.38517
#Sta/Elev= 30
 -537.38 1102.12    -388 1054.77  -311.9 1035.52 -268.63 1025.94 -258.82 1021.74
 -244.08 1020.11 -231.48 1018.22 -166.04 1014.42   -67.9 1014.71   -29.5 1013.72
  -15.35 1012.99   -6.87 1011.36   -4.45  1007.9    4.13  1008.7    5.33 1010.56
    6.38 1011.96   10.12 1013.23   14.75 1012.51   24.22 1014.84   88.48  1013.9
  136.73 1016.96  141.59 1017.69  146.67 1019.94  164.44 1031.32  192.33 1035.98
  217.22 1037.59  249.85 1039.59  401.23  1044.7  575.26 1048.89  709.88 1045.92
#Mann= 7 ,-1,0
 -537.38     .12       0 -244.08      .1       0   -29.5     .13       0
-6.86999    .045       05.330017     .13       030.20001     .13       0
  217.22      .1       0
Bank Sta=-6.87,5.33
XS Rating Curve= 0 ,0
Exp/Cntr=0.3,0.1

Type RM Length L Ch R = 1 ,70376.80,96.50882,48.3321,38.07024
BEGIN DESCRIPTION:
TWE_39USX
END DESCRIPTION:
XS GIS Cut Line= 5
   1496091.77723   1144119.63615   1495867.47835    1144060.1706
   1495738.18734   1144028.10171    1495665.0876   1144013.22441
   1495421.00984   1144118.80413
#Sta/Elev= 30
 -365.44 1052.18 -305.77 1039.55 -281.42 1032.32 -245.78 1023.51 -238.46 1020.71
  -221.9 1018.69  -210.4 1017.25 -155.93 1014.25  -19.04 1014.19  -15.27 1013.88
   -6.87 1011.16   -5.45  1009.8   -4.45  1007.7     .91 1008.71    4.13  1008.5
    4.71 1009.39    5.33 1010.36   12.52 1010.71   23.79 1013.55   43.11 1013.47
   58.95 1015.11   94.65  1015.3  113.17 1019.28  131.86 1026.38  140.43 1028.11
  147.92 1030.88  157.35  1030.8  195.09 1033.19  278.13 1037.49  340.35 1038.46
#Mann= 6 ,-1,0
 -365.44     .12       0  -221.9      .1       0-24.1499     .13       0
-5.45001    .045       04.709991     .13       0  195.09      .1       0
Bank Sta=-5.45,4.71
XS Rating Curve= 0 ,0
Exp/Cntr=0.5,0.3

Type RM Length L Ch R = 1 ,70328.47,64.05273,59.09576,61.7731
BEGIN DESCRIPTION:
Log House Rd (TWE_39) - US
END DESCRIPTION:
XS GIS Cut Line= 3
   1496421.06857   1143843.50164   1495734.58333   1143980.87303
   1495183.18602   1144116.22277
#Sta/Elev= 30
-675.955 1026.76-656.733 1026.73-595.203  1023.6-495.472 1026.06-472.637 1024.94
 -393.74 1024.18-327.043  1025.1-315.568  1024.7-279.481  1019.5-269.223 1019.52
-177.711 1014.02 -76.163 1013.14 -66.572  1013.8 -45.157 1012.86 -10.335 1008.41
  -8.732 1006.83   5.023 1007.28  11.794 1010.19  15.841 1012.24  34.561 1013.86
  39.361 1015.59  74.038 1017.83  82.152 1020.15 102.253 1028.37 117.785 1028.29
 178.551 1032.74  199.57 1034.54 260.259 1036.72 404.974 1036.55 548.704 1038.08
#Mann= 6 ,-1,0
-675.955     .12       0-269.223      .1       0 -76.163     .13       0
 -10.335    .045       011.79401     .13       0 178.551      .1       0
#XS Ineff= 2 ,-1
-675.955     -20    1016      20548.7039    1019
Permanent Ineff=
       F       F
Bank Sta=-10.335,11.794
XS Rating Curve= 0 ,0
Skew Angle= 15
Exp/Cntr=0.5,0.3

Type RM Length L Ch R = 2 ,70299.98,,,
BEGIN DESCRIPTION:
Log House Rd (TWE_39) - TOR
Skew = 15 degrees
END DESCRIPTION:
Bridge Culvert--1,0,-1,-1, 0
Deck Dist Width WeirC Skew NumUp NumDn MinLoCord MaxHiCord MaxSubmerge Is_Ogee
8,42.3,2.6,15, 151, 151, 1016.04, , 0.95, 0, 0,0,,
-662.867-662.673-659.254-599.975-565.405-514.993-446.364-405.003-367.081-319.799
-291.932-249.025-231.252-213.721-189.544-166.091-141.354-113.245 -91.087 -66.659
 -40.781 -26.582 -12.045  -3.738   1.545  24.805  50.788  73.121  94.574 119.997
 146.985 181.575 211.741 212.639 213.875 214.455  215.15 215.479 218.811 220.328
 222.202 222.907 224.925 225.379 227.765 228.731 231.813 233.184 234.469 235.947
 236.884 237.666   241.8 242.341 243.945 245.268 246.002 246.958 248.707 251.005
  252.59  254.29 255.681 256.589 258.105 258.289 260.858 262.529 264.635 265.591
  265.89  266.47 267.851 268.411 270.063 271.589 272.352 274.246 274.767 276.042
 277.114 278.283   279.5 279.838 283.605 284.156 286.242 287.392 289.227   289.7
 291.082 291.671 292.511 294.366 296.278  299.08 300.934 303.146 305.435 306.343
 309.676  312.69 313.636 315.462 316.592 317.867 319.635 322.165 323.952  325.16
 326.792   327.7 329.564  331.09 334.471 334.877 336.538 338.103  339.04 394.706
 457.994 523.242 584.704 586.269  590.76 592.364 594.595 615.073 618.888 621.728
 623.834  628.47 629.165 629.958 632.044 632.334 633.937 634.517 636.806  637.54
 640.148 642.003 644.205 644.813 646.948 651.903 653.372 655.342 656.675 661.756
 664.026
  1025.2 1025.17 1025.15 1022.68 1021.67 1020.66 1019.77 1019.36 1018.96 1018.46
 1018.27 1017.63 1017.35 1017.14 1016.72 1016.44 1016.24 1016.04 1016.16 1016.62
 1017.05 1017.39 1017.75 1018.04 1018.23 1019.11 1020.51  1021.9 1023.32 1024.69
 1026.19 1027.64 1028.97 1029.12 1029.17 1029.23 1029.29 1029.33 1029.42 1029.54
 1029.47 1029.51 1029.71 1029.69 1029.73  1029.8 1029.92 1029.98 1030.11 1030.16
 1030.18 1030.22 1030.36 1030.39 1030.46 1030.55 1030.52 1030.59 1030.71 1030.72
 1030.77 1030.83 1030.91 1030.97 1031.02 1031.06 1031.15  1031.2 1031.28 1031.33
 1031.34 1031.39 1031.44 1031.45 1031.54 1031.57  1031.6  1031.7 1031.72 1031.76
 1031.77 1031.89 1031.96 1031.99 1032.03 1032.06 1032.17 1032.18 1032.24 1032.26
 1032.34 1032.38  1032.4 1032.46 1032.51  1032.6 1032.67 1032.67 1032.81 1032.84
  1032.9 1032.99 1033.02  1033.1 1033.06 1033.06 1033.15 1033.24 1033.27 1033.32
  1033.4 1033.41 1033.39 1033.45 1033.52 1033.53 1033.61 1033.67 1033.78 1034.89
 1035.75 1036.42 1036.88 1036.99 1036.96 1036.95 1036.98 1037.21 1037.25 1037.27
 1037.29 1037.27 1037.27 1037.29 1037.35 1037.35 1037.44 1037.48 1037.37 1037.38
 1037.45 1037.49 1037.51 1037.52 1037.53 1037.54 1037.55 1037.58 1037.66 1037.69
 1037.74
                                                                                
                                                                                
                                                                                
                                                                                
                                                                                
                                                                                
                                                                                
                                                                                
                                                                                
                                                                                
                                                                                
                                                                                
                                                                                
                                                                                
                                                                                
        
-662.867-662.673-659.254-599.975-565.405-514.993-446.364-405.003-367.081-319.799
-291.932-249.025-231.252-213.721-189.544-166.091-141.354-113.245 -91.087 -66.659
 -40.781 -26.582 -12.045  -3.738   1.545  24.805  50.788  73.121  94.574 119.997
 146.985 181.575 211.741 212.639 213.875 214.455  215.15 215.479 218.811 220.328
 222.202 222.907 224.925 225.379 227.765 228.731 231.813 233.184 234.469 235.947
 236.884 237.666   241.8 242.341 243.945 245.268 246.002 246.958 248.707 251.005
  252.59  254.29 255.681 256.589 258.105 258.289 260.858 262.529 264.635 265.591
  265.89  266.47 267.851 268.411 270.063 271.589 272.352 274.246 274.767 276.042
 277.114 278.283   279.5 279.838 283.605 284.156 286.242 287.392 289.227   289.7
 291.082 291.671 292.511 294.366 296.278  299.08 300.934 303.146 305.435 306.343
 309.676  312.69 313.636 315.462 316.592 317.867 319.635 322.165 323.952  325.16
 326.792   327.7 329.564  331.09 334.471 334.877 336.538 338.103  339.04 394.706
 457.994 523.242 584.704 586.269  590.76 592.364 594.595 615.073 618.888 621.728
 623.834  628.47 629.165 629.958 632.044 632.334 633.937 634.517 636.806  637.54
 640.148 642.003 644.205 644.813 646.948 651.903 653.372 655.342 656.675 661.756
 664.026
  1025.2 1025.17 1025.15 1022.68 1021.67 1020.66 1019.77 1019.36 1018.96 1018.46
 1018.27 1017.63 1017.35 1017.14 1016.72 1016.44 1016.24 1016.04 1016.16 1016.62
 1017.05 1017.39 1017.75 1018.04 1018.23 1019.11 1020.51  1021.9 1023.32 1024.69
 1026.19 1027.64 1028.97 1029.12 1029.17 1029.23 1029.29 1029.33 1029.42 1029.54
 1029.47 1029.51 1029.71 1029.69 1029.73  1029.8 1029.92 1029.98 1030.11 1030.16
 1030.18 1030.22 1030.36 1030.39 1030.46 1030.55 1030.52 1030.59 1030.71 1030.72
 1030.77 1030.83 1030.91 1030.97 1031.02 1031.06 1031.15  1031.2 1031.28 1031.33
 1031.34 1031.39 1031.44 1031.45 1031.54 1031.57  1031.6  1031.7 1031.72 1031.76
 1031.77 1031.89 1031.96 1031.99 1032.03 1032.06 1032.17 1032.18 1032.24 1032.26
 1032.34 1032.38  1032.4 1032.46 1032.51  1032.6 1032.67 1032.67 1032.81 1032.84
  1032.9 1032.99 1033.02  1033.1 1033.06 1033.06 1033.15 1033.24 1033.27 1033.32
  1033.4 1033.41 1033.39 1033.45 1033.52 1033.53 1033.61 1033.67 1033.78 1034.89
 1035.75 1036.42 1036.88 1036.99 1036.96 1036.95 1036.98 1037.21 1037.25 1037.27
 1037.29 1037.27 1037.27 1037.29 1037.35 1037.35 1037.44 1037.48 1037.37 1037.38
 1037.45 1037.49 1037.51 1037.52 1037.53 1037.54 1037.55 1037.58 1037.66 1037.69
 1037.74
                                                                                
                                                                                
                                                                                
                                                                                
                                                                                
                                                                                
                                                                                
                                                                                
                                                                                
                                                                                
                                                                                
                                                                                
                                                                                
                                                                                
                                                                                
        
BR Coef=-1 ,-1 , 0 ,, 0 ,,,0.8,0,,0,
WSPro=,,,, 1 ,,,, 0 ,,,, 0 ,,,,-1 ,-1 ,-1 , 0 , 0 , 0 , 0 , 0
Culvert=1,5,5,42.3,0.013,0.2,1,1,3,1006.72,-12.47,1006.71,-12.47,Culvert #1  , 0 ,8
  -12.47  -12.47
BC Culvert Barrel=1,,0
Culvert Bottom n=0.013
Culvert=1,5,5,42.3,0.013,0.2,1,1,3,1006.17,1.6,1006.8,1.6,Culvert #2  , 0 ,8
     1.6     1.6
BC Culvert Barrel=1,,0
Culvert Bottom n=0.013
BR U #Sta/Elev= 30
-675.955 1026.76-656.733 1026.73-595.203  1023.6-495.472 1026.06 -393.74 1024.18
-327.043  1025.1-315.568  1024.7-279.481  1019.5-269.223 1019.52-177.711 1014.02
 -76.163 1013.14 -66.572  1013.8 -45.157 1012.86 -29.693 1011.46 -15.585 1008.41
 -14.079 1006.71  -1.063 1006.17   2.338 1006.17  11.794 1010.19  15.841 1012.24
  34.561 1013.86  39.361 1015.59  74.038 1017.83 102.253 1028.37 117.785 1028.29
 178.551 1032.74  199.57 1034.54 260.259 1036.72 404.974 1036.55 548.704 1038.08
BR U #Mann= 6
-675.955     .12-269.223      .1 -76.163     .13 -15.585    .045  11.794     .13
 178.551      .1
BR U Banks=-15.585,
BR D #Sta/Elev= 30
-665.397 1024.63-648.368 1022.21-609.992 1018.12-544.647 1015.58-527.048 1015.75
-497.713 1017.26-458.081 1014.84-352.959 1016.25-303.059 1016.14 -183.68 1012.25
 -80.751 1012.92 -46.055 1012.11 -32.996 1011.98 -15.551  1008.7 -14.006 1006.71
 -10.335 1006.71   2.338 1006.71   6.307  1008.7  11.794 1011.06  16.778 1014.14
  26.051 1014.32  54.932 1017.43  65.799 1019.16  74.058 1020.82   88.73 1025.82
 116.732 1027.21  193.63 1032.26 267.977 1033.99 469.662 1032.83 616.406 1034.42
BR D #Mann= 5
-665.397     .11 -46.055     .13 -10.335    .045  11.794     .13 116.732      .1
BR D Banks=-15.551,6.307
BC Design=,, 0 ,, 0 ,,,,,,
BC Use User HTab Curves=0
BC User HTab FreeFlow(D)= 0

Type RM Length L Ch R = 1 ,70269.37,376.0072,533.0539,464.8225
BEGIN DESCRIPTION:
Log House Rd (TWE_39) - DS
END DESCRIPTION:
XS GIS Cut Line= 3
    1496398.9334   1143770.58465   1495727.60039   1143922.15157
   1495103.20636   1144057.00722
#Sta/Elev= 30
-665.397 1024.63-648.368 1022.21-609.992 1018.12-544.647 1015.58-527.048 1015.75
-497.713 1017.26-458.081 1014.84-352.959 1016.25-303.059 1016.14 -183.68 1012.25
 -80.751 1012.92 -32.996 1011.98 -16.575  1008.8 -12.538 1008.68 -10.335 1009.28
  -8.732  1007.7    .715 1008.47   5.023 1008.15    8.74 1009.67  16.778 1014.14
  25.616 1014.28  41.255 1016.43  57.579 1017.78  74.058 1020.82   88.73 1025.82
 116.732 1027.21  193.63 1032.26 267.977 1033.99 469.662 1032.83 616.406 1034.42
#Mann= 5 ,-1,0
-665.397     .11       0-46.0549     .13       0 -10.335    .045       0
 8.73999     .13       0 116.732      .1       0
#XS Ineff= 2 , 0
             -20  1012.9      20            1016
Permanent Ineff=
       F       F
Bank Sta=-10.335,8.74
XS Rating Curve= 0 ,0
Skew Angle= 15
Exp/Cntr=0.5,0.3

Type RM Length L Ch R = 1 ,69736.32,289.2822,350.3647,257.4523
XS GIS Cut Line= 4
   1496409.72703   1143752.26673   1495989.57251   1143563.15518
   1495774.30906   1143458.86352   1495546.87828   1143681.08629
#Sta/Elev= 30
 -458.82 1024.59 -453.93 1023.84  -439.7 1021.46 -405.62 1018.12  -390.2 1017.97
 -374.79 1015.99 -312.05 1012.54 -269.64 1011.21  -169.6 1010.49  -67.79 1008.76
  -19.77 1009.08   -8.92 1007.65   -8.33    1004   -1.84 1004.28     .53 1005.48
    4.65 1005.43    5.51 1005.72    6.78 1007.39   24.07 1009.51   40.04 1009.29
   77.52 1011.23   85.48 1012.35   89.89 1011.91  143.22 1012.25  222.13 1014.99
  245.42 1015.19  256.79 1015.78   265.1 1017.06  332.37 1020.36  559.11 1022.53
#Mann= 5 ,-1,0
 -458.82     .11       0 -453.93     .11       0-40.7099     .13       0
-8.92001    .045       06.779999      .1       0
#XS Ineff= 2 , 0
            -150    1012
Permanent Ineff=
       F       F
Bank Sta=-8.92,6.78
XS Rating Curve= 0 ,0
Exp/Cntr=0.3,0.1

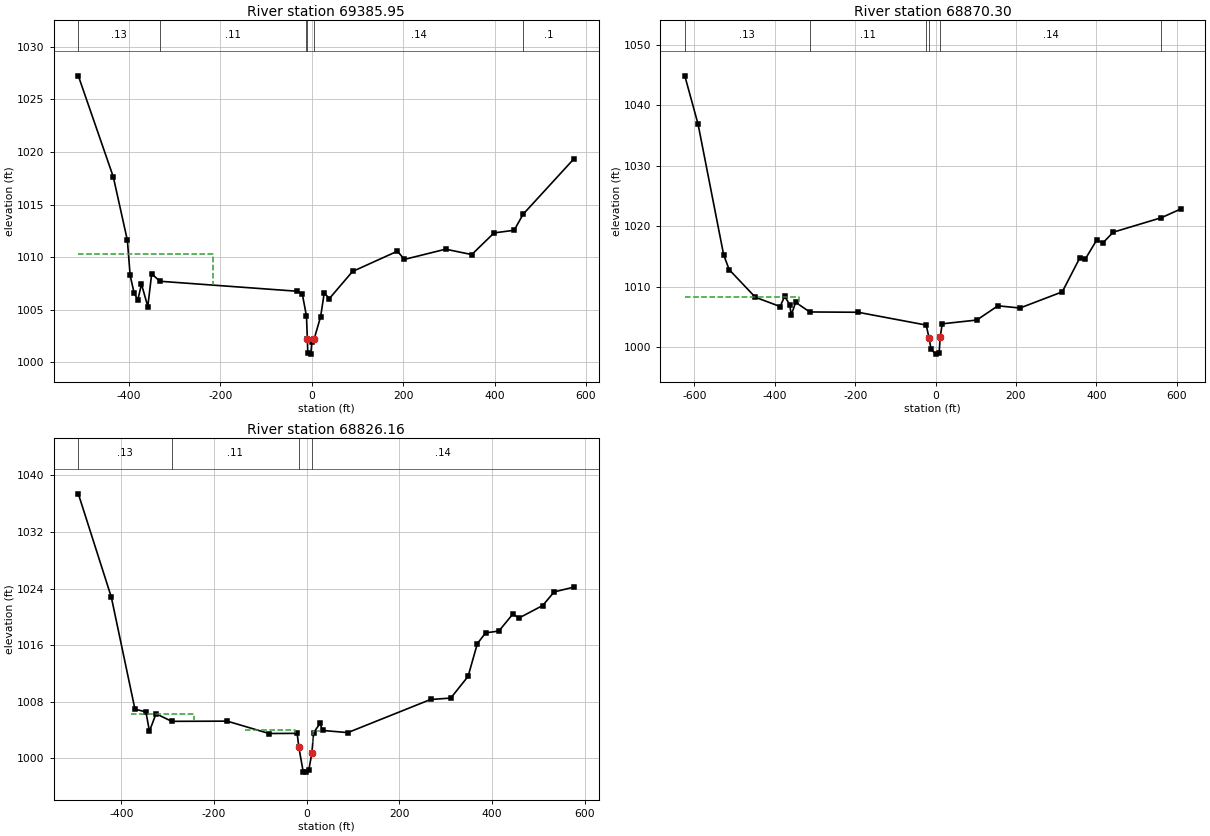
Type RM Length L Ch R = 1 ,69385.95,412.9951,515.6531,392.017
BEGIN DESCRIPTION:
TWE_38X
END DESCRIPTION:
XS GIS Cut Line= 4
   1496526.70341   1143251.30709   1496116.98031   1143313.80741
   1496022.39239   1143304.99541   1495448.57612    1143270.4042
#Sta/Elev= 30
 -510.22 1027.25 -433.72 1017.63 -402.95  1011.6 -396.95 1008.28 -388.16 1006.58
 -380.02 1005.94 -372.17 1007.44 -358.29 1005.31 -349.81 1008.41 -331.55 1007.71
  -31.27 1006.76  -20.52 1006.52  -11.27 1004.39   -9.41 1002.22   -8.33 1000.85
   -1.84 1000.78     .53 1001.98    5.51 1002.22   19.68 1004.35   27.51 1006.59
   38.86 1006.07   89.37 1008.64  187.55 1010.57  202.99 1009.79  292.88 1010.76
  350.16 1010.25  398.93 1012.31  442.92 1012.56  462.35 1014.08   574.1 1019.38
#Mann= 6 ,-1,0
 -510.22     .13       0 -331.55     .11       0-11.2699     .14       0
   -9.41     .04       05.509979     .14       0  462.35      .1       0
#XS Ineff= 2 , 0
         -216.37 1010.34
Permanent Ineff=
       F       F
Bank Sta=-9.41,5.51
XS Rating Curve= 0 ,0
Exp/Cntr=0.3,0.1

Type RM Length L Ch R = 1 ,68870.30,37.21201,44.13676,38.35141
BEGIN DESCRIPTION:
TWE_37USX
END DESCRIPTION:
XS GIS Cut Line= 5
   1496605.63648   1142829.78609   1496012.44554   1142909.22507
   1495987.34022   1142913.22408   1495949.92782   1142918.97867
   1495441.45177   1143181.21161
#Sta/Elev= 30
 -624.06 1044.91 -590.99 1036.89 -527.33 1015.27 -513.55 1012.82 -448.43 1008.25
 -386.77 1006.72 -375.61 1008.41 -362.87 1007.03 -359.26 1005.31 -348.07 1007.41
 -313.08 1005.82 -192.92 1005.77  -23.39 1003.65  -16.28 1001.56  -11.32  999.65
     .04  998.84     8.9  998.99   11.39 1001.64   16.56 1003.86  102.57 1004.48
  155.13 1006.84  209.94 1006.47  315.27 1009.15  359.21 1014.81  372.38 1014.56
  400.66 1017.69  416.89 1017.28  441.87 1019.02  562.18 1021.43  609.81 1022.86
#Mann= 6 ,-1,0
 -624.06     .13       0 -313.08     .11       0  -23.39     .14       0
  -16.28     .05       011.39001     .14       0  562.18      .1       0
#XS Ineff= 2 , 0
         -339.96 1008.28
Permanent Ineff=
       F       F
Bank Sta=-16.28,11.39
XS Rating Curve= 0 ,0
Exp/Cntr=0.5,0.3

Type RM Length L Ch R = 1 ,68826.16,65.08826,39.57481,37.44172
BEGIN DESCRIPTION:
E. of Midway Rd (US) (TWE_37) - US
END DESCRIPTION:
XS GIS Cut Line= 6
   1496466.19357   1142756.73163   1496075.21063   1142864.33202
   1495983.78248   1142869.49934   1495950.60564   1142876.84711
   1495871.80282   1142945.02034    1495475.3061   1143122.61745
#Sta/Elev= 30
 -492.72 1037.39 -421.55 1022.78 -370.57 1006.94 -346.93 1006.56 -339.29 1003.82
 -325.11  1006.3 -291.34 1005.22 -171.61 1005.25  -81.23  1003.5  -20.62 1003.52
  -16.98 1001.55   -7.64  998.12   -1.79  998.04    4.37   998.3    11.1  1000.7
   14.93 1003.61   28.78 1004.94   34.08 1003.93   88.73 1003.63   267.1 1008.31
  310.74 1008.51  348.14 1011.58  368.21 1016.22  386.01 1017.73  414.64 1017.99
  444.54 1020.38   458.2 1019.84   509.2  1021.6  533.78 1023.52     577 1024.21
#Mann= 4 ,-1,0
 -492.72     .13       0 -291.34     .11       0  -16.98     .05       0
11.10001     .14       0
#XS Ineff= 3 ,-1
  -378.3    -243  1006.3 -133.92-24.6499 1004.0113.10999   27.72  1003.9
Permanent Ineff=
       F       F       F
Bank Sta=-16.98,11.1
XS Rating Curve= 0 ,0
Exp/Cntr=0.5,0.3