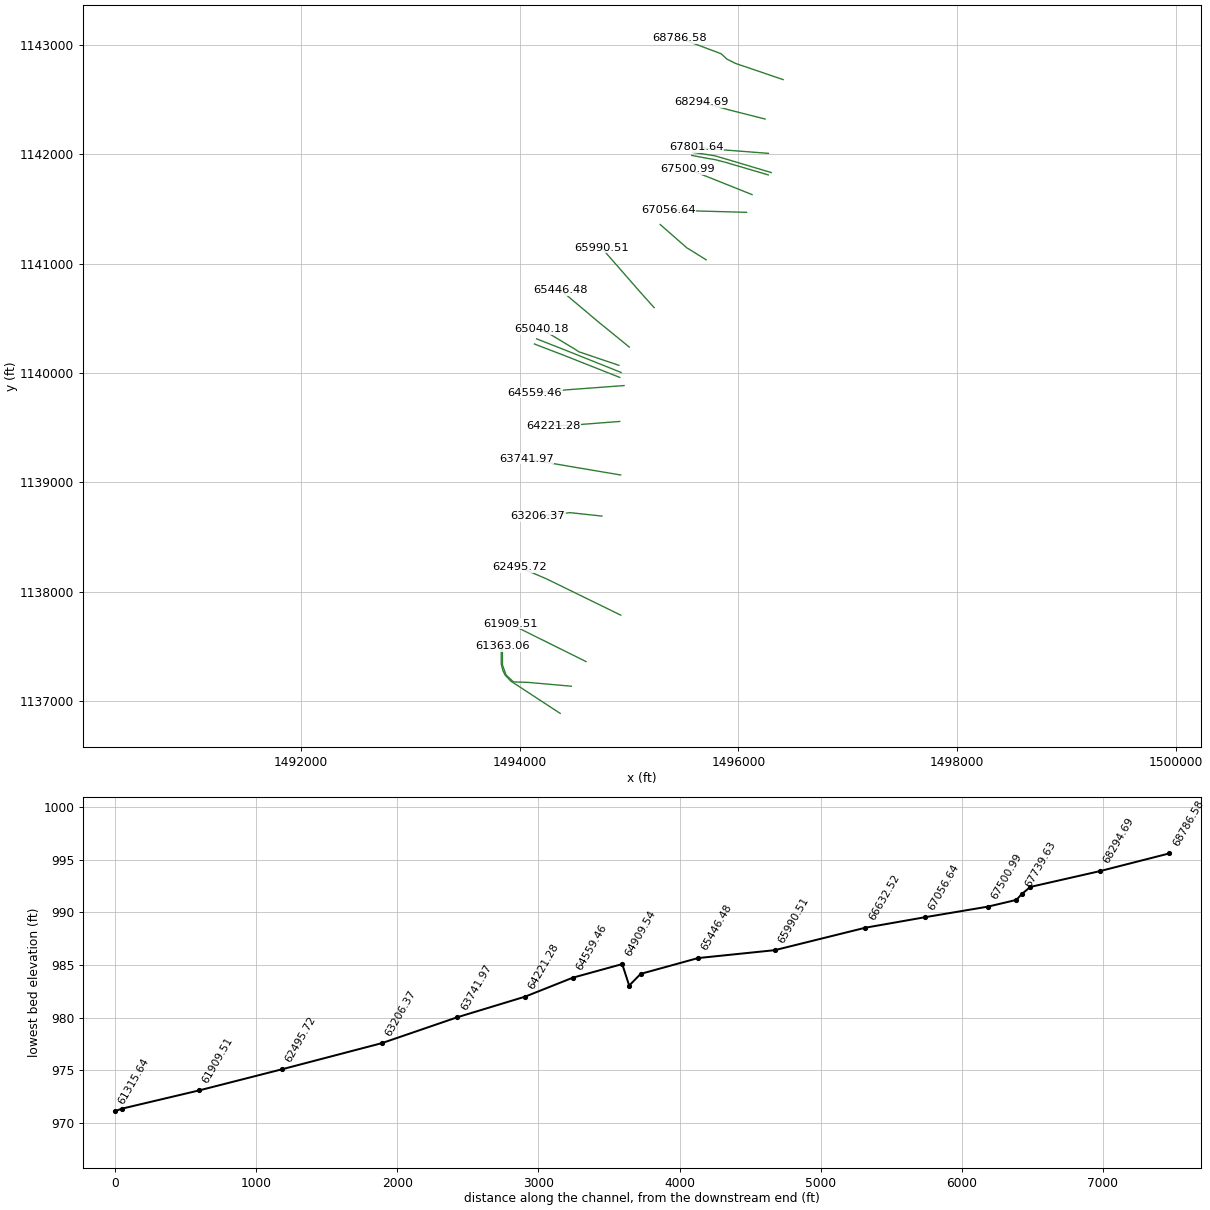
HEC-RAS study 12mile_Combined.prj: 12mile Creek Combined Model

--- 12mile_Combined.g07 (geometry) --- (continued)

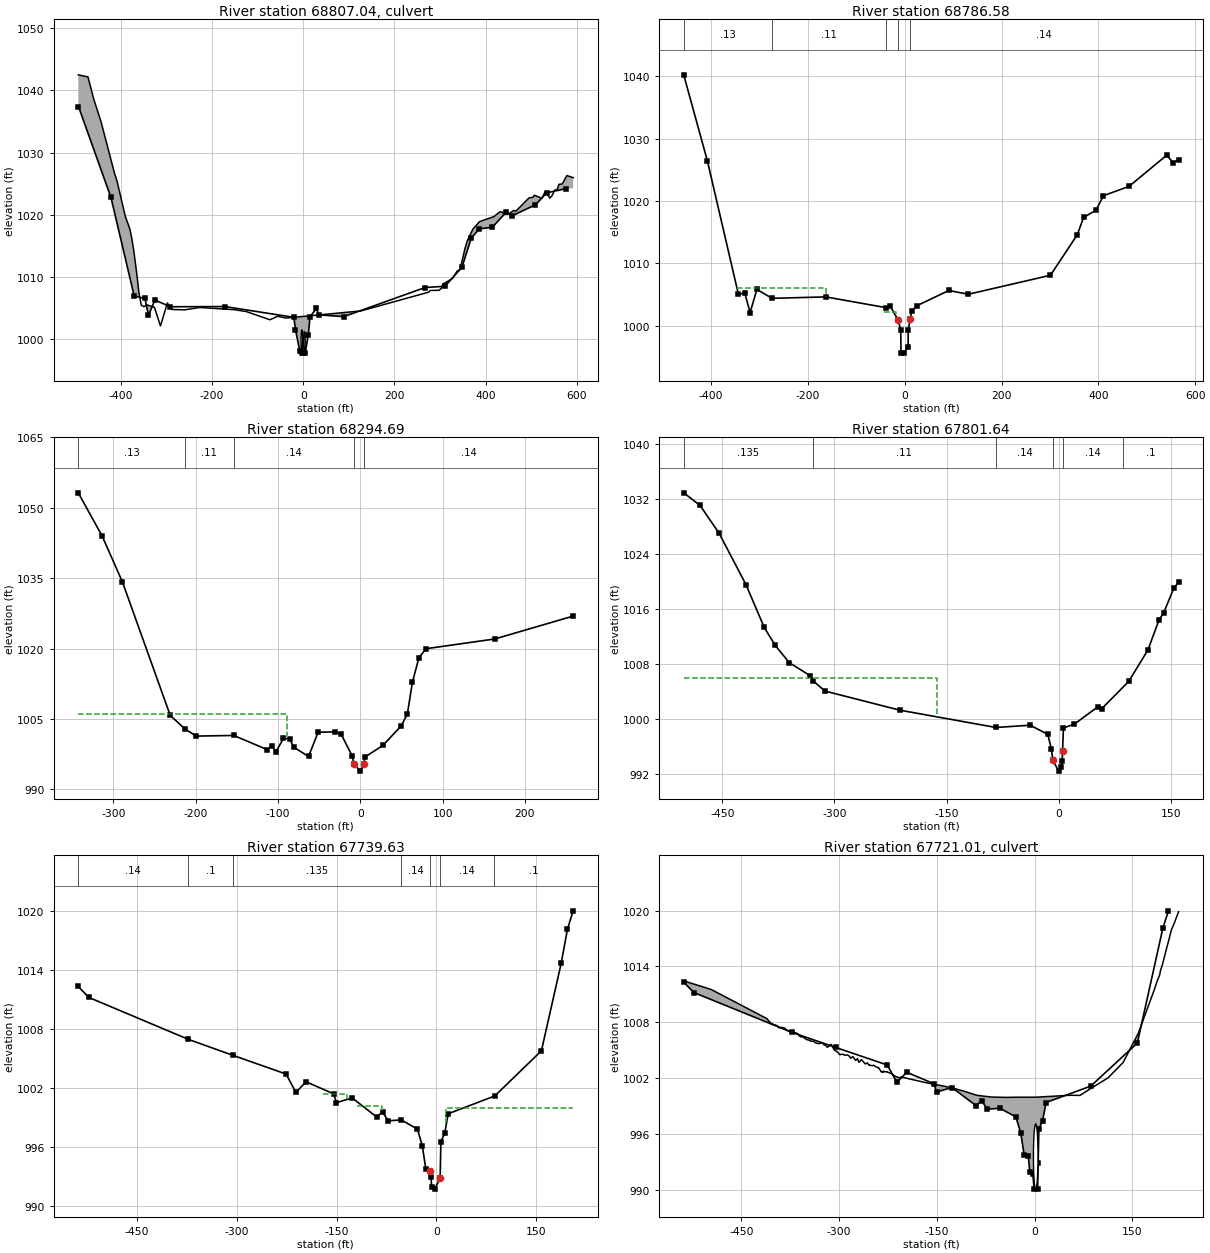
Type RM Length L Ch R = 2 ,68807.04,,,
BEGIN DESCRIPTION:
E. of Midway Rd (US) (TWE_37) - TOR
END DESCRIPTION:
Bridge Culvert--1,0,-1,-1, 0
Deck Dist Width WeirC Skew NumUp NumDn MinLoCord MaxHiCord MaxSubmerge Is_Ogee
4,30.3,2.6,0, 60, 60, 1003.13, , 0.95, 0, 0,0,,
 -493.15 -471.91 -459.16 -443.33 -413.85 -408.05 -390.08 -380.16 -375.93 -371.67
 -364.68 -360.43 -355.05 -348.99 -342.81 -326.28 -312.96 -297.81 -289.21 -260.31
  -227.1 -150.83 -124.96  -73.06  -55.46  -38.79  126.52  275.22  278.44  297.64
  303.05  306.18   327.4  337.42  343.94  354.74  359.74  372.12  386.36  417.91
  431.02  435.91  440.15  451.02  462.03  465.99  494.49  503.97  506.41  523.17
  529.79  534.59  540.27  544.79  551.62   556.2  560.82  567.79  578.05  591.79
 1042.48 1042.14 1038.56 1034.96  1026.7 1025.37 1019.75 1017.74 1016.26 1014.31
  1010.4 1007.59 1005.46 1005.23 1005.53 1005.13 1002.14 1005.83 1004.79 1004.72
  1005.1 1004.75 1004.45 1003.13  1003.7  1003.4 1004.55 1007.57 1007.84 1007.86
 1008.19 1008.85 1009.78 1010.94 1011.22 1014.61 1015.82 1017.71 1018.89  1019.7
 1020.46 1020.46 1020.07 1020.18  1020.7 1020.56 1022.68 1022.82 1023.14 1022.65
  1023.6 1023.46 1022.67 1022.99 1023.98 1023.99 1024.89 1024.95  1026.3 1025.95
                                                                                
                                                                                
                                                                                
                                                                                
                                                                                
                                                                                
 -473.15 -459.16 -443.33 -413.85 -408.05 -390.08 -380.16 -375.93 -371.67 -364.68
 -360.43 -355.05 -348.99 -342.81 -326.28 -312.96 -297.81 -289.21 -260.31  -227.1
 -150.83 -124.96  -73.06  -55.46  -38.79  126.52   270.4  275.22  278.44  297.64
  303.05  306.18   327.4  337.42  343.94  354.74  359.74  372.12  386.36  417.91
  431.02  435.91  440.15  451.02  462.03  465.99  494.49  503.97  506.41  523.17
  529.79  534.59  540.27  544.79  551.62   556.2  560.82  567.79  578.05  591.79
 1042.48 1038.56 1034.96  1026.7 1025.37 1019.75 1017.74 1016.26 1014.31  1010.4
 1007.59 1005.46 1005.23 1005.53 1005.13 1002.14 1005.83 1004.79 1004.72  1005.1
 1004.75 1004.45 1003.13  1003.7  1003.4 1004.55 1007.68 1007.57 1007.84 1007.86
 1008.19 1008.85 1009.78 1010.94 1011.22 1014.61 1015.82 1017.71 1018.89  1019.7
 1020.46 1020.46 1020.07 1020.18  1020.7 1020.56 1022.68 1022.82 1023.14 1022.65
  1023.6 1023.46 1022.67 1022.99 1023.98 1023.99 1024.89 1024.95  1026.3 1025.95
                                                                                
                                                                                
                                                                                
                                                                                
                                                                                
                                                                                
BR Coef=-1 ,-1 , 0 ,, 0 ,,,0.8,0,,0,
WSPro=,,,, 1 ,,,, 0 ,,,, 0 ,,,,-1 ,-1 ,-1 , 0 , 0 , 0 , 0 , 0
Culvert=1,3.5,3.5,30.3,0.024,0.9,1,2,3,998.03,-3,997.89,-3,Culvert #2  , 0 ,4
      -3      -3
BC Culvert Barrel=1,,0
Culvert Bottom n=0.024
Culvert=1,3.5,3.5,30.3,0.024,0.9,1,2,3,997.78,2.5,997.75,2.5,Culvert #3  , 0 ,4
     2.5     2.5
BC Culvert Barrel=1,,0
Culvert Bottom n=0.024
BR U #Sta/Elev= 30
 -492.72 1037.39 -421.55 1022.78 -370.57 1006.94 -346.93 1006.56 -339.29 1003.82
 -325.11  1006.3 -291.34 1005.22 -171.61 1005.25  -20.62 1003.52  -16.98 1001.55
   -7.64  998.12   -1.79  997.77     .14  997.77    4.37  997.77    11.1  1000.7
   14.93 1003.61   28.78 1004.94   34.08 1003.93   88.73 1003.63   267.1 1008.31
  310.74 1008.51  348.14 1011.58  368.21 1016.22  386.01 1017.73  414.64 1017.99
  444.54 1020.38   458.2 1019.84   509.2  1021.6  533.78 1023.52     577 1024.21
BR U #Mann= 4
 -492.72     .13 -291.34     .11  -16.98    .045    11.1     .14
BC Design=,, 0 ,, 0 ,,,,,,
BC Use User HTab Curves=0
BC User HTab FreeFlow(D)= 0

Type RM Length L Ch R = 1 ,68786.58,419.7679,491.8906,444.9928
BEGIN DESCRIPTION:
E. of Midway Rd (US) (TWE_37) - DS
END DESCRIPTION:
XS GIS Cut Line= 5
   1496410.20374   1142683.81496   1495972.06332   1142833.04101
   1495896.19291   1142871.40584   1495842.32448   1142920.92126
    1495466.1916   1143061.41962
#Sta/Elev= 30
 -456.67 1040.23 -407.77 1026.43 -343.88 1005.11  -330.3 1005.17 -319.49  1002.1
 -305.43 1005.81 -274.16 1004.38 -163.11 1004.61  -38.25 1002.88  -29.71 1003.09
  -13.58  1000.9   -8.22   999.3   -7.64  995.67   -1.79  995.59    7.14  996.63
    7.21  999.34   11.26 1001.01   14.39 1002.34   25.58 1003.21   91.21 1005.64
  131.26 1005.03  301.16 1008.08  356.67 1014.59  369.59 1017.36  395.13  1018.5
  410.56 1020.84  463.38 1022.33  541.46 1027.34  554.53 1026.15  565.89 1026.63
#Mann= 5 ,-1,0
 -456.67     .13       0 -274.16     .11       0  -38.25     .14       0
-13.5799     .05       011.26001     .14       0
#XS Ineff= 3 ,-1
 -347.53 -163.11    1006-42.2999  -18.11 1002.1416.36002   34.381002.115
Permanent Ineff=
       F       F       F
Bank Sta=-13.58,11.26
XS Rating Curve= 0 ,0
Exp/Cntr=0.5,0.3

Type RM Length L Ch R = 1 ,68294.69,365.8345,493.0584,410.2743
XS GIS Cut Line= 3
   1496244.79626   1142323.44455    1495916.6706   1142406.77789
   1495663.19783   1142476.22277
#Sta/Elev= 30
 -342.78 1053.18 -313.88    1044 -289.24 1034.25 -231.04 1005.77 -213.05 1002.89
 -199.63 1001.37 -153.92 1001.51 -113.07  998.48 -107.03   999.3  -102.7  997.99
  -93.47 1000.88  -85.58 1000.74  -81.25  999.04  -63.02  997.03  -51.34 1002.19
  -31.01 1002.28  -23.47 1001.81   -9.91  997.13   -7.92  995.48    -.15  993.91
    4.56  995.39    5.07  996.85    27.4  999.39   49.52 1003.52   57.07 1006.06
   63.27 1012.86    71.2 1018.09   79.82 1019.98  163.41 1022.06  258.58 1026.93
#Mann= 5 ,-1,0
 -342.78     .13       0 -213.05     .11       0 -153.92     .14       0
-7.92001     .05       04.559998     .14       0
#XS Ineff= 2 , 0
          -89.04 1006.07
Permanent Ineff=
       F       F
Bank Sta=-7.92,4.56
XS Rating Curve= 0 ,0
Exp/Cntr=0.3,0.1

Type RM Length L Ch R = 1 ,67801.64,77.53092,62.01023,57.99741
BEGIN DESCRIPTION:
TWE_36USX
END DESCRIPTION:
XS GIS Cut Line= 3
    1496275.6122   1142009.64206   1495775.63156   1142048.13386
   1495616.32251   1142065.45801
#Sta/Elev= 30
 -501.53  1032.9 -479.75 1031.08 -454.17 1027.01 -418.34 1019.56 -393.86 1013.32
 -379.23 1010.71 -360.25 1008.18 -332.69 1006.31 -328.83 1005.58  -312.7 1004.06
 -212.69 1001.28  -83.96  998.76  -38.26  999.09  -14.71  997.76   -9.91  995.63
   -7.92  993.98    -.15  992.41    3.54  993.05    4.56  993.89    5.07  995.35
    6.22  998.69   20.81  999.25   52.26 1001.77   57.21 1001.47   93.56 1005.47
  119.18 1010.04  134.07 1014.42  140.36 1015.46  153.65 1018.99  160.18 1019.91
#Mann= 6 ,-1,0
 -501.53    .135       0 -328.83     .11       0-83.9599     .14       0
-7.92001     .04       05.070007     .14       085.93002      .1       0
#XS Ineff= 2 , 0
         -163.31    1006
Permanent Ineff=
       F       F
Bank Sta=-7.92,5.07
XS Rating Curve= 0 ,0
Exp/Cntr=0.5,0.3

Type RM Length L Ch R = 1 ,67739.63,31.78791,36.5445,34.36387
BEGIN DESCRIPTION:
E. of Midway Rd (TWE_36) - US
END DESCRIPTION:
XS GIS Cut Line= 4
    1496301.3189   1141833.89272   1495892.33169    1141956.3353
   1495785.55807   1141987.40879   1495582.21621   1142019.05479
#Sta/Elev= 30
 -538.45 1012.29 -522.61 1011.18 -372.89 1006.92 -305.46 1005.29 -226.08  1003.4
 -211.26 1001.53 -196.19 1002.62 -154.62 1001.39 -150.36  1000.5 -126.79 1000.98
   -89.9  999.04  -81.14  999.56  -72.64  998.65  -53.14  998.75  -28.64  997.82
  -21.29  996.11  -16.03  993.77   -9.58  993.59   -8.08  992.98   -7.44  991.94
   -2.56  991.72    5.51   992.9    6.63  996.53   12.33   997.4   17.59  999.37
   87.66 1001.18  157.73 1005.76  187.41 1014.63  196.88 1018.11  205.46 1019.97
#Mann= 7 ,-1,0
 -538.45     .14       0 -372.89      .1       0 -305.46    .135       0
  -53.14     .14       0-9.58001     .04       0 5.51001     .14       0
86.16998      .1       0
#XS Ineff= 3 ,-1
 -170.37 -133.85 1001.37 -119.03  -82.13 1000.12      15  205.46    1000
Permanent Ineff=
       F       F       F
Bank Sta=-9.58,5.51
XS Rating Curve= 0 ,0
Exp/Cntr=0.5,0.3

Type RM Length L Ch R = 2 ,67721.01,,,
BEGIN DESCRIPTION:
E. of Midway Rd (TWE_36) - TOR
END DESCRIPTION:
Bridge Culvert--1,0,-1,-1, 0
Deck Dist Width WeirC Skew NumUp NumDn MinLoCord MaxHiCord MaxSubmerge Is_Ogee
6,25,2.6,0, 149, 149, 999.94, , 0.95, 0, 0,0,,
    -538 -496.37 -411.19 -407.24  -407.2 -406.95 -406.71 -405.54 -403.69 -402.78
 -402.41 -402.09 -398.69 -395.08 -394.95 -393.61    -393 -391.76 -388.86 -383.43
 -383.02 -381.47 -375.95 -373.95 -368.69  -368.6 -368.54 -364.64 -363.35 -363.31
 -360.83 -359.57 -356.95 -355.72 -350.93 -349.88 -349.71 -344.81 -344.22 -342.83
 -339.67 -338.71 -336.79 -336.21 -332.37 -331.45 -329.21 -327.54 -327.08  -326.2
 -322.84  -321.5 -319.06 -317.89 -312.25 -312.12  -312.1 -310.22 -307.61  -307.6
 -307.57 -302.17 -301.84 -299.58 -299.17 -295.51 -293.59 -293.47 -293.16 -291.17
 -287.19 -284.21 -283.08 -282.28 -279.08 -276.01 -274.62 -272.81 -271.89 -269.91
 -269.38 -269.07 -265.87 -259.88 -259.74 -259.67  -256.9 -256.57 -256.04  -254.6
 -253.68 -252.38 -248.83  -246.8 -243.24 -241.32 -240.22 -239.63 -238.77 -235.15
 -234.89 -233.22 -232.72 -231.69 -229.64 -227.01 -226.19 -225.53 -222.57 -220.95
 -219.61 -218.53 -215.12  -207.7 -204.57 -167.31 -147.75 -127.58 -108.64  -88.32
  -77.24   -66.6  -44.16  -23.79    1.74      55   69.58   88.33  112.42  135.79
  159.23  183.48  188.16  192.04   193.3  194.75  196.55   200.3  208.58  209.62
  210.14  213.13  213.56  214.26  216.71   218.2  218.82  220.67  221.01
 1012.43 1011.52  1008.4 1008.07 1008.06 1008.06 1008.05 1007.98 1007.78 1007.85
 1007.83 1007.78 1007.71 1007.63 1007.63 1007.48 1007.43  1007.4 1007.44 1007.37
 1007.35  1007.2 1006.99 1006.88 1006.92 1006.92 1006.91  1006.8 1006.76 1006.76
 1006.52 1006.44 1006.42 1006.43 1006.18 1006.14 1006.13 1006.05 1005.98 1005.97
 1005.94 1005.93 1005.82 1005.78 1005.71  1005.7 1005.71  1005.8 1005.79  1005.8
 1005.55 1005.63 1005.37 1005.31  1005.6 1005.61 1005.61 1005.37 1005.05 1005.04
 1005.04 1004.79 1004.77 1004.54 1004.52 1004.54 1004.57 1004.56 1004.53 1004.45
 1004.48 1004.35  1004.2 1004.13 1004.31 1004.04  1003.9 1003.98 1004.09 1003.75
 1003.69  1003.7 1003.98 1003.52 1003.52 1003.51 1003.63 1003.63 1003.59  1003.4
 1003.43 1003.36 1003.33 1003.37  1003.2 1003.15  1003.1 1003.13 1003.04 1002.66
 1002.69 1002.63 1002.59 1002.74 1002.66  1002.7 1002.62 1002.63 1002.56  1002.5
 1002.46 1002.43 1002.23 1002.02 1002.11 1001.51 1001.25 1000.96 1000.59 1000.14
 1000.05  999.96  999.92  999.94  999.94 1000.15 1000.13 1000.97    1002 1003.66
 1006.82 1011.44 1012.43 1013.09 1013.58 1013.86 1014.28 1015.31 1017.52 1017.86
 1017.95 1018.42  1018.5 1018.61 1019.09 1019.33 1019.47  1019.8 1019.87
                                                                                
                                                                                
                                                                                
                                                                                
                                                                                
                                                                                
                                                                                
                                                                                
                                                                                
                                                                                
                                                                                
                                                                                
                                                                                
                                                                                
                                                                        
    -538 -496.37 -411.19 -407.24  -407.2 -406.95 -406.71 -405.54 -403.69 -402.78
 -402.41 -402.09 -398.69 -395.08 -394.95 -393.61    -393 -391.76 -388.86 -383.43
 -383.02 -381.47 -375.95 -373.95 -368.69  -368.6 -368.54 -364.64 -363.35 -363.31
 -360.83 -359.57 -356.95 -355.72 -350.93 -349.88 -349.71 -344.81 -344.22 -342.83
 -339.67 -338.71 -336.79 -336.21 -332.37 -331.45 -329.21 -327.54 -327.08  -326.2
 -322.84  -321.5 -319.06 -317.89 -312.25 -312.12  -312.1 -310.22 -307.61  -307.6
 -307.57 -302.17 -301.84 -299.58 -299.17 -295.51 -293.59 -293.47 -293.16 -291.17
 -287.19 -284.21 -283.08 -282.28 -279.08 -276.01 -274.62 -272.81 -271.89 -269.91
 -269.38 -269.07 -265.87 -259.88 -259.74 -259.67  -256.9 -256.57 -256.04  -254.6
 -253.68 -252.38 -248.83  -246.8 -243.24 -241.32 -240.22 -239.63 -238.77 -235.15
 -234.89 -233.22 -232.72 -231.69 -229.64 -227.01 -226.19 -225.53 -222.57 -220.95
 -219.61 -218.53 -215.12  -207.7 -204.57 -167.31 -147.75 -127.58 -108.64  -88.32
  -77.24   -66.6  -44.16  -23.79    1.74      55   69.58   88.33  112.42  135.79
  159.23  183.48  188.16  192.04   193.3  194.75  196.55   200.3  208.58  209.62
  210.14  213.13  213.56  214.26  216.71   218.2  218.82  220.67  221.01
 1012.43 1011.52  1008.4 1008.07 1008.06 1008.06 1008.05 1007.98 1007.78 1007.85
 1007.83 1007.78 1007.71 1007.63 1007.63 1007.48 1007.43  1007.4 1007.44 1007.37
 1007.35  1007.2 1006.99 1006.88 1006.92 1006.92 1006.91  1006.8 1006.76 1006.76
 1006.52 1006.44 1006.42 1006.43 1006.18 1006.14 1006.13 1006.05 1005.98 1005.97
 1005.94 1005.93 1005.82 1005.78 1005.71  1005.7 1005.71  1005.8 1005.79  1005.8
 1005.55 1005.63 1005.37 1005.31  1005.6 1005.61 1005.61 1005.37 1005.05 1005.04
 1005.04 1004.79 1004.77 1004.54 1004.52 1004.54 1004.57 1004.56 1004.53 1004.45
 1004.48 1004.35  1004.2 1004.13 1004.31 1004.04  1003.9 1003.98 1004.09 1003.75
 1003.69  1003.7 1003.98 1003.52 1003.52 1003.51 1003.63 1003.63 1003.59  1003.4
 1003.43 1003.36 1003.33 1003.37  1003.2 1003.15  1003.1 1003.13 1003.04 1002.66
 1002.69 1002.63 1002.59 1002.74 1002.66  1002.7 1002.62 1002.63 1002.56  1002.5
 1002.46 1002.43 1002.23 1002.02 1002.11 1001.51 1001.25 1000.96 1000.59 1000.14
 1000.05  999.96  999.92  999.94  999.94 1000.15 1000.13 1000.97    1002 1003.66
 1006.82 1011.44 1012.43 1013.09 1013.58 1013.86 1014.28 1015.31 1017.52 1017.86
 1017.95 1018.42  1018.5 1018.61 1019.09 1019.33 1019.47  1019.8 1019.87
                                                                                
                                                                                
                                                                                
                                                                                
                                                                                
                                                                                
                                                                                
                                                                                
                                                                                
                                                                                
                                                                                
                                                                                
                                                                                
                                                                                
                                                                        
BR Coef=-1 ,-1 , 0 ,, 0 ,,,0.8,0,,0,
WSPro=,,,, 1 ,,,, 0 ,,,, 0 ,,,,-1 ,-1 ,-1 , 0 , 0 , 0 , 0 , 0
Culvert=1,7,7,25,0.024,0.9,1,2,3,990.07,1.74,989.75,1.74,Culvert #1  , 0 ,6
    1.74    1.74
BC Culvert Barrel=1,,0
Culvert Bottom n=0.024
BR U #Sta/Elev= 30
 -538.45 1012.29 -522.61 1011.18 -372.89 1006.92 -305.46 1005.29 -226.08  1003.4
 -211.26 1001.53 -196.19 1002.62 -154.62 1001.39 -150.36  1000.5 -126.79 1000.98
   -89.9  999.04  -81.14  999.56  -72.64  998.65  -53.14  998.75  -28.64  997.82
  -21.29  996.11  -16.03  993.77   -9.58  993.59   -7.44  991.94   -2.56  991.72
    -.83  990.06    4.71  990.06    5.51   992.9    6.63  996.53   12.33   997.4
   17.59  999.37   86.17 1001.13  157.73 1005.76  196.88 1018.11  205.46 1019.97
BR U #Mann= 7
 -538.45     .14 -372.89     .08 -305.46    .135  -53.14     .14   -9.58    .045
    5.51     .14   86.17     .08
BR D #Sta/Elev= 30
 -503.05 1013.52 -432.55 1009.48 -376.08 1007.83 -355.02 1006.49 -292.78 1005.04
 -208.27 1002.22 -135.18 1000.83  -97.39  999.45   -43.4  999.28  -30.37  998.76
  -18.43  998.92  -11.04  995.51  -10.05  995.51   -8.08  992.44   -7.44   991.4
   -2.56  991.18     .12  989.74    4.71   990.1    5.51  992.36    7.81  993.64
   16.69  995.61   20.69  997.21   22.65  996.87   29.01  998.73   69.27   999.8
  105.15 1000.71  150.42 1004.13   185.4 1009.21   205.3 1013.21  221.05  1017.4
BR D #Mann= 6
 -503.05     .14 -355.02     .08   -43.4     .14   -8.08    .045    5.51     .14
   69.27     .08
BC Design=,, 0 ,, 0 ,,,,,,
BC Use User HTab Curves=0
BC User HTab FreeFlow(D)= 0

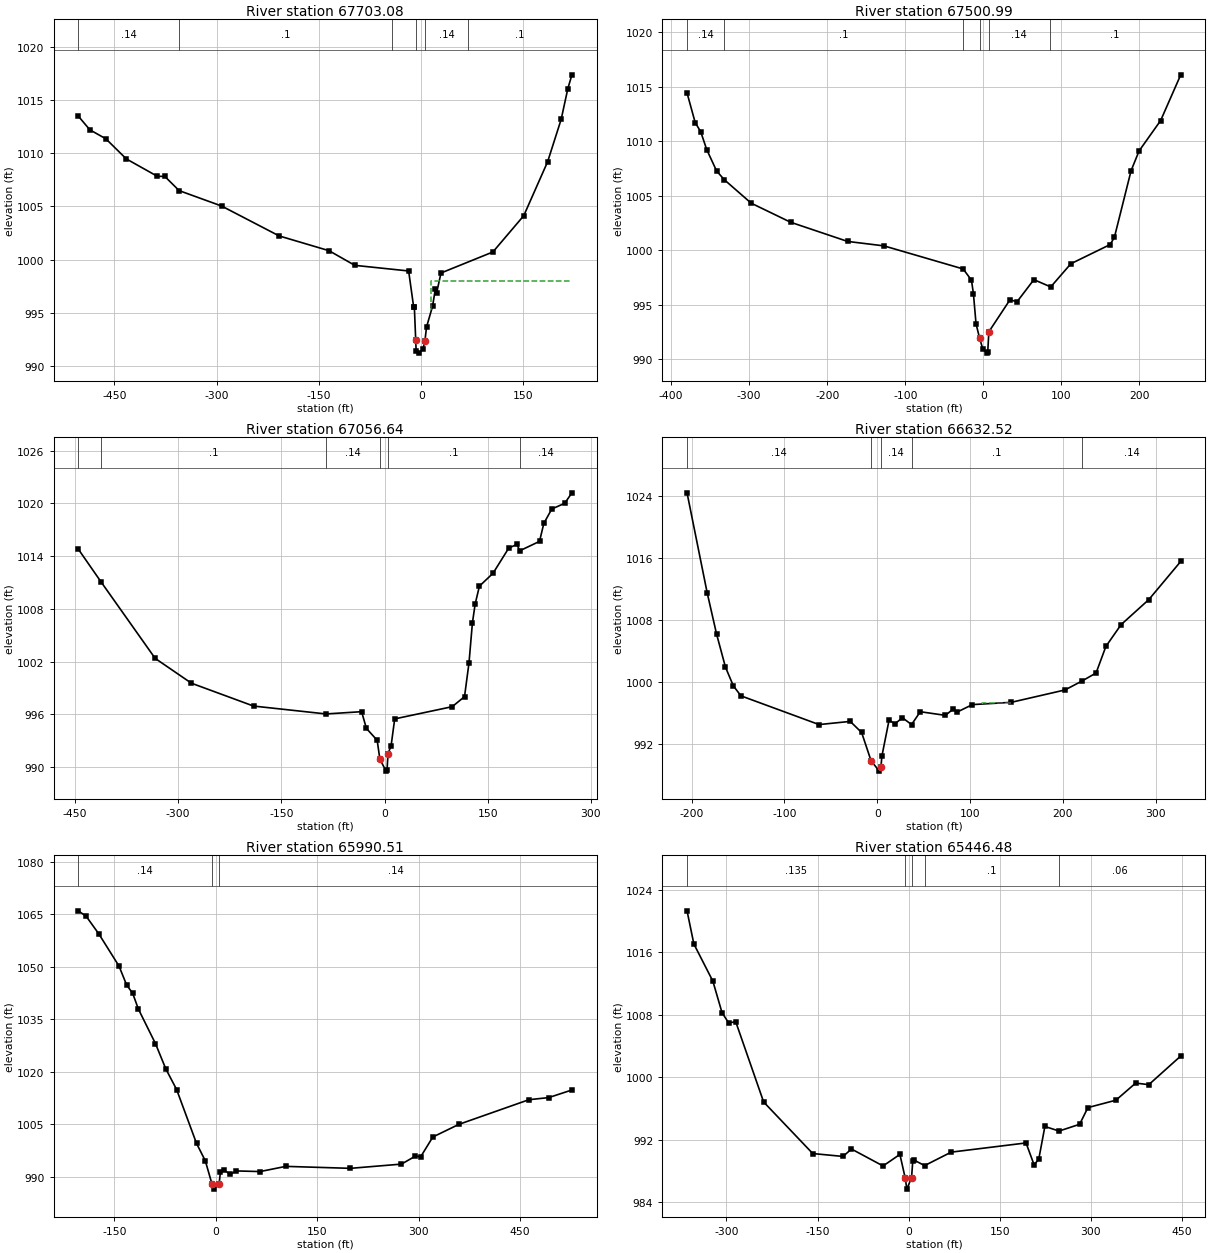
Type RM Length L Ch R = 1 ,67703.08,180.2184,202.094,165.4561
BEGIN DESCRIPTION:
E. of Midway Rd (TWE_36) - DS
END DESCRIPTION:
XS GIS Cut Line= 5
   1496274.38615   1141812.34613   1495885.20899   1141926.81004
   1495789.59777   1141951.72277   1495728.99934   1141961.82251
   1495573.46325   1141990.77559
#Sta/Elev= 30
 -503.05 1013.52 -486.03 1012.22 -462.46 1011.37 -432.55 1009.48 -387.01 1007.84
 -376.08 1007.83 -355.02 1006.49 -292.78 1005.04 -208.27 1002.22 -135.18 1000.83
  -97.39  999.45  -18.43  998.92  -11.04  995.51  -10.05  995.51   -8.08  992.44
   -7.44   991.4   -2.56  991.18    2.63  991.57    5.51  992.36    7.81  993.64
   16.69  995.61   20.69  997.21   22.65  996.87   29.01  998.73  105.15 1000.71
  150.42 1004.13   185.4 1009.21   205.3 1013.21  215.08 1016.11  221.05  1017.4
#Mann= 6 ,-1,0
 -503.05     .14       0 -355.02      .1       0-43.3999     .14       0
-8.07998     .04       0 5.51001     .14       069.27002      .1       0
#XS Ineff= 2 ,-1
 -503.05     -20     998      15  221.05     998
Permanent Ineff=
       F       F
Bank Sta=-8.08,5.51
XS Rating Curve= 0 ,0
Exp/Cntr=0.5,0.3

Type RM Length L Ch R = 1 ,67500.99,292.445,444.347,343.7893
XS GIS Cut Line= 3
   1496125.65879   1141632.59547   1495774.25197   1141773.15814
   1495537.77592   1141865.76444
#Sta/Elev= 30
 -379.56 1014.44 -369.14 1011.72 -362.02 1010.87 -354.33 1009.23 -341.66 1007.27
 -331.89 1006.47 -297.33 1004.31 -246.84 1002.56 -173.95  1000.8 -127.27 1000.39
  -25.82  998.27   -15.2  997.24  -12.68     996   -9.34  993.23   -4.79  991.92
-.849999  990.96    4.19  990.54    5.65  990.64    7.07   992.5   34.15  995.44
    43.2  995.26   64.77  997.29   86.36  996.62  112.12  998.75  162.42 1000.51
  167.88 1001.17  189.29  1007.3   199.6 1009.12  227.13  1011.9  252.88  1016.1
#Mann= 6 ,-1,0
 -379.56     .14       0 -331.89      .1       0  -25.82     .14       0
   -4.79     .04       07.070007     .14       084.79001      .1       0
Bank Sta=-4.79,7.07
XS Rating Curve= 0 ,0
Exp/Cntr=0.3,0.1

Type RM Length L Ch R = 1 ,67056.64,396.0011,424.119,307.9694
XS GIS Cut Line= 3
   1496075.30807   1141470.36122   1495630.86253   1141482.51378
   1495358.29265   1141492.93077
#Sta/Elev= 30
 -445.06  1014.8 -411.89 1011.06 -333.23 1002.36 -280.59  999.54 -190.31  996.94
     -85996.0433  -33.28   996.3  -26.34   994.4  -10.67  993.05   -6.79  990.92
    2.19  989.54    3.65  989.64    5.07   991.5    9.61  992.45    14.8  995.48
   98.38  996.87  116.26  998.01  122.78 1001.87  127.69 1006.38  131.66 1008.52
   137.9 1010.58  157.66 1012.04  180.48  1014.9  192.41 1015.33  196.431014.597
  225.25 1015.67  231.48 1017.71  243.06 1019.35  261.82    1020  272.32 1021.19
#Mann= 6 ,-1,0
 -445.06     .14       0 -411.89      .1       0     -85     .14       0
   -6.79     .04       05.070007      .1       0  196.43     .14       0
Bank Sta=-6.79,5.07
XS Rating Curve= 0 ,0
Exp/Cntr=0.3,0.1

Type RM Length L Ch R = 1 ,66632.52,607.0123,642.0161,582.5013
BEGIN DESCRIPTION:
TWE_35X
END DESCRIPTION:
XS GIS Cut Line= 5
   1495705.55545   1141036.35564    1495595.7372   1141105.04823
   1495544.21752   1141136.68307   1495531.21293   1141143.86713
   1495285.37566      1141359.25
#Sta/Elev= 30
 -204.82 1024.47 -183.14 1011.57 -172.98 1006.22 -163.42 1001.96 -154.94  999.55
 -146.76  998.26  -62.64  994.55  -29.07  994.96   -16.8  993.53   -6.67  989.89
    2.19  988.54    4.01  989.11    5.07   990.5   12.77  995.13   19.04  994.65
   27.19  995.43   36.97  994.55   46.38  996.21   73.38  995.74   81.94  996.56
   85.81  996.15   102.5  997.13  144.28  997.42   202.2  999.02  220.65 1000.18
   235.7 1001.21  246.27 1004.64  262.63 1007.45  292.45 1010.68  326.87 1015.61
#Mann= 5 ,-1,0
 -204.82     .14       0-6.66998     .04       04.009995     .14       0
   36.97      .1       0  220.65     .14       0
#XS Ineff= 1 ,-1
  112.99  145.25  997.31
Permanent Ineff=
       F
Bank Sta=-6.67,4.01
XS Rating Curve= 0 ,0
Exp/Cntr=0.3,0.1

Type RM Length L Ch R = 1 ,65990.51,456.5038,544.0231,484.8703
XS GIS Cut Line= 3
   1495230.22933   1140598.73163   1495096.54823    1140748.0374
   1494747.58924    1141147.3435
#Sta/Elev= 30
 -203.64 1065.92 -191.97 1064.39 -173.22 1059.35 -143.25 1050.12  -132.1 1044.78
    -123 1042.34 -114.68 1037.88   -89.3 1027.98  -74.06 1020.79  -57.99 1014.85
  -28.56  999.48  -15.54   994.5   -5.62  987.84   -2.86  986.41    4.88   987.9
    6.82  991.28   11.83  991.91   21.62  990.61   30.11  991.61   65.59  991.43
  103.58  992.91  199.24  992.35  274.77  993.56  295.12  995.81  303.39   995.7
  321.18  1001.3  359.83 1004.92  463.44 1011.96  492.71 1012.56  527.07 1014.74
#Mann= 3 ,-1,0
 -203.64     .14       0-5.61999     .04       04.880005     .14       0
Bank Sta=-5.62,4.88
XS Rating Curve= 0 ,0
Exp/Cntr=0.3,0.1

Type RM Length L Ch R = 1 ,65446.48,304.5831,406.3046,353.6302
XS GIS Cut Line= 3
   1495002.60171   1140238.58005   1494720.80873   1140467.92552
   1494376.79035   1140757.71916
#Sta/Elev= 30
 -364.93 1021.33 -353.67 1017.08 -322.36 1012.31 -307.28 1008.27 -296.23 1006.95
 -284.79 1007.13 -238.77  996.83 -157.87  990.22 -108.02  989.85  -94.08   990.8
  -42.05  988.63  -14.31  990.11   -5.62  987.09   -2.86  985.66    4.88  987.15
    6.89  989.28    8.27  989.41   26.38988.6756   70.12   990.4  193.44  991.58
  206.65  988.78  214.36  989.49  224.46  993.69  247.88993.1054  281.65  993.97
  295.35  996.11  341.46  997.06  373.99  999.25  395.62  999.05  448.21 1002.72
#Mann= 5 ,-1,0
 -364.93    .135       0-5.61999     .04       04.880005     .13       0
   26.38      .1       0  247.88     .06       0
Bank Sta=-5.62,4.88
XS Rating Curve= 0 ,0
Exp/Cntr=0.3,0.1

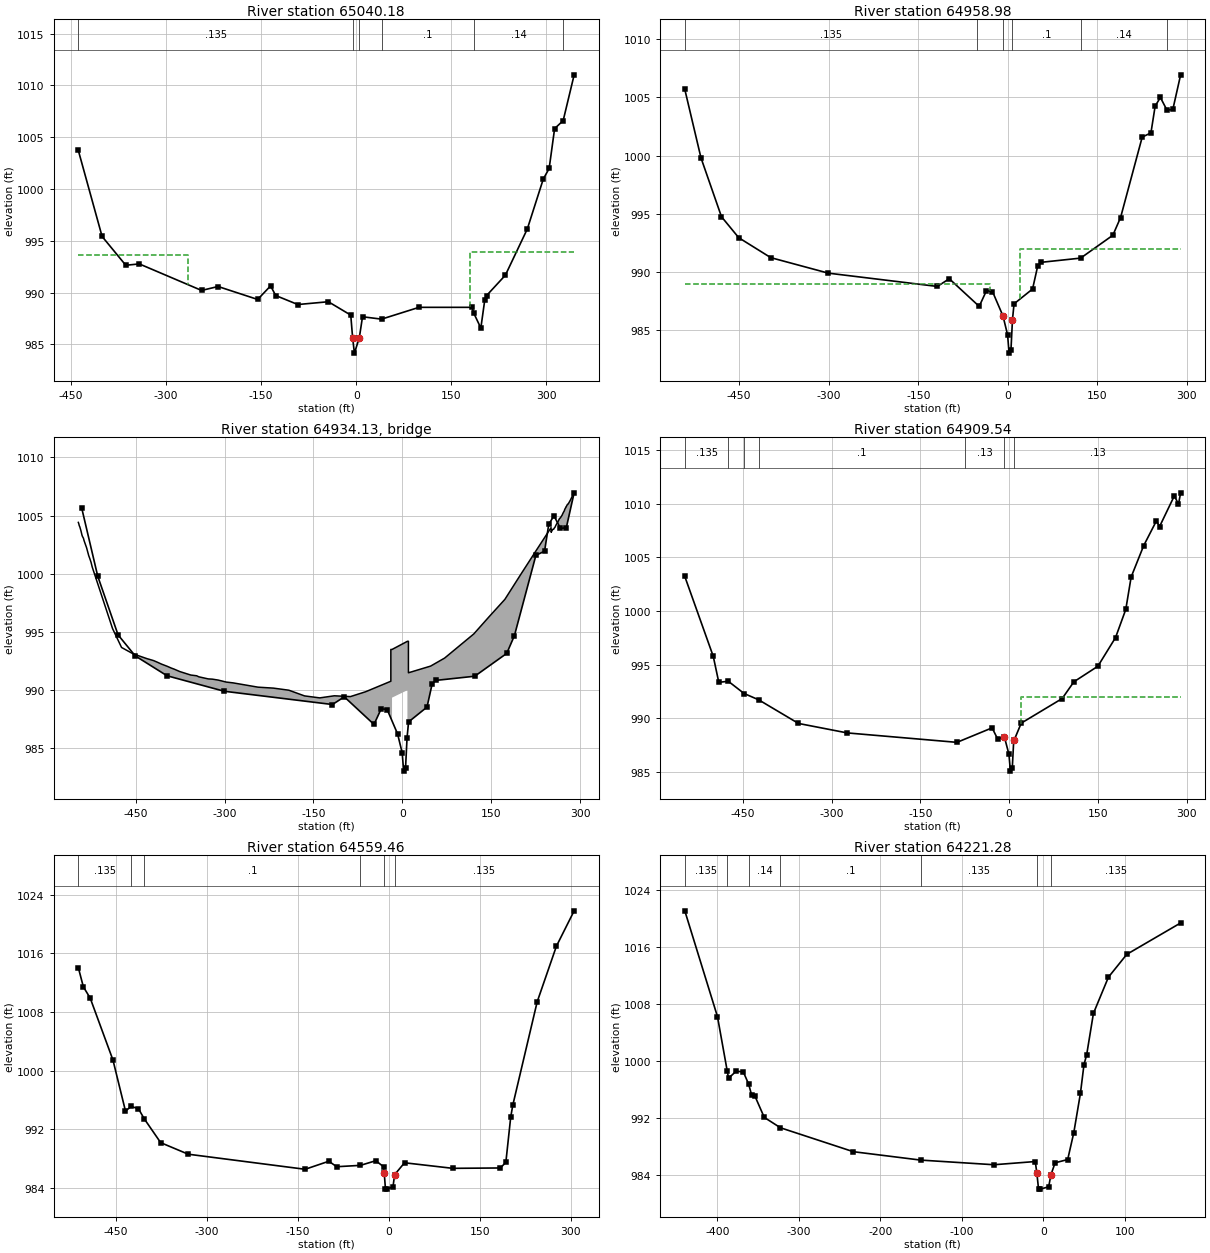
Type RM Length L Ch R = 1 ,65040.18,35.51299,81.20195,61.46384
BEGIN DESCRIPTION:
TWE_34USX
END DESCRIPTION:
XS GIS Cut Line= 4
   1494908.63911   1140071.05282   1494541.28051    1140195.3481
   1494498.83563   1140223.13156   1494204.29757   1140400.56759
#Sta/Elev= 30
 -438.52 1003.72 -401.03  995.42 -363.64  992.64 -342.29  992.77 -244.04  990.21
    -218  990.59 -155.56  989.34 -135.13  990.65 -127.08  989.72  -92.17  988.85
  -44.01  989.12   -8.64  987.83   -5.62  985.59   -2.86  984.16    4.88  985.65
    9.92  987.67   39.94  987.44   99.12  988.58  182.89  988.58  185.38  988.03
  196.63  986.58  202.87  989.31  205.73  989.72  235.33  991.68  269.95  996.14
  295.21 1000.97  304.43 1001.98  313.04 1005.83  326.54  1006.6  343.89 1011.02
#Mann= 6 ,-1,0
 -438.52    .135       0-5.61999     .04       04.880005     .13       0
   39.94      .1       0  185.38     .14       0  326.54      .1       0
#XS Ineff= 2 , 0
         -265.47  993.63   178.9          993.91
Permanent Ineff=
       F       F
Bank Sta=-5.62,4.88
XS Rating Curve= 0 ,0
Exp/Cntr=0.5,0.3

Type RM Length L Ch R = 1 ,64958.98,48.1625,49.4349,49.77205
BEGIN DESCRIPTION:
Tater Hill Mountain Rd (TWE_34) - US
END DESCRIPTION:
XS GIS Cut Line= 3
   1494928.16207   1140005.96654     1494427.646   1140206.32808
   1494156.11417   1140313.08399
#Sta/Elev= 30
 -541.18 1005.67 -514.07   999.8 -479.72  994.75 -450.79  992.95 -397.13  991.24
 -300.71  989.91 -117.99  988.77  -97.96  989.43  -47.82  987.06  -35.63  988.41
  -25.54  988.33   -7.99  986.24    -.26  984.62    2.21  983.05    5.39  983.32
    7.94  985.93   10.58  987.28   41.61  988.55   50.38  990.56    56.2  990.84
  122.18   991.2  176.14  993.16  189.09  994.68  225.34 1001.58  239.97 1001.94
  247.04 1004.24  255.82 1004.98  266.81 1003.89  276.66 1003.95  289.72 1006.92
#Mann= 6 ,-1,0
 -541.18    .135       0-52.2999      .1       0-7.98999     .04       0
7.940002      .1       0  122.18     .14       0  266.81      .1       0
#XS Ineff= 2 , 0
             -30     989      20             992
Permanent Ineff=
       F       F
Bank Sta=-7.99,7.94
XS Rating Curve= 0 ,0
Exp/Cntr=0.5,0.3

Type RM Length L Ch R = 3 ,64934.13,,,
BEGIN DESCRIPTION:
Tater Hill Mountain Rd (TWE_34) - TOR
END DESCRIPTION:
Bridge Culvert--1,0,-1,-1, 0
Deck Dist Width WeirC Skew NumUp NumDn MinLoCord MaxHiCord MaxSubmerge Is_Ogee
11.15,27.4,2.6,0, 94, 94, 989.34, , 0.95, 0, 0,0,,
 -546.76 -545.95  -545.1 -544.55 -544.05 -542.39  -540.6 -539.85 -538.13 -537.16
 -535.26 -532.87 -529.52 -529.28 -527.52 -525.34 -523.28    -489 -473.84 -454.19
 -430.41 -427.48 -419.64 -413.23 -406.36 -397.13 -389.85 -385.12 -375.47 -356.87
 -347.12 -343.48  -334.6 -327.55 -320.63 -310.81 -297.34 -285.71 -243.43  -217.8
 -191.58    -165 -139.38 -114.76  -87.68  -61.89  -19.41  -19.41  -17.41    8.57
   10.27   10.27   10.55   47.67   71.34   89.86   120.5  146.19  172.99  199.51
  207.88  226.01  250.95  251.15  253.29  253.59  254.64  255.29  256.14  257.54
  259.25  261.16  262.55  264.78  265.26  266.61  269.54  271.23   273.1  273.44
  273.94  276.27  276.34   276.4  278.63  279.39  280.85  283.71  284.18  286.24
  287.66  288.87  289.67  289.92
 1004.41 1004.29 1004.11 1004.07 1003.99  1003.7 1003.32 1003.21 1003.05 1002.86
 1002.58 1002.24 1001.61 1001.56 1001.32 1000.99 1000.57  995.29  993.67  993.12
   992.7  992.66  992.54   992.4  992.24  992.06   991.9  991.81   991.6   991.3
  991.24  991.15  991.05  990.97  990.95  990.87   990.7  990.63  990.26  990.18
     990  989.51  989.34  989.52  989.45  989.87  990.77   993.5   993.5   994.2
   994.2   991.5   991.5  992.07  992.76  993.54  994.83   996.3   997.8  999.92
 1000.58 1002.01 1003.96 1003.56 1003.79 1003.81 1003.81 1003.82 1003.91 1003.99
 1004.18 1004.35 1004.46  1004.7 1004.74  1004.8 1005.03 1005.22 1005.39 1005.42
 1005.52 1005.74 1005.74 1005.75 1005.96 1005.97 1006.08 1006.34 1006.39 1006.61
  1006.8 1006.93 1006.94 1006.95
                                                                                
                                                                                
                                                                                
                                                                                
                                                                  989.36     990
                                                                                
                                                                                
                                                                                
                                                                                
                                
 -546.76 -545.95  -545.1 -544.55 -544.05 -542.39  -540.6 -539.85 -538.13 -537.16
 -535.26 -532.87 -529.52 -529.28 -527.52 -525.34 -523.28    -489 -473.84 -454.19
 -430.41 -427.48 -419.64 -413.23 -406.36 -397.13 -389.85 -385.12 -375.47 -356.87
 -347.12 -343.48  -334.6 -327.55 -320.63 -310.81 -297.34 -285.71 -243.43  -217.8
 -191.58    -165 -139.38 -114.76  -87.68  -61.89  -19.41  -19.41  -17.41    8.57
   10.27   10.27   10.55   47.67   71.34   89.86   120.5  146.19  172.99  199.51
  207.88  226.01  250.95  251.15  253.29  253.59  254.64  255.29  256.14  257.54
  259.25  261.16  262.55  264.78  265.26  266.61  269.54  271.23   273.1  273.44
  273.94  276.27  276.34   276.4  278.63  279.39  280.85  283.71  284.18  286.24
  287.66  288.87  289.67  289.92
 1004.41 1004.29 1004.11 1004.07 1003.99  1003.7 1003.32 1003.21 1003.05 1002.86
 1002.58 1002.24 1001.61 1001.56 1001.32 1000.99 1000.57  995.29  993.67  993.12
   992.7  992.66  992.54   992.4  992.24  992.06   991.9  991.81   991.6   991.3
  991.24  991.15  991.05  990.97  990.95  990.87   990.7  990.63  990.26  990.18
     990  989.51  989.34  989.52  989.45  989.87  990.77   993.5   993.5   994.2
   994.2   991.5   991.5  992.07  992.76  993.54  994.83   996.3   997.8  999.92
 1000.58 1002.01 1003.96 1003.56 1003.79 1003.81 1003.81 1003.82 1003.91 1003.99
 1004.18 1004.35 1004.46  1004.7 1004.74  1004.8 1005.03 1005.22 1005.39 1005.42
 1005.52 1005.74 1005.74 1005.75 1005.96 1005.97 1006.08 1006.34 1006.39 1006.61
  1006.8 1006.93 1006.94 1006.95
                                                                                
                                                                                
                                                                                
                                                                                
                                                                  989.36     990
                                                                                
                                                                                
                                                                                
                                                                                
                                
BR Coef=-1 ,-1 , 0 ,, 0 ,,,0.8,0,1.2,0,
WSPro=,,,, 1 ,,,, 0 ,,,, 0 ,,,,-1 ,-1 ,-1 , 0 , 0 , 0 , 0 , 0
BC Design=,, 0 ,, 0 ,,,,,,
BC Use User HTab Curves=0
BC User HTab FreeFlow(D)= 0

Type RM Length L Ch R = 1 ,64909.54,244.0514,350.0783,339.4108
BEGIN DESCRIPTION:
Tater Hill Mountain Rd (TWE_34) - DS
END DESCRIPTION:
XS GIS Cut Line= 3
    1494916.5584   1139960.32448    1494408.3061   1140161.45932
   1494136.00066   1140265.89469
#Sta/Elev= 30
 -548.25 1003.22 -500.14  995.78 -490.78  993.36 -474.72  993.46 -448.03  992.32
 -423.28  991.73 -356.03  989.53 -273.79  988.65   -88.1  987.77  -28.72  989.12
   -19.5   988.1   -7.99  988.28    -.26  986.66    2.21  985.09    5.39  985.36
    7.83  987.94    8.73     988   20.54  989.56   89.74  991.85  109.53  993.41
  150.11  994.86  179.98  997.53  197.28 1000.15  206.36 1003.17  227.54 1006.09
  249.09  1008.4  254.35 1007.86  279.38 1010.73   286.4 1009.95     290 1011.01
#Mann= 7 ,-1,0
 -548.25    .135       0 -474.72     .06       0 -448.03     .06       0
 -423.28      .1       0-74.7699     .13       0-7.98999     .04       0
 8.72998     .13       0
#XS Ineff= 2 , 0
             -30     989      20             992
Permanent Ineff=
       F       F
Bank Sta=-7.99,8.73
XS Rating Curve= 0 ,0
Exp/Cntr=0.5,0.3

Type RM Length L Ch R = 1 ,64559.46,326.2435,338.1874,332.4392
XS GIS Cut Line= 3
   1494955.51411   1139886.15682   1494446.39829   1139848.39633
   1494140.40814   1139821.05217
#Sta/Elev= 30
  -512.4 1014.05 -504.11 1011.43 -492.78 1009.88  -455.3 1001.43 -434.64  994.46
 -425.37995.0964  -413.2  994.78 -403.95993.4351 -376.61  990.15 -331.21  988.57
 -138.39  986.51  -99.19  987.61  -86.37  986.86   -47.1987.0467  -21.81  987.68
    -8.9  986.85   -7.92  986.02   -5.86  983.81   -3.59   983.8    6.57  984.13
    9.25  985.78   25.56   987.4  105.07  986.64   183.5  986.69  192.67  987.45
  200.68  993.63   204.1  995.26  244.33 1009.38  276.11 1016.99  305.33 1021.81
#Mann= 6 ,-1,0
  -512.4    .135       0 -425.37     .06       0 -403.95      .1       0
   -47.1    .135       0-7.92001     .04       0    9.25    .135       0
Bank Sta=-7.92,9.25
XS Rating Curve= 0 ,0
Exp/Cntr=0.3,0.1

Type RM Length L Ch R = 1 ,64221.28,399.8014,479.3083,372.4897
XS GIS Cut Line= 3
   1494915.14928   1139558.03117   1494480.25262   1139524.17684
    1494308.3773    1139518.9685
#Sta/Elev= 30
 -439.77 1021.03 -399.69 1006.19  -387.7998.5498 -386.14  997.55 -376.76  998.54
    -368  998.44 -361.45996.7295  -357.7  995.15 -353.88  995.08  -342.3  992.06
 -322.42990.6046 -233.05  987.25 -150.52986.0724  -60.55  985.42    -9.9  985.87
   -7.92  984.22   -5.86982.0099   -3.59     982    6.57  982.33    9.25  983.98
   14.41  985.69   29.87  986.15   37.35  989.91    45.5  995.43   49.85  999.45
   53.19 1000.87   61.45 1006.65   79.86 1011.73  102.39 1014.93   168.4 1019.33
#Mann= 7 ,-1,0
 -439.77    .135       0  -387.7     .06       0 -361.45     .14       0
 -322.42      .1       0 -150.52    .135       0-7.92001     .04       0
    9.25    .135       0
Bank Sta=-7.92,9.25
XS Rating Curve= 0 ,0
Exp/Cntr=0.3,0.1

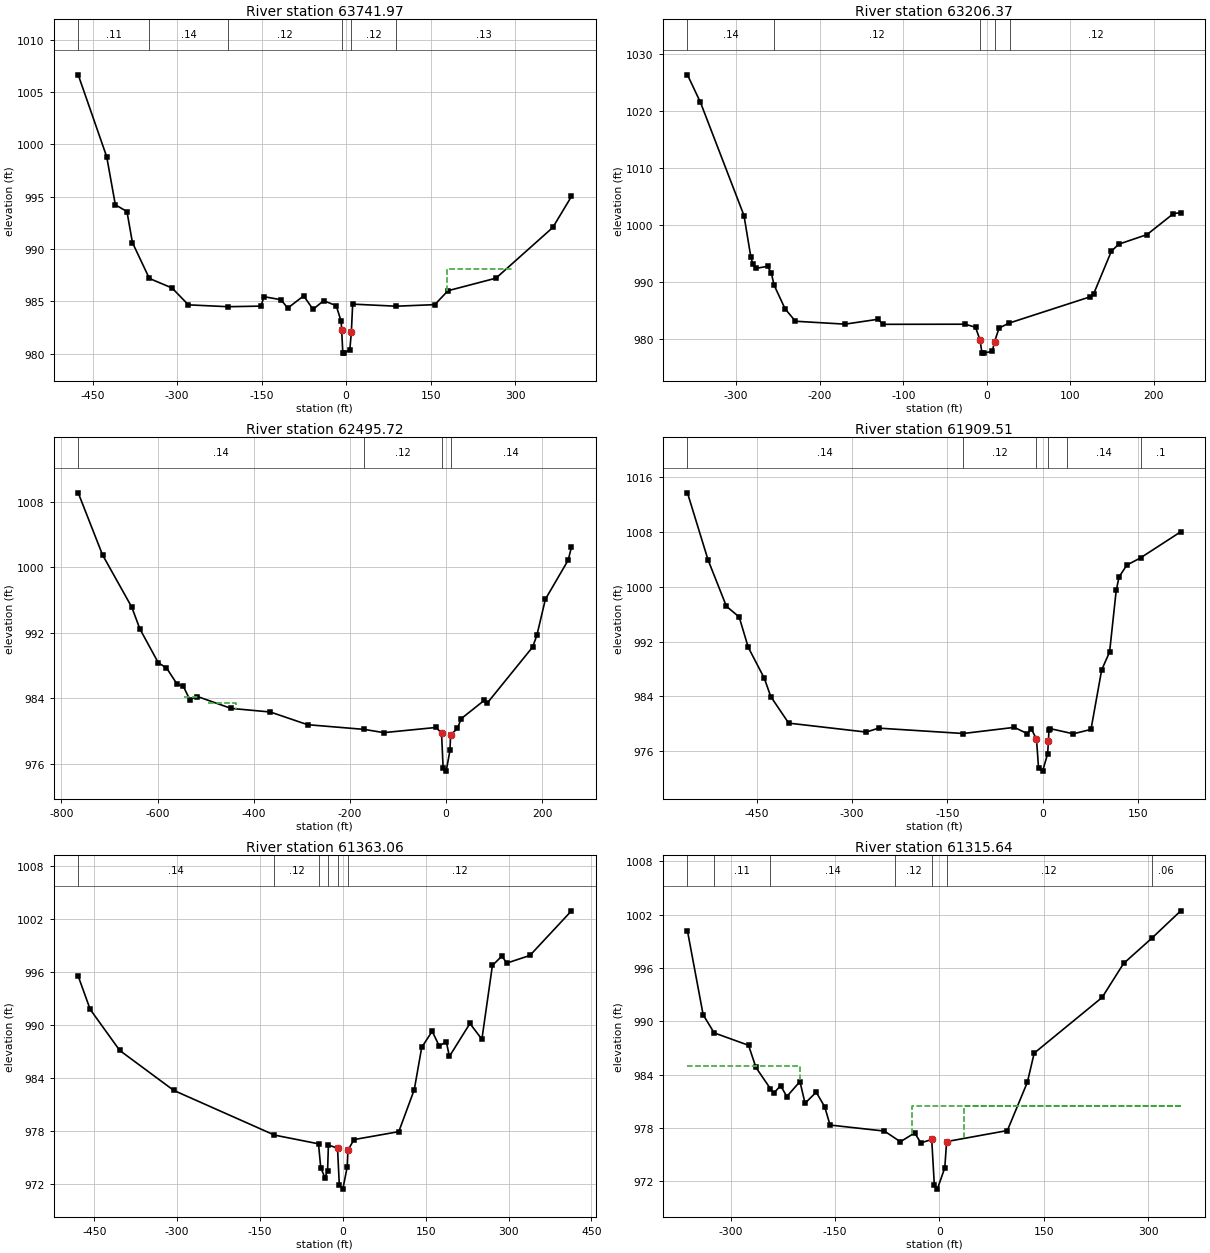
Type RM Length L Ch R = 1 ,63741.97,414.8988,535.5957,451.0252
XS GIS Cut Line= 3
   1494924.26411   1139068.44685   1494457.15322   1139147.25558
   1494060.98097   1139215.58268
#Sta/Elev= 30
 -475.64 1006.63 -425.01   998.8 -409.71  994.22 -389.08  993.57  -379.4  990.61
 -349.35987.1844 -309.01  986.27 -279.99  984.66 -209.88984.4842 -151.29  984.54
 -145.71  985.44 -115.67  985.15 -103.69  984.35  -75.35  985.52  -58.78  984.23
  -39.85  985.06   -17.6  984.58    -8.9   983.1   -7.92  982.27   -5.86  980.06
   -3.59  980.05    6.57  980.38    9.25  982.03   11.61  984.73   88.69984.5318
   157.4  984.68  180.78  986.01  266.03  987.21  366.89  992.05   400.1  995.02
#Mann= 6 ,-1,0
 -475.64     .11       0 -349.35     .14       0 -209.88     .12       0
-7.92001     .04       0    9.25     .12       0   88.69     .13       0
#XS Ineff= 1 ,-1
  179.65  295.77  988.05
Permanent Ineff=
       F
Bank Sta=-7.92,9.25
XS Rating Curve= 0 ,0
Exp/Cntr=0.3,0.1

Type RM Length L Ch R = 1 ,63206.37,683.8718,710.6496,611.7475
BEGIN DESCRIPTION:
TWE_33X
END DESCRIPTION:
XS GIS Cut Line= 5
   1494752.55512    1138692.6063   1494461.53675   1138724.07907
   1494396.40617   1138716.21424   1494327.71129   1138708.10335
    1494165.5315   1138691.52133
#Sta/Elev= 30
 -358.32 1026.38 -342.77 1021.55 -290.65 1001.71 -282.43  994.42 -279.93  993.14
 -276.56  992.44 -262.46  992.81 -257.93  991.64 -254.67  989.53 -241.47  985.36
 -229.09  983.18 -169.67  982.67    -130  983.53 -124.37  982.64  -25.97  982.66
  -13.47  982.13   -7.92  979.81   -5.86   977.6   -3.59  977.59    6.57  977.92
    9.25  979.57   14.72  981.99   26.61  982.85  123.71  987.46  128.01  988.01
  149.03  995.42  157.77  996.68  191.79  998.37  223.47 1002.05  232.19 1002.22
#Mann= 5 ,-1,0
 -358.32     .14       0 -254.67     .12       0-7.92001     .04       0
    9.25     .12       028.20001     .12       0
Bank Sta=-7.92,9.25
XS Rating Curve= 0 ,0
Exp/Cntr=0.3,0.1

Type RM Length L Ch R = 1 ,62495.72,535.3537,586.2144,526.637
XS GIS Cut Line= 3
   1494925.29856   1137786.57152   1494243.00558   1138119.90551
   1493998.21325   1138224.07251
#Sta/Elev= 30
 -764.85 1009.08 -714.35 1001.51  -653.5  995.12 -636.71  992.47 -598.27  988.32
 -581.37  987.71  -559.1   985.7 -546.46  985.47 -532.98  983.84 -517.08  984.21
  -447.1  982.76 -365.55  982.32 -288.16  980.77 -170.05980.1938 -129.68   979.8
  -21.24  980.43   -9.61  979.76   -6.34  975.54     .01   975.1    7.93  977.63
    9.21  979.51    23.5  980.32   31.22   981.5   79.59  983.76   85.72  983.43
  179.89  990.26  188.63   991.7   206.3  996.09  253.64 1000.86  260.55 1002.47
#Mann= 4 ,-1,0
 -764.85     .14       0 -170.05     .12       0-9.60998     .04       0
9.210022     .14       0
#XS Ineff= 2 ,-1
 -543.98 -516.77  984.21 -494.19 -437.29  983.36
Permanent Ineff=
       F       F
Bank Sta=-9.61,9.21
XS Rating Curve= 0 ,0
Exp/Cntr=0.3,0.1

Type RM Length L Ch R = 1 ,61909.51,384.125,546.4482,467.8672
XS GIS Cut Line= 3
   1494607.58957   1137362.09154   1494103.69948   1137612.11844
   1493912.27592   1137708.44619
#Sta/Elev= 30
 -559.24 1013.74 -526.83 1003.95 -497.91  997.17 -477.85  995.62 -463.52  991.18
 -438.23  986.66 -428.06  983.99 -399.87  980.11 -277.65   978.8  -258.3  979.38
 -125.01978.5942  -44.54  979.49  -23.91  978.57  -17.78  979.28   -9.61  977.76
   -6.34  973.54     .01   973.1    7.93  975.63    9.21  977.51   10.07  979.17
   12.25   979.3   48.24  978.55    76.2  979.19   93.02  987.88  105.51   990.5
  115.93  999.49  120.42 1001.46   132.7 1003.19   154.21004.242  217.56 1008.05
#Mann= 6 ,-1,0
 -559.24     .14       0 -125.01     .12       0-9.60998     .04       0
9.210022     .12       039.03003     .14       0   154.2      .1       0
Bank Sta=-9.61,9.21
XS Rating Curve= 0 ,0
Exp/Cntr=0.3,0.1

Type RM Length L Ch R = 1 ,61363.06,113.0541,47.42634,15.37912
BEGIN DESCRIPTION:
TWE_32USX
END DESCRIPTION:
XS GIS Cut Line= 6
   1494472.47474   1137136.85072   1494079.67881   1137171.57316
   1493944.05184   1137176.11975   1493876.87697   1137238.33924
   1493843.28904   1137330.29199   1493842.18799   1137503.73556
#Sta/Elev= 30
 -479.03  995.53 -457.36  991.76 -403.83   987.1  -306.1  982.57 -123.74   977.5
  -44.04  976.51     -40  973.81  -32.47  972.68  -27.62  973.43   -26.1  976.36
   -9.61  976.03   -6.34  971.81     .01  971.37    7.93   973.9    9.21  975.78
    20.2  976.99  101.28  977.89  129.32  982.65  142.79  987.45  161.77  989.28
  174.39  987.62  187.34  988.09  192.88  986.42  230.07  990.16  251.72  988.37
  270.79  996.75  287.91   997.8  296.84  997.01  338.71  997.88  413.94 1002.94
#Mann= 6 ,-1,0
 -479.03     .14       0 -123.74     .12       0  -44.04    .045       0
   -26.1     .12       0-9.60998     .04       09.209991     .12       0
Bank Sta=-9.61,9.21
XS Rating Curve= 0 ,0
Exp/Cntr=0.5,0.3

Type RM Length L Ch R = 1 ,61315.64,58.08566,71.82238,65.56407
BEGIN DESCRIPTION:
Ponderosa Rd (TWE_32) - US
END DESCRIPTION:
XS GIS Cut Line= 6
   1494370.79232   1136888.40617   1493919.27428   1137183.82841
   1493869.16831   1137236.13681   1493848.24475   1137276.33169
   1493831.72638   1137341.30413    1493831.7792   1137482.21719
#Sta/Elev= 30
 -361.86 1000.19-339.301  990.74-323.516  988.71 -274.08  987.31-263.472  984.82
-242.854  982.45-238.021   981.9 -228.06  982.78-219.082  981.55-200.193  983.23
-192.927  980.79-176.855  982.04-164.527  980.37-157.023  978.34 -78.827  977.66
 -55.948  976.46 -35.404  977.45 -26.467  976.33 -10.887  976.72  -7.176  971.63
  -2.818  971.13   7.888  973.53  10.526  976.48   97.79  977.72 126.526  983.15
  136.34  986.43 234.015   992.7 264.807  996.52 305.208  999.35 346.935 1002.44
#Mann= 7 ,-1,0
 -361.86     .14       0-323.516     .11       0-242.854     .14       0
-63.4599     .12       0-10.8869     .04       0  10.526     .12       0
 305.208     .06       0
#XS Ineff= 3 ,-1
 -361.86 -200.19     985     -39    -200   980.5      35 346.935   980.5
Permanent Ineff=
       F       F       F
Bank Sta=-10.887,10.526
XS Rating Curve= 0 ,0
Skew Angle= 35
Exp/Cntr=0.5,0.3