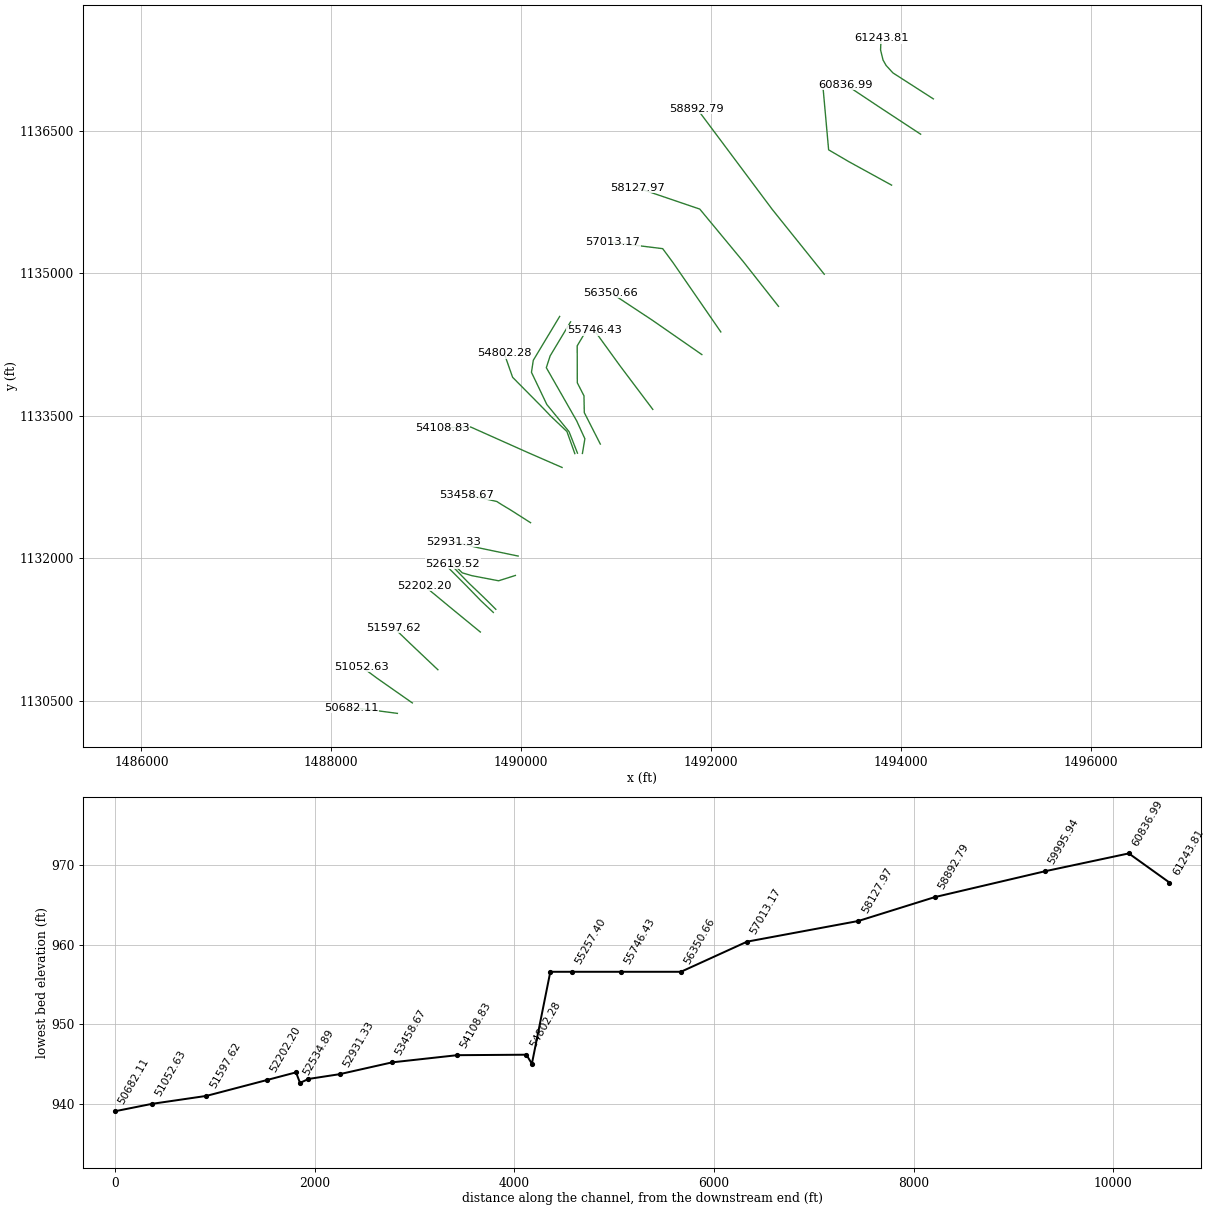
HEC-RAS study 12mile_Combined.prj: 12mile Creek Combined Model

--- 12mile_Combined.g07 (geometry) --- (continued)

Type RM Length L Ch R = 3 ,61281.73,,,
BEGIN DESCRIPTION:
Ponderosa Rd (TWE_32) - TOR
Skew = 35 Degrees
END DESCRIPTION:
Bridge Culvert--1,0,-1,-1, 0
Deck Dist Width WeirC Skew NumUp NumDn MinLoCord MaxHiCord MaxSubmerge Is_Ogee
20,27.5,2.6,35, 166, 166, 980.35, , 0.95, 0, 0,0,,
-362.065-348.852-348.344-344.912-338.875-337.474 -335.14-332.289-329.463-328.341
-326.104-317.307-316.946-313.702-312.015-308.517-304.028-303.234 -301.03-300.932
-300.817-297.909-295.992-293.011-289.832 -286.13-281.469-280.355-279.544-277.906
-276.308-268.641-268.125-267.797-252.217-215.863-213.135-196.441-175.987-154.869
-134.578-129.221-111.446  -90.23 -69.292 -48.649 -23.977 -23.977 -19.471  15.924
   20.02   20.02  52.557  73.404   93.26  96.996 115.074 133.948 140.992 164.289
 190.608 200.143 226.274 254.232 255.715 255.928 256.051 259.425 260.466 260.777
 262.006  265.52 267.805 269.419 272.393  272.95 274.105 274.768 277.594 278.888
 279.699 282.689 285.089 286.113 288.358 288.997 291.594 294.272  296.05   297.5
 298.499 299.203 300.916 301.923 302.521 303.201 304.913 305.667 306.076 310.721
  311.36 312.662 314.161 314.497 315.447 317.643 318.675 320.837  321.14 323.844
 324.859 326.825 327.276 328.783 332.469 332.838 333.067 334.992 336.082 337.302
 339.948 341.029 342.651 342.897 343.077  344.74 345.764 346.485 347.304 349.901
  350.63 350.982 352.465 352.579 353.071 353.407 354.947 355.717 356.241 356.405
 358.101 359.796 360.271 360.558 361.877 362.655 363.982 365.448 365.973 366.366
 367.062 368.356 369.028 370.265 370.765  372.19 373.836  374.23 374.271 374.787
 377.547 377.785 379.153 379.472  379.53 379.915
 1002.89 1002.75 1002.55  1001.2  998.68  998.01  996.62  995.47  994.14  993.66
  992.76  989.78  989.67  988.82  988.65   987.9  987.03  986.83  986.48  986.47
  986.45   986.2  986.06   985.9  985.98  986.12  985.74  985.78  985.81  985.91
  985.93  985.89  985.88  985.93  985.58  984.43  984.39  984.12  983.38  982.59
  982.07  981.99  981.74  981.51  981.22  981.01  980.64  983.55  983.55  983.26
  983.26  980.35  981.12  981.24  981.49  981.63  982.29  984.07  984.68  986.69
  989.09   989.9  992.13  994.46  994.52  994.54  994.55  994.79  995.16  995.24
  995.26  995.32  995.47  995.56  996.14  996.19  996.19  995.99   996.1  996.12
  996.23  996.45  996.62  996.68  996.76  996.78  997.03  997.08  997.26  997.35
  997.42  997.46  997.73  997.84  997.82  997.81  997.84  997.95  997.93  998.19
  998.23  998.32  998.41  998.44  998.48  998.57  998.67  998.86  998.87  999.01
  999.07   999.2  999.22  999.27  999.54  999.57  999.58  999.74  999.82   999.9
 1000.01 1000.12 1000.16 1000.16 1000.19 1000.39 1000.44 1000.47 1000.51 1000.65
 1000.71 1000.74 1000.86 1000.87  1000.9 1000.88 1001.03 1001.09 1001.12 1001.13
  1001.2 1001.35 1001.39 1001.41 1001.44 1001.47 1001.56 1001.63 1001.66 1001.69
 1001.75 1001.89 1001.92 1002.02 1002.04 1002.12 1002.28 1002.32 1002.32 1002.34
 1002.39  1002.4 1002.57  1002.6  1002.6 1002.62
                                                                                
                                                                                
                                                                                
                                                                                
                                                                  979.61  979.63
                                                                                
                                                                                
                                                                                
                                                                                
                                                                                
                                                                                
                                                                                
                                                                                
                                                                                
                                                                                
                                                                                
                                                
 -349.18-348.852-348.344-344.912-338.875-337.474 -335.14-332.289-329.463-328.341
-326.104-317.307-316.946-313.702-312.015-308.517-304.028-303.234 -301.03-300.932
-300.817-297.909-295.992-293.011-289.832 -286.13-281.469-280.355-279.544-277.906
-276.308-268.641-268.125-267.797-252.217-215.863-213.135-196.441-175.987-154.869
-134.578-129.221-111.446  -90.23 -69.292 -48.649 -23.977 -23.977 -19.471  15.924
   20.02   20.02  52.557  73.404   93.26  96.996 115.074 133.948 140.992 164.289
 190.608 200.143 226.274 254.232 255.715 255.928 256.051 259.425 260.466 260.777
 262.006  265.52 267.805 269.419 272.393  272.95 274.105 274.768 277.594 278.888
 279.699 282.689 285.089 286.113 288.358 288.997 291.594 294.272  296.05   297.5
 298.499 299.203 300.916 301.923 302.521 303.201 304.913 305.667 306.076 310.721
  311.36 312.662 314.161 314.497 315.447 317.643 318.675 320.837  321.14 323.844
 324.859 326.825 327.276 328.783 332.469 332.838 333.067 334.992 336.082 337.302
 339.948 341.029 342.651 342.897 343.077  344.74 345.764 346.485 347.304 349.901
  350.63 350.982 352.465 352.579 353.071 353.407 354.947 355.717 356.241 356.405
 358.101 359.796 360.271 360.558 361.877 362.655 363.982 365.448 365.973 366.366
 367.062 368.356 369.028 370.265 370.765  372.19 373.836  374.23 374.271 374.787
 377.547 377.785 379.153 379.472  379.53 379.915
 1002.89 1002.75 1002.55  1001.2  998.68  998.01  996.62  995.47  994.14  993.66
  992.76  989.78  989.67  988.82  988.65   987.9  987.03  986.83  986.48  986.47
  986.45   986.2  986.06   985.9  985.98  986.12  985.74  985.78  985.81  985.91
  985.93  985.89  985.88  985.93  985.58  984.43  984.39  984.12  983.38  982.59
  982.07  981.99  981.74  981.51  981.22  981.01  980.64  983.55  983.55  983.26
  983.26  980.35  981.12  981.24  981.49  981.63  982.29  984.07  984.68  986.69
  989.09   989.9  992.13  994.46  994.52  994.54  994.55  994.79  995.16  995.24
  995.26  995.32  995.47  995.56  996.14  996.19  996.19  995.99   996.1  996.12
  996.23  996.45  996.62  996.68  996.76  996.78  997.03  997.08  997.26  997.35
  997.42  997.46  997.73  997.84  997.82  997.81  997.84  997.95  997.93  998.19
  998.23  998.32  998.41  998.44  998.48  998.57  998.67  998.86  998.87  999.01
  999.07   999.2  999.22  999.27  999.54  999.57  999.58  999.74  999.82   999.9
 1000.01 1000.12 1000.16 1000.16 1000.19 1000.39 1000.44 1000.47 1000.51 1000.65
 1000.71 1000.74 1000.86 1000.87  1000.9 1000.88 1001.03 1001.09 1001.12 1001.13
  1001.2 1001.35 1001.39 1001.41 1001.44 1001.47 1001.56 1001.63 1001.66 1001.69
 1001.75 1001.89 1001.92 1002.02 1002.04 1002.12 1002.28 1002.32 1002.32 1002.34
 1002.39  1002.4 1002.57  1002.6  1002.6 1002.62
                                                                                
                                                                                
                                                                                
                                                                                
                                                                  979.63   979.6
                                                                                
                                                                                
                                                                                
                                                                                
                                                                                
                                                                                
                                                                                
                                                                                
                                                                                
                                                                                
                                                                                
                                                
Pier Skew, UpSta & Num, DnSta & Num=  ,-8.814, 4 ,-8.814, 4 , 3 , 3 , 0 ,,
       1       1     1.5     1.5
     970  978.61  978.61     980
       1       1     1.5     1.5
     970  978.61  978.61     980
Pier Skew, UpSta & Num, DnSta & Num=  ,4.751, 4 ,4.751, 4 , 3 , 3 , 0 ,,
       1       1     1.5     1.5
     970  978.61  978.61     980
       1       1     1.5     1.5
     970  978.61  978.61     980
BR Coef=-1 ,-1 , 0 ,, 0 ,,,0.8,0,1.2,0,
WSPro=,,,, 1 ,,,, 0 ,,,, 0 ,,,,-1 ,-1 ,-1 , 0 , 0 , 0 , 0 , 0
BC Design=,, 0 ,, 0 ,,,,,,
BC Use User HTab Curves=0
BC User HTab FreeFlow(D)= 0

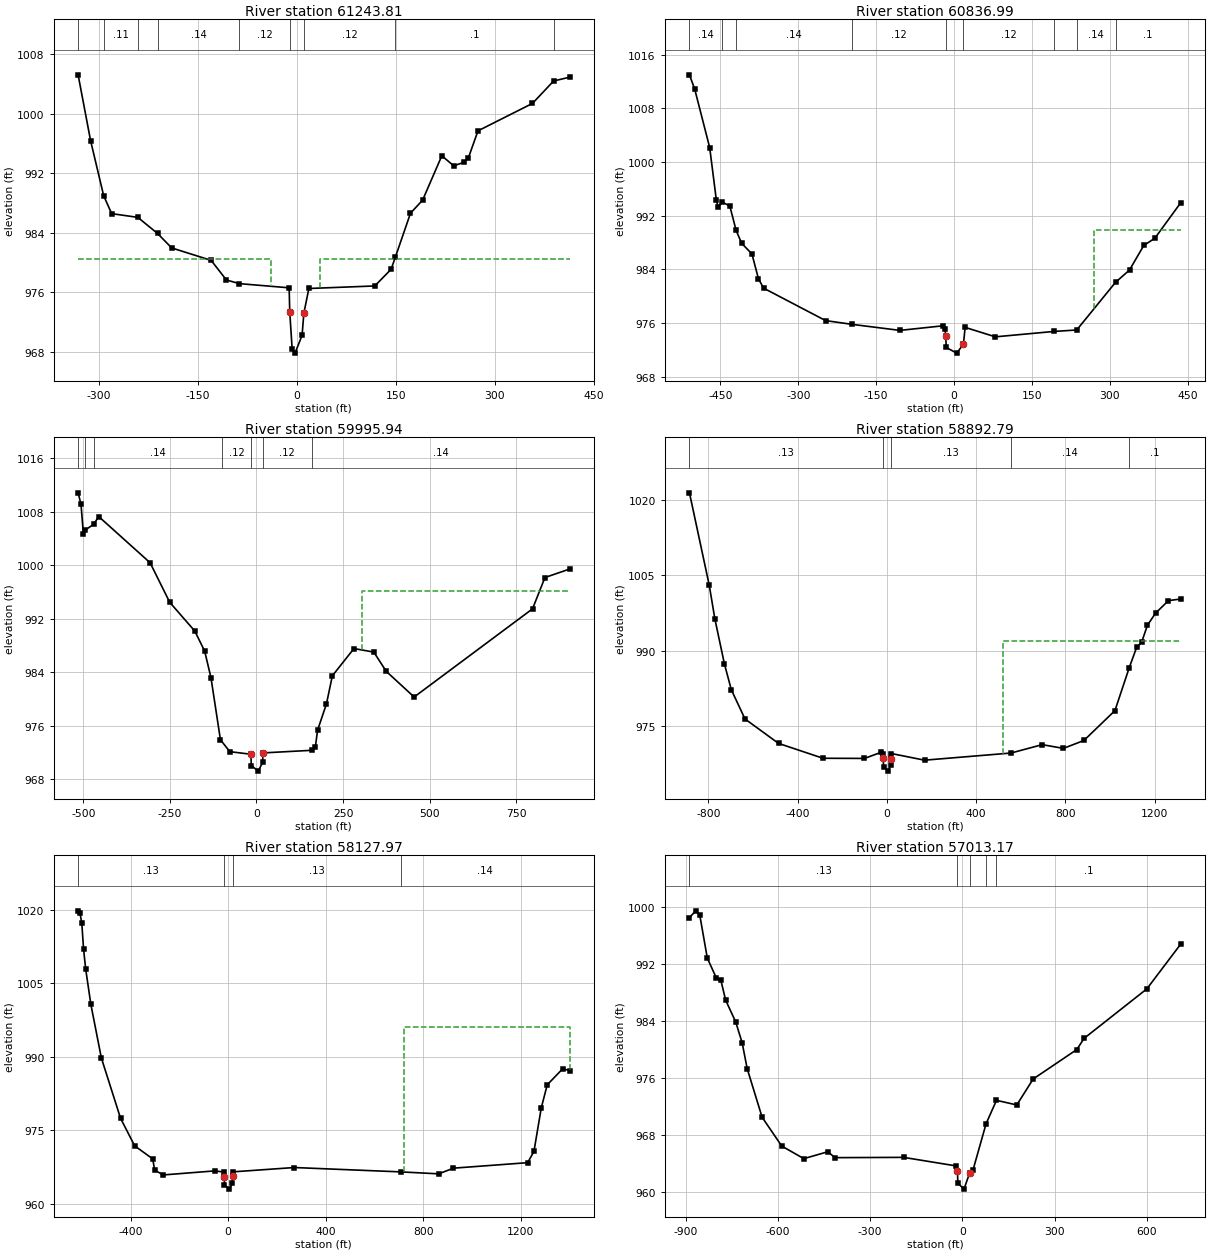
Type RM Length L Ch R = 1 ,61243.81,387.1822,406.8167,383.6989
BEGIN DESCRIPTION:
Ponderosa Rd (TWE_32) - DS
END DESCRIPTION:
XS GIS Cut Line= 6
   1494339.90584    1136838.5899   1493913.69751   1137112.57776
   1493841.74245    1137191.2897   1493809.85991   1137248.08038
   1493783.95538   1137353.69094   1493788.93701   1137476.23917
#Sta/Elev= 30
 -331.92 1005.25-313.023  996.41 -293.15     989-281.018  986.59-241.363  986.09
-211.472  983.93-189.929  981.98-130.114  980.31-106.908  977.67   -87.1  977.18
 -11.747  976.62 -10.887  973.43  -7.176  968.34  -2.818  967.84   7.888  970.24
  10.526  973.19  18.152  976.53 118.204  976.87 142.901  979.11 149.299  980.72
 172.341  986.65 190.756  988.41 219.844  994.37 237.906  993.02 253.052  993.48
 259.851  994.01 274.719  997.72 357.429 1001.41 389.441 1004.42 413.565 1004.93
#Mann= 9 ,-1,0
 -331.92     .14       0 -293.15     .11       0-241.363     .06       0
-211.472     .14       0   -87.1     .12       0-10.8869     .04       0
  10.526     .12       0 149.299      .1       0 389.441     .14       0
#XS Ineff= 2 ,-1
 -331.92     -40   980.5      35 413.565   980.5
Permanent Ineff=
       F       F
Bank Sta=-10.887,10.526
XS Rating Curve= 0 ,0
Skew Angle= 35
Exp/Cntr=0.5,0.3

Type RM Length L Ch R = 1 ,60836.99,650.8298,841.0577,674.1644
XS GIS Cut Line= 3
   1494205.80315   1136466.79462   1493779.22999   1136747.10105
   1493416.13419   1136988.72146
#Sta/Elev= 30
 -509.67    1013  -499.5 1010.85 -470.69 1002.15  -457.8  994.27 -454.15  993.24
 -446.55  994.02 -431.96  993.44 -419.85  989.82 -409.21  987.88 -389.36   986.3
 -376.77  982.59 -366.88  981.19 -247.38  976.35 -196.38  975.79 -104.25  974.89
  -22.06  975.57   -17.3  975.06  -16.12  974.02  -14.93  972.34    5.12   971.5
   18.08  972.83   21.34  975.34   79.56  973.93  193.47  974.74  236.31  974.95
   311.1  982.06     338  983.89  365.44  987.55  386.81  988.63   436.9  993.95
#Mann= 9 ,-1,0
 -509.67     .14       0 -446.55     .06       0 -419.85     .14       0
 -196.38     .12       0  -16.12     .04       018.07999     .12       0
  193.47     .12       0  236.31     .14       0   311.1      .1       0
#XS Ineff= 2 , 0
                          269.36          989.92
Permanent Ineff=
       F       F
Bank Sta=-16.12,18.08
XS Rating Curve= 0 ,0
Exp/Cntr=0.3,0.1

Type RM Length L Ch R = 1 ,59995.94,1016.771,1103.151,955.7007
XS GIS Cut Line= 4
   1493900.16142   1135930.25492   1493450.41831   1136177.14272
   1493236.87631   1136302.14304    1493177.9393   1136958.03281
#Sta/Elev= 30
 -515.04 1010.82 -506.69 1009.11 -499.77  1004.7  -495.1 1005.24  -469.8 1006.13
 -455.61 1007.28 -307.22 1000.38 -250.48  994.47 -177.89  990.16 -149.58  987.17
 -131.42  983.22 -104.04  973.94  -77.03  972.16  -16.12  971.77  -14.93  970.09
    5.12  969.25   18.08  970.58   18.53  971.97  159.77  972.36  170.16   972.9
  176.45  975.36  202.09  979.29  219.16  983.49  281.51  987.56  338.91  987.03
   374.7  984.16  455.34  980.32  797.21  993.49  833.03  998.17  903.98  999.43
#Mann= 7 ,-1,0
 -515.04     .14       0  -495.1     .06       0  -469.8     .14       0
-98.9599     .12       0  -16.12     .04       018.53003     .12       0
  159.77     .14       0
#XS Ineff= 2 , 0
                          303.33           996.1
Permanent Ineff=
       F       F
Bank Sta=-16.12,18.53
XS Rating Curve= 0 ,0
Exp/Cntr=0.3,0.1

Type RM Length L Ch R = 1 ,58892.79,585.639,764.8176,605.2095
XS GIS Cut Line= 3
   1493190.86877   1134992.24475   1492643.99278   1135673.66962
   1491849.72047   1136737.04003
#Sta/Elev= 30
 -884.33 1021.41 -795.52 1002.97  -770.5   996.3 -727.55  987.31 -696.76   982.2
 -635.48  976.38 -485.27  971.52 -286.17  968.56  -100.4  968.53  -26.73  969.73
   -16.8  969.48  -16.12  968.52  -14.93  966.84    5.12     966   17.82  967.28
   18.78  968.42   20.36   969.5  168.59  968.18  555.69   969.6   695.7  971.27
  790.66  970.53  882.52   972.1 1021.45  978.05  1085.6  986.61  1118.7  990.65
 1140.68  991.61 1166.86  995.03 1203.34  997.45 1261.21  999.95 1316.67 1000.27
#Mann= 5 ,-1,0
 -884.33     .13       0  -16.12     .04       018.78003     .13       0
  555.69     .14       0  1085.6      .1       0
#XS Ineff= 1 ,-1
520.1299 1316.67     992
Permanent Ineff=
       F
Bank Sta=-16.12,18.78
XS Rating Curve= 0 ,0
Exp/Cntr=0.3,0.1

Type RM Length L Ch R = 1 ,58127.97,653.5295,1114.794,595.4461
XS GIS Cut Line= 4
   1492709.09744   1134653.70243    1492340.1729   1135122.45341
   1491880.10269   1135678.00984   1491219.16306   1135902.89304
#Sta/Elev= 30
  -615.5 1019.82 -607.64 1019.29 -600.34 1017.31  -593.2 1012.04 -584.65 1008.02
 -563.25 1000.73 -520.19  989.79 -441.42  977.47 -383.41  971.83 -309.46  969.18
 -301.33  966.85 -265.32   965.9  -53.13  966.73  -18.99  966.48  -16.12  965.52
  -14.93  963.84    5.12     963   17.82  964.28   19.09  965.58   20.34  966.53
  271.28  967.41  708.23  966.52  863.57  966.12  924.56  967.28 1228.79   968.4
 1254.58  970.69 1284.75  979.61 1309.18   984.3  1372.7  987.58 1400.49  987.21
#Mann= 4 ,-1,0
  -615.5     .13       0  -16.12     .04       019.09003     .13       0
  708.23     .14       0
#XS Ineff= 2 , 0
                        721.9399          996.12
Permanent Ineff=
       F       F
Bank Sta=-16.12,19.09
XS Rating Curve= 0 ,0
Exp/Cntr=0.3,0.1

Type RM Length L Ch R = 1 ,57013.17,453.8044,662.5118,694.4956
BEGIN DESCRIPTION:
TWE_31X
END DESCRIPTION:
XS GIS Cut Line= 4
   1492101.45735   1134384.60433   1491597.63123   1135115.19783
   1491489.47671   1135261.34252   1490964.30217   1135326.44652
#Sta/Elev= 30
 -887.96  998.54 -867.37  999.48 -854.26  998.85 -829.94  992.85 -800.23  990.02
 -785.81  989.74 -770.35  986.95 -737.35  983.86 -716.43  980.93 -700.24  977.33
 -651.59  970.49 -587.76  966.45 -515.97  964.68 -437.66  965.65  -414.9  964.82
  -191.5  964.86  -21.98  963.67  -16.12  962.92  -14.93  961.24    5.12   960.4
   23.62  962.69   34.16  963.04   77.06   969.6  110.82  972.87  176.85  972.22
  230.25  975.87  372.11     980  395.72  981.57  599.92  988.52  710.52  994.83
#Mann= 5 ,-1,0
 -887.96     .13       0  -16.12     .04       0   23.62     .13       0
   77.06     .14       0  110.82      .1       0
Bank Sta=-16.12,23.62
XS Rating Curve= 0 ,0
Exp/Cntr=0.3,0.1

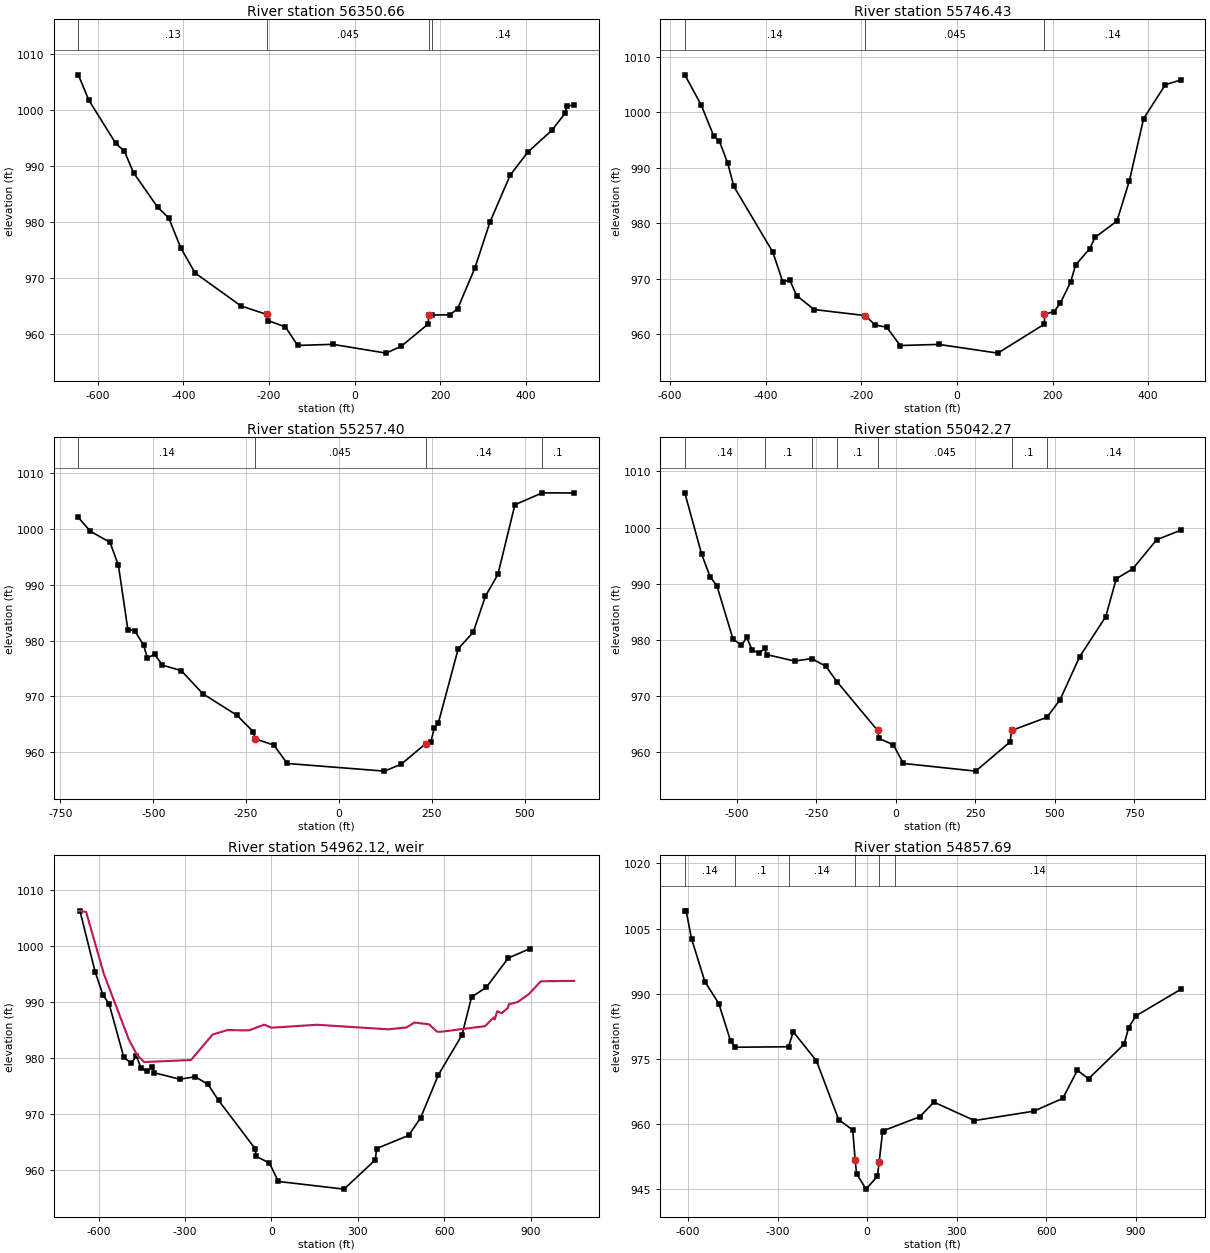
Type RM Length L Ch R = 1 ,56350.66,671.6779,604.2281,529.3818
XS GIS Cut Line= 3
   1491901.80413   1134145.88878   1491376.62927   1134510.47277
   1490942.60072   1134796.93176
#Sta/Elev= 30
 -645.76 1006.29 -621.21 1001.76 -558.13  994.04 -538.12  992.66 -516.64  988.81
 -460.33  982.65 -434.46  980.76 -406.38  975.42 -372.91  970.93 -265.41  965.03
  -204.8  963.51-201.958  962.42-161.471  961.28 -132.96  957.98-51.1319  958.18
 73.8066  956.61  109.72  957.86 172.525  961.83  173.41   963.4  181.21  963.41
  222.97  963.45  241.01  964.52  281.39  971.78  316.97  980.06  364.22   988.4
  405.77  992.54  461.57  996.39  492.65  999.46  497.02 1000.79   513.6 1000.83
#Mann= 4 ,-1,0
 -645.76     .13       0  -204.8    .045       0  173.41    .045       0
  181.21     .14       0
Bank Sta=-204.8,173.41
XS Rating Curve= 0 ,0
Exp/Cntr=0.3,0.1

Type RM Length L Ch R = 1 ,55746.43,591.4186,489.0385,359.0197
XS GIS Cut Line= 3
   1491385.30971   1133568.63058   1491042.42717   1134024.36056
   1490768.98917   1134401.96555
#Sta/Elev= 30
  -568.8 1006.73  -534.3 1001.26 -508.35  995.71 -496.46  994.77 -478.98  990.79
 -466.27  986.63 -384.93  974.83 -363.77   969.4 -349.68  969.81 -334.94  966.97
  -298.5  964.46 -191.49  963.37-170.882  961.67-146.718  961.28-118.568  957.98
-37.7758  958.18 85.5812  956.61  183.05  961.83  183.06   963.6  203.12  964.08
  215.91  965.55  237.85  969.42  248.12  972.47  277.85  975.44  288.82  977.45
  334.55  980.39  360.51  987.62  390.36  998.84  435.73 1004.95  467.73 1005.79
#Mann= 3 ,-1,0
  -568.8     .14       0 -191.49    .045       0  183.06     .14       0
Bank Sta=-191.49,183.06
XS Rating Curve= 0 ,0
Exp/Cntr=0.3,0.1

Type RM Length L Ch R = 1 ,55257.40,187.8023,215.1259,357.8358
BEGIN DESCRIPTION:
TWE_30USX
END DESCRIPTION:
XS GIS Cut Line= 6
   1490832.65846   1133203.58268   1490664.02854   1133534.68504
   1490660.48196   1133711.85991   1490590.27461   1133848.89764
   1490589.26444   1134237.87434   1490712.56529   1134445.36877
#Sta/Elev= 30
 -701.92 1002.12 -669.43  999.62 -616.62  997.66 -593.93  993.51 -568.56     982
 -550.36  981.82 -526.34  979.23 -515.76  976.91 -496.22  977.56 -475.24  975.62
  -424.5  974.63 -366.62  970.49 -275.16  966.65 -230.35  963.66 -226.53  962.42
 -175.28  961.28 -139.19  957.98  122.54  956.61     168  957.86  233.65  961.53
   247.5  961.83  256.66  964.32   267.4  965.17  321.29  978.56   361.7  981.53
  394.69  988.01   428.2   991.9  473.91 1004.39  547.78 1006.53  633.53  1006.5
#Mann= 4 ,-1,0
 -701.92     .14       0 -226.53    .045       0  233.65     .14       0
  547.78      .1       0
Bank Sta=-226.53,233.65
XS Rating Curve= 0 ,0
Exp/Cntr=0.5,0.3

Type RM Length L Ch R = 1 ,55042.27,202.4462,184.575,406.9847
BEGIN DESCRIPTION:
Dam E. of Midway RD (TWE_30) - US
END DESCRIPTION:
XS GIS Cut Line= 6
    1490644.1227   1133104.83136   1490670.16437   1133259.34547
   1490583.35892   1133448.58235   1490263.88944   1134008.10827
   1490304.39633   1134132.39961   1490519.77657   1134490.95932
#Sta/Elev= 30
  -664.1 1006.19  -611.2  995.28 -584.22  991.21 -562.91  989.61 -512.24  980.12
 -485.69  979.05 -468.89  980.42 -452.19  978.18 -430.11  977.64 -412.86  978.46
 -406.47  977.37 -318.23  976.22 -264.67  976.66 -220.53  975.31 -183.53  972.44
  -57.06  963.85  -52.49  962.44 -7.4936  961.28 23.9047  957.98251.6098  956.61
 360.325  961.83  364.59  963.85  475.65  966.19  516.99  969.29  579.03     977
   660.9  984.11  694.12  990.88  745.89  992.64  821.37  997.83  896.76  999.52
#Mann= 7 ,-1,0
  -664.1     .14       0 -412.86      .1       0 -264.67     .14       0
 -183.53      .1       0  -57.06    .045       0  364.59      .1       0
  475.65     .14       0
Bank Sta=-57.06,364.59
XS Rating Curve= 0 ,0
Exp/Cntr=0.5,0.3

Type RM Length L Ch R = 5 ,54962.12,,,
BEGIN DESCRIPTION:
Dam E. of Midway RD (TWE_30) - TOR
END DESCRIPTION:
IW Pilot Flow=0
#Inline Weir SE= 30
    -670 1006.26 -642.93 1006.07 -581.76  995.05 -494.55  983.27 -466.53  980.59
 -441.65  979.28 -279.13  979.64  -204.3  984.18 -153.25  984.98  -78.06  984.93
  -24.98  985.95      .2  985.41  157.86  985.93  405.88  985.12  468.93  985.46
  495.67  986.33  546.23  986.02  574.62  984.69  586.77  984.68  739.99  985.67
  771.22  987.22  774.48  986.89  783.13  988.36  797.87  987.99  819.72  988.91
  823.95  989.61   853.8  989.98  894.12  991.46  934.18  993.69    1050  993.76
IW Dist,WD,Coef,Skew,MaxSub,Min_El,Is_Ogee,SpillHt,DesHd
74,12,2.6,0,0.98,, 0 ,,,0,0,
IW Gate Name Wd,H,Inv,GCoef,Exp_T,Exp_O,Exp_H,Type,WCoef,Is_Ogee,SpillHt,DesHd,#Openings
Gate #1     ,2.66,2.66,962.93,0.5,0,1,0.5, 0 ,3, 0 ,,, 1 ,0,0.8, 0 ,0.5,,0,0,0, 0
      -6
IW Gate Opening=1,Opening #1,0
Inline Weir Flap Gates= 0
IW Outlet Rating Curve= 0 ,False,,

Type RM Length L Ch R = 1 ,54857.69,50.84569,55.41602,71.15096
BEGIN DESCRIPTION:
Dam E. of Midway RD (TWE_30) - DS
END DESCRIPTION:
XS GIS Cut Line= 6
   1490592.03937   1133108.30348   1490503.49738   1133333.99869
   1490269.14436   1133620.46982   1490107.66339        1133959.
   1490126.76083   1134085.73589   1490404.53904   1134547.54265
#Sta/Elev= 30
 -611.27 1008.93  -606.9 1009.08 -588.71 1002.67 -544.08   992.8 -497.29  987.74
 -457.94  979.16 -442.33  977.69 -263.42   977.8 -247.92  981.25 -169.91  974.56
  -95.72  961.06   -48.4  958.62  -40.16  951.66  -35.39  948.58   -3.66  945.04
   34.33     948   40.07   951.3   51.54  958.15   55.29  958.51  175.84  961.67
  223.66  965.06  359.54  960.82  558.15  962.97  655.49  965.92  704.55  972.37
  742.04  970.43  861.17  978.39  876.49  982.23  900.66   984.9  1050.6  990.99
#Mann= 6 ,-1,0
 -611.27     .14       0 -442.33      .1       0 -263.42     .14       0
-40.1599    .045       040.07001     .14       091.90002     .14       0
Bank Sta=-40.16,40.07
XS Rating Curve= 0 ,0
Exp/Cntr=0.5,0.3

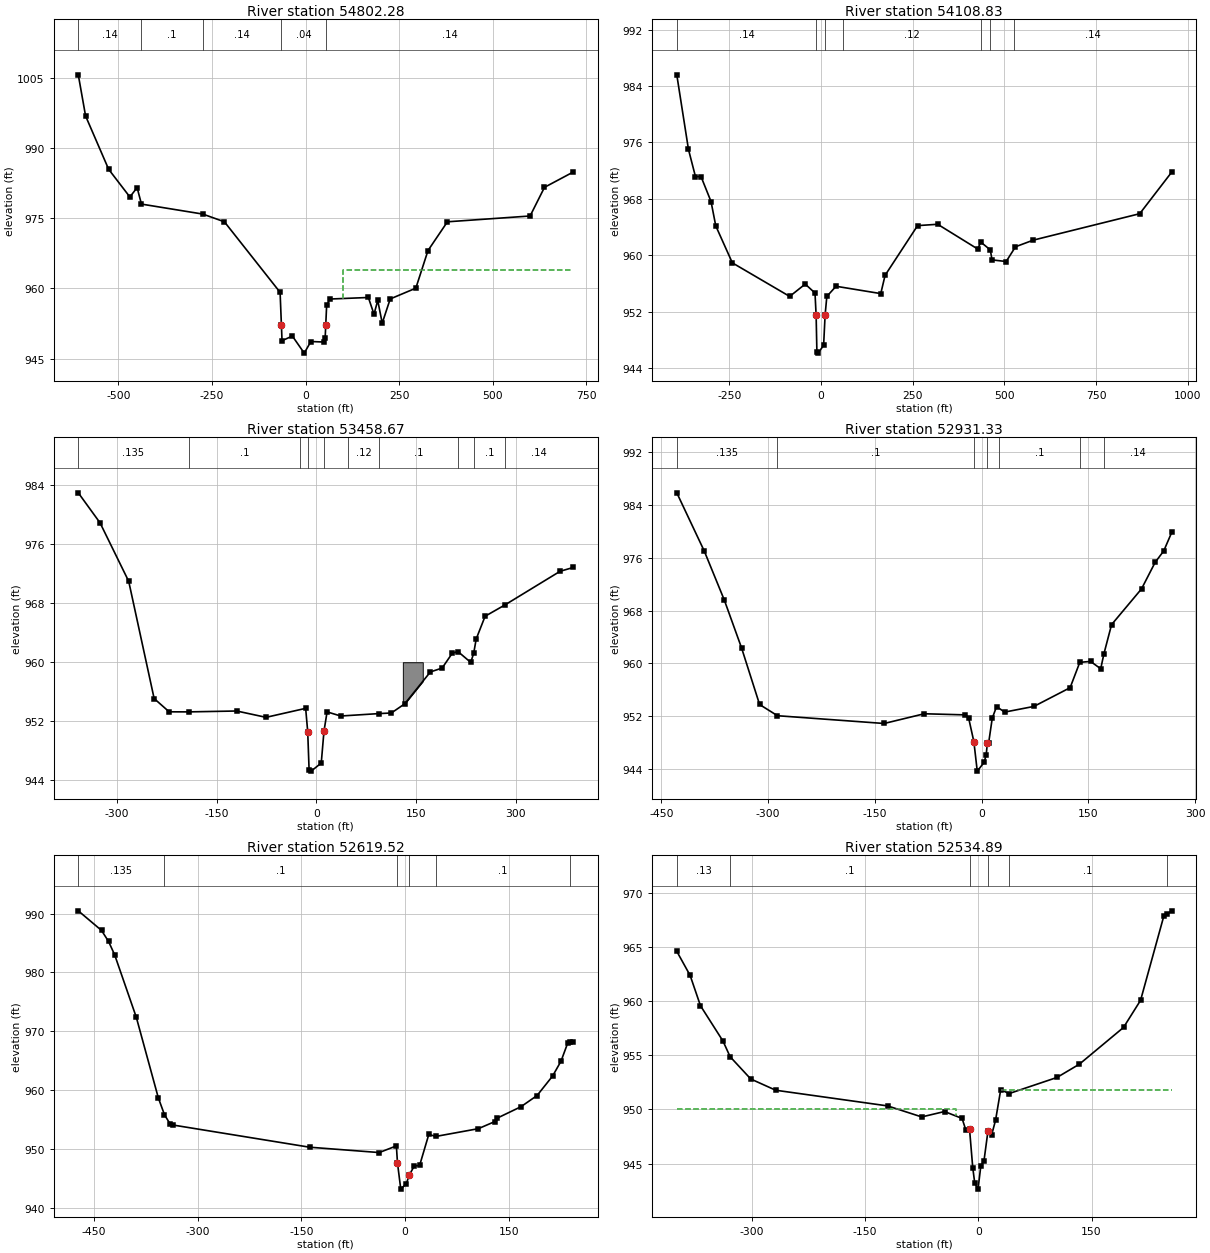
Type RM Length L Ch R = 1 ,54802.28,527.0717,693.4466,535.7596
BEGIN DESCRIPTION:
TWE_30DSX
END DESCRIPTION:
XS GIS Cut Line= 6
   1490564.26148   1133103.09514   1490480.92815   1133335.73458
   1490310.07087   1133498.24409   1490226.75427   1133585.52756
   1489909.04528   1133906.70899   1489820.50361   1134158.44554
#Sta/Elev= 30
 -607.24  1005.6 -587.76  996.82 -526.14  985.43 -469.43  979.52 -450.12  981.52
  -438.5     978 -274.69  975.87 -216.89  974.22  -68.13  959.16   -64.6  952.09
  -62.97  948.83  -35.39  949.83   -3.66  946.18   14.12  948.66   48.08  948.55
   52.26  949.45   53.83  952.18   56.22  956.43   65.11  957.73  167.68  958.06
  182.76  954.48   192.7  957.44  204.68  952.58  226.02  957.75  294.47  960.05
  326.94  968.08  378.82  974.22  599.72  975.46  638.16  981.58  714.96  984.85
#Mann= 5 ,-1,0
 -607.24     .14       0  -438.5      .1       0 -274.69     .14       0
-64.5999     .04       053.83002     .14       0
#XS Ineff= 1 ,-1
  100.27  714.96  963.98
Permanent Ineff=
       F
Bank Sta=-64.6,53.83
XS Rating Curve= 0 ,0
Exp/Cntr=0.3,0.1

Type RM Length L Ch R = 1 ,54108.83,630.9732,650.1635,610.911
XS GIS Cut Line= 4
   1490429.87992   1132957.27165   1490076.14665   1133111.35138
   1489466.75131   1133383.54823   1489171.19685   1133373.93898
#Sta/Elev= 30
 -392.97  985.58 -361.18  975.01  -342.1  971.15  -326.9  971.15 -299.64  967.61
 -286.73  964.16 -241.56  958.92   -85.3  954.16  -42.91  955.91  -16.28  954.64
   -13.2  951.46  -11.14  946.33   -7.94  946.12    7.19  947.22   11.26  951.52
   15.95  954.16   41.09   955.6  162.96  954.56   174.7  957.15   263.3   964.2
  318.07  964.39   427.2  960.88  435.43961.8668  461.49960.7619   466.2  959.34
  504.74  959.11  530.14   961.2  578.53  962.14  868.76  965.89     956  971.79
#Mann= 7 ,-1,0
 -392.97     .14       0   -13.2     .04       011.26001     .14       0
60.70999     .12       0  435.43     .06       0  461.49      .1       0
525.0602     .14       0
Bank Sta=-13.2,11.26
XS Rating Curve= 0 ,0
Exp/Cntr=0.3,0.1

Type RM Length L Ch R = 1 ,53458.67,464.3838,527.3426,535.4126
BEGIN DESCRIPTION:
TWE_29X
END DESCRIPTION:
XS GIS Cut Line= 5
    1490097.8481    1132375.6729   1489884.26542   1132511.71916
   1489794.05807   1132565.68701   1489741.91503    1132599.0584
   1489425.10367   1132670.81266
#Sta/Elev= 30
 -358.57  982.99 -325.85  978.92 -282.67  970.98 -244.38  955.07 -221.78  953.27
 -192.62  953.26 -120.13  953.38  -75.94  952.52  -16.28  953.74   -13.2  950.56
  -11.14  945.43   -7.94  945.22    7.19  946.32   11.26  950.62   15.95  953.26
   36.53   952.7   94.28  953.03   112.7  953.11  132.78  954.35  171.45  958.68
  189.16  959.21  204.42  961.22  212.93  961.45   232.2  959.98  236.63   961.2
  240.46  963.16  253.86  966.24  283.97  967.79   366.7  972.34  386.52  972.86
#Mann= 10 ,-1,0
 -358.57    .135       0 -192.62      .1       0-24.5199     .12       0
   -13.2     .04       011.26001      .1       047.39001     .12       0
   94.28      .1       0  212.93     .06       0  236.63      .1       0
  283.97     .14       0
#Block Obstruct= 1 ,-1
     130     160     960
Bank Sta=-13.2,11.26
XS Rating Curve= 0 ,0
Exp/Cntr=0.3,0.1

Type RM Length L Ch R = 1 ,52931.33,302.7447,311.809,300.2909
XS GIS Cut Line= 3
   1489967.63944   1132024.10991   1489550.97178   1132110.91535
   1489288.38484   1132173.84974
#Sta/Elev= 30
 -428.46  985.79  -389.8  976.98 -361.73   969.6 -337.48  962.37  -312.1   953.8
 -286.96952.1042 -137.06  950.93  -80.65   952.4  -22.76  952.23  -18.38   951.8
  -10.93  948.18   -6.18  943.73    3.41  945.04    6.37  946.18    8.04  947.95
    9.87  948.02   14.92  951.74   21.02  953.49   32.25  952.65   73.47  953.51
  124.34  956.34  137.95 960.172  153.09  960.31  167.34   959.2  171.89961.4764
  182.59  965.87  224.74  971.28  243.83  975.28  255.92  977.01  267.17  979.82
#Mann= 7 ,-1,0
 -428.46    .135       0 -286.96      .1       0-10.9299     .04       0
8.040009     .12       024.76999      .1       0  137.95     .06       0
  171.89     .14       0
Bank Sta=-10.93,8.04
XS Rating Curve= 0 ,0
Exp/Cntr=0.3,0.1

Type RM Length L Ch R = 1 ,52619.52,161.9004,84.63351,63.53086
BEGIN DESCRIPTION:
TWE_28USX
END DESCRIPTION:
XS GIS Cut Line= 5
   1489938.41207   1131819.97211   1489761.47966   1131763.87139
   1489479.48983   1131817.76739   1489378.52165   1131847.61122
   1489280.30938   1131944.04068
#Sta/Elev= 30
 -472.44  990.46 -438.87  987.13 -428.68  985.25 -419.86  982.98 -388.52  972.34
 -356.74  958.66 -347.82  955.78 -339.28  954.14 -334.91  954.02 -138.03  950.26
  -37.33  949.35  -12.53  950.48  -10.93  947.58   -6.18  943.13    1.74  944.04
    6.37  945.58   13.37  947.07   21.09  947.16   34.36  952.44   44.39  952.09
  105.95  953.41  130.05  954.63  132.29  955.15  167.68  957.15  190.89  959.05
  213.37  962.37  225.55   964.9  235.42  968.05  238.56  968.23  243.19  968.16
#Mann= 6 ,-1,0
 -472.44    .135       0 -347.82      .1       0-10.9299    .045       0
6.369995     .12       044.39001      .1       0  238.56     .06       0
Bank Sta=-10.93,6.37
XS Rating Curve= 0 ,0
Exp/Cntr=0.5,0.3

Type RM Length L Ch R = 1 ,52534.89,49.06389,39.87159,41.53906
BEGIN DESCRIPTION:
SE. of Midway RD (TWE_28) - US
END DESCRIPTION:
XS GIS Cut Line= 5
   1489732.33202   1131463.35663   1489607.83694   1131586.93045
   1489447.63845   1131739.82251   1489351.36909   1131838.56037
    1489265.9603   1131927.27625
#Sta/Elev= 30
-399.155  964.63-381.483   962.4-367.805   959.6-337.999  956.33-328.535  954.88
-301.209  952.82-268.146  951.78-119.992  950.33 -74.854  949.31 -44.639  949.81
 -21.368  949.17 -16.617  948.14 -11.516  948.18  -7.242  944.61  -4.573  943.17
   -.269  942.63   3.447  944.78   7.661  945.27  12.841  947.98  17.762  947.65
  22.962  949.01  29.786  951.83  40.824  951.47 104.192  952.96 133.918  954.19
 192.395  957.59 214.969   960.1 245.931  967.94 249.686  968.06 256.251  968.38
#Mann= 6 ,-1,0
-399.155     .13       0-328.535      .1       0-11.5159    .045       0
  12.841     .12       040.82401      .1       0 249.686     .06       0
#XS Ineff= 2 , 0
             -30     950      30          951.84
Permanent Ineff=
       F       F
Bank Sta=-11.516,12.841
XS Rating Curve= 0 ,0
Skew Angle= 5
Exp/Cntr=0.5,0.3

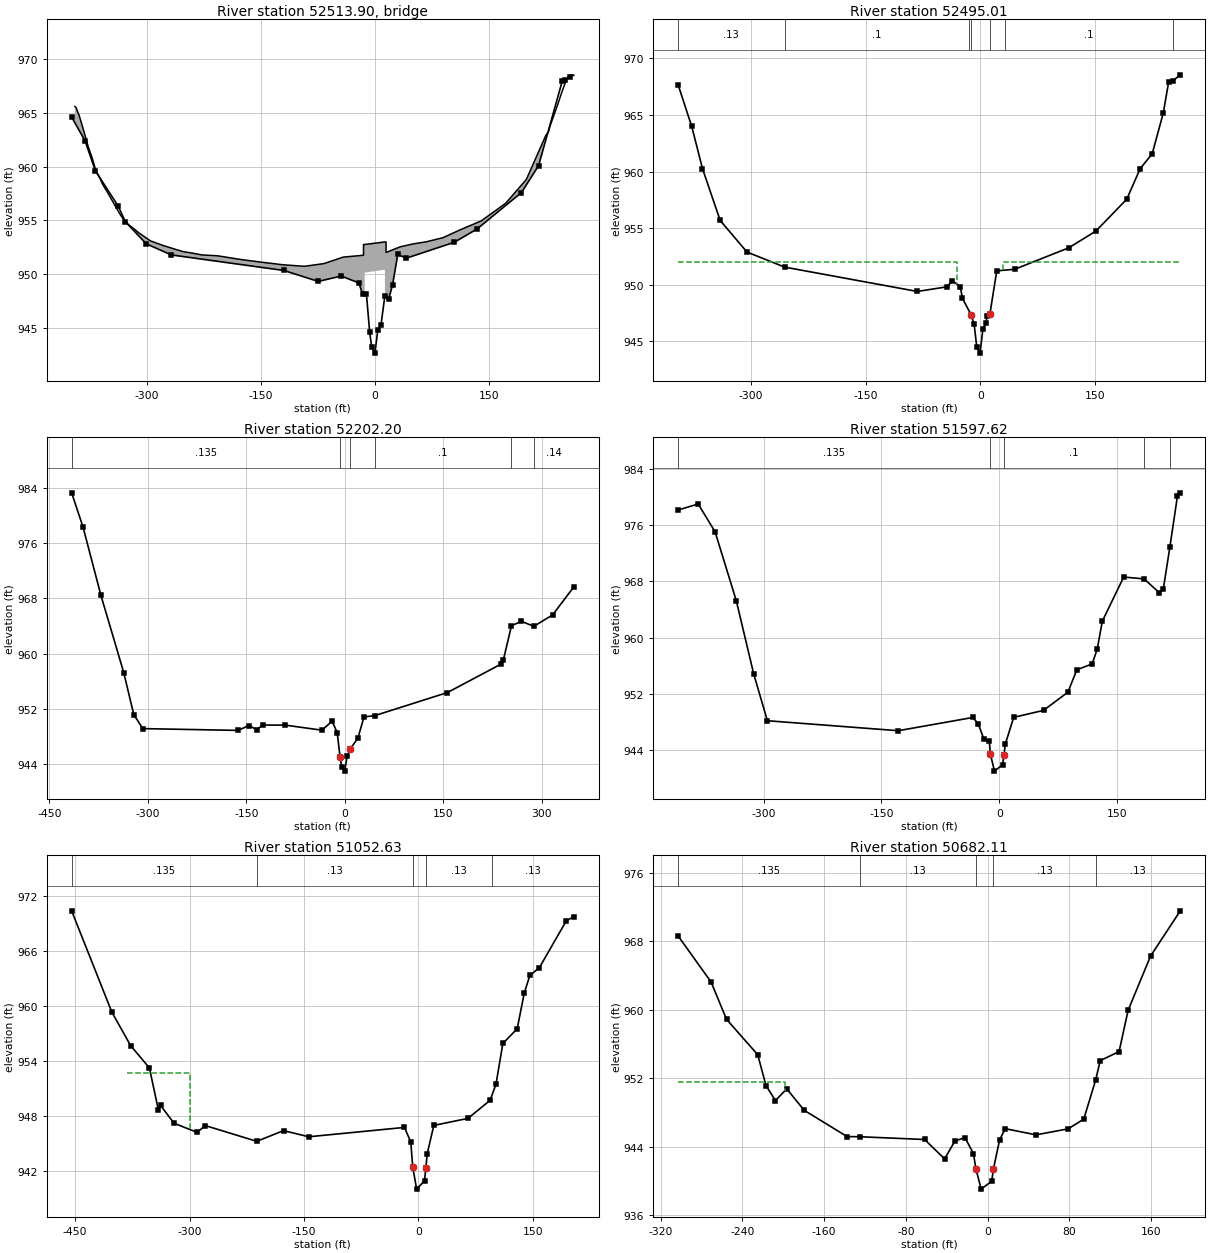
Type RM Length L Ch R = 3 ,52513.90,,,
BEGIN DESCRIPTION:
SE. of Midway RD (TWE_28) - TOR
Skew = 5 degrees
END DESCRIPTION:
Bridge Culvert--1,0,-1,-1, 0
Deck Dist Width WeirC Skew NumUp NumDn MinLoCord MaxHiCord MaxSubmerge Is_Ogee
15,12,2.6,5, 86, 86, 950.72, , 0.95, 0, 0,0,,
-394.842-393.078-391.694-391.584-389.482 -387.36-387.281-386.534-385.238-380.566
-380.088-379.889-377.139-372.398 -369.02-368.283-368.214 -366.61-360.702-359.357
-355.203-352.932-349.654-336.764-335.698-335.568-335.379 -332.42-331.803-331.155
-324.779-323.972-323.684-322.309-319.041-310.285-295.471-278.885-260.804-252.167
-244.008-238.369 -227.82-207.378 -178.04-177.293-150.336-120.908 -93.104 -67.393
  -41.93 -15.292 -15.292 -13.797  12.851  14.345  14.345  33.183  50.208  67.034
   89.01 111.863 139.487 171.804 198.831 224.473 227.939 229.444  230.36 236.068
 236.357 236.536 236.676 240.163 245.064 245.821 247.843 249.696 253.263 254.827
 255.942 257.108 259.628 260.057 261.202 261.312
  965.61  965.48   965.2  965.17  964.82  964.33  964.31  964.15  963.82  962.67
  962.55   962.5  961.81  960.86  960.06  959.79  959.77  959.54  958.76  958.49
  957.97  957.72  957.32  955.72   955.6  955.58  955.56  955.24  955.18  955.13
  954.63  954.57  954.55  954.49  954.32  953.81  953.09  952.66  952.26  952.08
  951.99  951.92  951.78   951.7  951.37  951.36  951.11  950.86  950.72  950.97
  951.58  951.75  952.75  952.75  952.99  952.99  952.01  952.54  952.81     953
  953.38  954.12  954.95   956.6  958.81  962.92  963.24  963.65  963.86  964.99
  965.04  965.09  965.11   965.8  966.85     967   967.4  967.76  968.26  968.46
  968.49  968.53  968.52  968.56  968.53  968.52
                                                                                
                                                                                
                                                                                
                                                                                
                                                                                
                          950.13   950.4
                                                                                
                                                                                
                                                
-394.842-393.078-391.694-391.584-389.482 -387.36-387.281-386.534-385.238-380.566
-380.088-379.889-377.139-372.398 -369.02-368.283-368.214 -366.61-360.702-359.357
-355.203-352.932-349.654-336.764-335.698-335.568-335.379 -332.42-331.803-331.155
-324.779-323.972-323.684-322.309-319.041-310.285-295.471-278.885-260.804-252.167
-244.008-238.369 -227.82-207.378 -178.04-177.293-150.336-120.908 -93.104 -67.393
  -41.93 -15.292 -15.292 -13.797  12.851  14.345  14.345  33.183  50.208  67.034
   89.01 111.863 139.487 171.804 198.831 224.473 227.939 229.444  230.36 236.068
 236.357 236.536 236.676 240.163 245.064 245.821 247.843 249.696 253.263 254.827
 255.942 257.108 259.628 260.057 261.202 261.312
  965.61  965.48   965.2  965.17  964.82  964.33  964.31  964.15  963.82  962.67
  962.55   962.5  961.81  960.86  960.06  959.79  959.77  959.54  958.76  958.49
  957.97  957.72  957.32  955.72   955.6  955.58  955.56  955.24  955.18  955.13
  954.63  954.57  954.55  954.49  954.32  953.81  953.09  952.66  952.26  952.08
  951.99  951.92  951.78   951.7  951.37  951.36  951.11  950.86  950.72  950.97
  951.58  951.75  952.75  952.75  952.99  952.99  952.01  952.54  952.81     953
  953.38  954.12  954.95   956.6  958.81  962.92  963.24  963.65  963.86  964.99
  965.04  965.09  965.11   965.8  966.85     967   967.4  967.76  968.26  968.46
  968.49  968.53  968.52  968.56  968.53  968.52
                                                                                
                                                                                
                                                                                
                                                                                
                                                                                
                          950.12  950.48
                                                                                
                                                                                
                                                
BR Coef=-1 ,-1 , 0 ,, 0 ,,,0.8,0,1.2,0,
WSPro=,,,, 1 ,,,, 0 ,,,, 0 ,,,,-1 ,-1 ,-1 , 0 , 0 , 0 , 0 , 0
BC Design=,, 0 ,, 0 ,,,,,,
BC Use User HTab Curves=0
BC User HTab FreeFlow(D)= 0

Type RM Length L Ch R = 1 ,52495.01,266.9324,292.8095,286.3088
BEGIN DESCRIPTION:
SE. of Midway RD (TWE_28) - DS
END DESCRIPTION:
XS GIS Cut Line= 4
   1489706.00197    1131430.4439   1489576.04495    1131552.7021
    1489423.7769   1131709.37828   1489238.64304   1131895.33465
#Sta/Elev= 30
 -395.19  967.67-377.388  963.99-363.312  960.26-340.171  955.68-305.115  952.89
-255.903  951.56 -82.435  949.41 -43.414  949.82  -36.62  950.36  -26.21  949.84
 -23.311  948.79 -11.665  947.31  -8.019  946.49  -4.573   944.5   -.269  943.96
   3.447  946.11   7.661   946.6   8.567  947.22  12.602  947.43  21.568  951.23
  45.038  951.37 115.887  953.27 151.113  954.74 191.558  957.56 209.051  960.25
 224.871  961.58 239.276  965.16 246.439  967.95 251.798  968.02 261.601  968.55
#Mann= 7 ,-1,0
 -395.19     .13       0-255.903      .1       0-14.7139     .12       0
 -11.665    .045       012.60199     .12       031.79901      .1       0
 251.798     .06       0
#XS Ineff= 2 , 0
             -30     952      30             952
Permanent Ineff=
       F       F
Bank Sta=-11.665,12.602
XS Rating Curve= 0 ,0
Skew Angle= 5
Exp/Cntr=0.5,0.3

Type RM Length L Ch R = 1 ,52202.20,580.3328,604.5864,567.6392
XS GIS Cut Line= 3
   1489569.14961    1131224.1063   1489243.62795   1131491.03412
   1488978.87073    1131710.2185
#Sta/Elev= 30
 -415.99  983.24 -398.56  978.25 -371.41  968.41  -336.7  957.25 -321.33  951.15
 -307.61  949.14 -162.64  948.88 -146.12  949.58 -134.36     949 -124.73  949.66
   -90.5  949.64  -34.79  948.91  -19.38  950.22  -11.56  948.54   -7.27  944.97
   -4.59  943.53    -.27  942.99    3.46  945.14    7.89  946.15   19.92  947.77
   29.17  950.83   45.66  951.02   156.3  954.36  237.03  958.43  241.47  959.11
  253.75  964.03  268.93  964.66   287.7  963.93  316.36  965.58  348.69  969.64
#Mann= 6 ,-1,0
 -415.99    .135       0-7.26998    .045       07.890015     .13       0
   45.66      .1       0  253.75     .06       0   287.7     .14       0
Bank Sta=-7.27,7.89
XS Rating Curve= 0 ,0
Exp/Cntr=0.3,0.1

Type RM Length L Ch R = 1 ,51597.62,477.8195,544.9846,510.2537
XS GIS Cut Line= 3
   1489122.10039   1130826.97014   1488825.57119   1131107.73031
   1488659.85958   1131267.50919
#Sta/Elev= 30
 -408.59  978.15 -383.11     979 -361.59  975.05 -334.64  965.25 -312.43  954.81
 -295.09  948.17 -128.75  946.75  -33.94  948.63  -26.98  947.74  -19.68  945.51
   -12.9  945.27  -11.49   943.4   -6.33     941    4.04  941.92    5.72  943.36
    7.54  944.88   18.11  948.65   56.01  949.64      87  952.23   98.42  955.42
   117.8  956.25  124.21  958.31   130.8  962.33  157.96  968.61  183.86  968.35
   203.1   966.4  208.26  966.85  216.66  972.84  226.37  980.17  229.96  980.59
#Mann= 5 ,-1,0
 -408.59    .135       0-11.4899     .04       05.720001      .1       0
  183.86     .06       0  216.66     .14       0
Bank Sta=-11.49,5.72
XS Rating Curve= 0 ,0
Exp/Cntr=0.3,0.1

Type RM Length L Ch R = 1 ,51052.63,267.2786,370.5237,365.7625
XS GIS Cut Line= 3
    1488853.0023   1130477.57677   1488484.07808   1130735.82415
   1488316.97703   1130859.52231
#Sta/Elev= 30
 -454.55   970.4  -401.9  959.34 -377.18  955.67 -352.64  953.24 -340.88  948.66
 -338.07  949.15 -320.45   947.2 -289.82  946.19 -279.69  946.95 -211.96945.2222
 -176.86  946.39 -143.77  945.72  -18.37  946.74   -9.99  945.15   -7.49   942.4
   -2.33     940    8.04  940.929.719999  942.36   11.54  943.88   20.15  946.96
      65  947.73   93.92   949.7  101.64  951.46  110.64  955.91  129.46  957.52
   138.7  961.42     146  963.34  158.57   964.2  193.76   969.3  203.69  969.78
#Mann= 5 ,-1,0
 -454.55    .135       0 -211.96     .13       0-7.48999     .04       0
9.720001     .13       097.07001     .13       0
#XS Ineff= 1 ,-1
 -382.35 -298.78  952.67
Permanent Ineff=
       F
Bank Sta=-7.49,9.719999
XS Rating Curve= 0 ,0
Exp/Cntr=0.3,0.1

Type RM Length L Ch R = 1 ,50682.11,326.1364,434.0806,224.7923
BEGIN DESCRIPTION:
TWE_27X
END DESCRIPTION:
XS GIS Cut Line= 3
   1488695.59252   1130367.49869   1488395.77428    1130407.1332
   1488208.02362   1130428.22802
#Sta/Elev= 30
 -302.81   968.6 -270.56  963.23 -255.47  958.88 -224.94  954.75 -216.81  951.15
 -207.62   949.4 -196.52  950.76 -179.41  948.26 -137.45   945.2    -125  945.18
  -61.69  944.86  -42.05   942.6  -32.04  944.67  -22.21  945.09  -13.84  943.22
  -11.49  941.47   -6.33  939.07    4.04  939.99    5.72  941.43   11.81  944.85
   17.33  946.12   47.41   945.4   78.71   946.1   94.08  947.23  105.84  951.84
  110.16  954.06  128.65  955.11  137.51  959.94  159.47  966.26  188.55  971.53
#Mann= 5 ,-1,0
 -302.81    .135       0    -125     .13       0-11.4899     .04       0
5.720001     .13       0  105.84     .13       0
#XS Ineff= 2 , 0
         -198.26  951.57
Permanent Ineff=
       F       F
Bank Sta=-11.49,5.72
XS Rating Curve= 0 ,0
Exp/Cntr=0.3,0.1