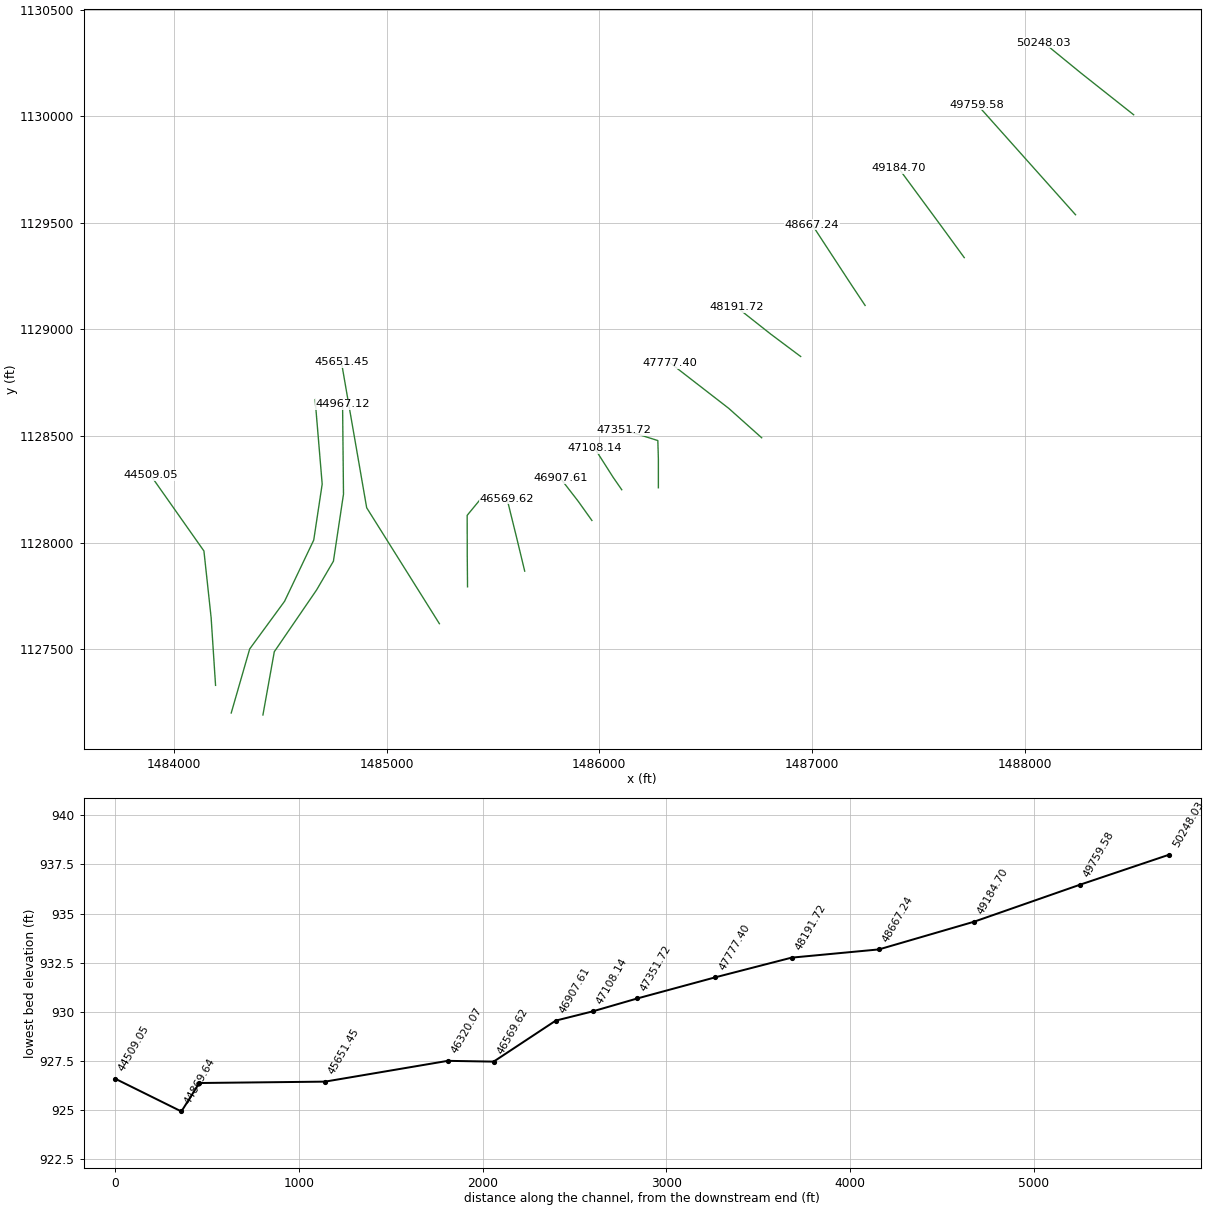
HEC-RAS study 12mile_Combined.prj: 12mile Creek Combined Model

--- 12mile_Combined.g07 (geometry) --- (continued)

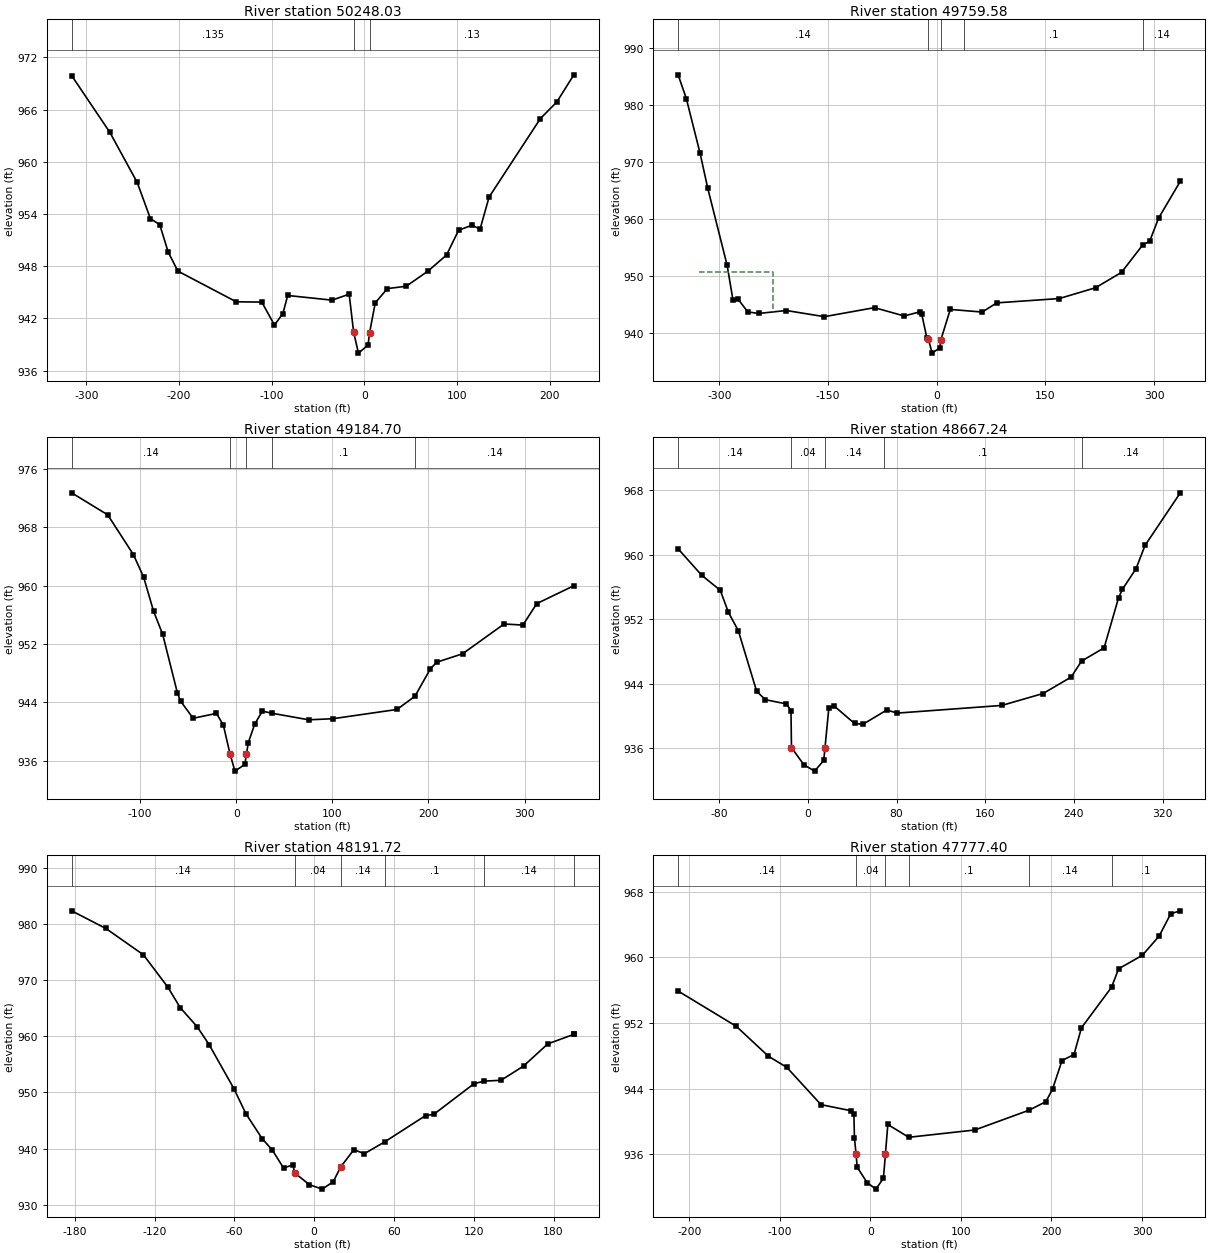
Type RM Length L Ch R = 1 ,50248.03,494.5609,488.4489,459.1877
XS GIS Cut Line= 3
     1488513.375   1130006.65617   1488265.97867   1130201.96883
   1488090.19685   1130345.19849
#Sta/Elev= 30
 -315.82  969.91 -274.55  963.38 -245.05  957.62 -230.84  953.47 -220.75  952.77
 -211.61  949.61 -201.17  947.43 -138.13   943.9 -110.62  943.87  -96.97  941.23
  -87.85  942.55  -82.69  944.63  -34.81  944.09  -16.34  944.78  -11.49   940.4
   -6.33     938    4.04  938.92    5.72  940.36   11.81  943.78   24.94  945.42
   45.22  945.69   68.71  947.43   88.75  949.28  101.78  952.13  116.22  952.71
  124.93  952.26  134.68  955.95  190.02  964.97   207.7  966.87  226.13     970
#Mann= 3 ,0,0
 -315.82    .135       0  -11.49     .04       0    5.72     .13       0
Bank Sta=-11.49,5.72
XS Rating Curve= 0 ,0
Exp/Cntr=0.3,0.1

Type RM Length L Ch R = 1 ,49759.58,514.6816,574.8795,496.1618
XS GIS Cut Line= 3
   1488239.93701   1129537.90518   1488001.17782   1129804.57218
   1487777.69619   1130054.39895
#Sta/Elev= 30
 -356.99  985.24 -345.69  981.09 -326.82  971.56 -316.05  965.34 -289.38  951.88
 -281.36  945.83 -274.06  945.88 -260.83  943.69    -246  943.41 -207.57  943.93
 -155.19  942.85  -85.92  944.43  -44.97  942.97  -23.02  943.71  -20.88  943.36
  -13.68  939.14  -11.49  938.86   -6.33  936.46    4.04  937.38    5.72  938.82
   18.66  944.12   62.69  943.66   82.85  945.27  169.22  946.03  219.15  947.92
  255.02  950.62  284.33955.4391  293.79  956.05  306.26  960.15  336.14  966.58
#Mann= 5 ,-1,0
 -356.99     .14       0-11.4899     .04       05.720001     .14       0
37.85999      .1       0  284.33     .14       0
#XS Ineff= 1 ,-1
 -327.79 -225.56  950.71
Permanent Ineff=
       F
Bank Sta=-11.49,5.72
XS Rating Curve= 0 ,0
Exp/Cntr=0.3,0.1

Type RM Length L Ch R = 1 ,49184.70,508.0684,517.4625,498.2339
XS GIS Cut Line= 3
   1487716.63648   1129336.80479   1487616.00492   1129474.42126
   1487406.99967   1129757.39501
#Sta/Elev= 30
 -171.12  972.71 -133.58  969.69 -106.87  964.24  -96.22  961.15  -85.88  956.47
  -76.46  953.33  -61.21  945.33  -57.86  944.18  -44.79  941.82  -20.54  942.49
  -13.35  940.89   -6.49  936.98   -1.33  934.58    9.04   935.5   10.72  936.94
   12.54  938.46   19.27  941.02   27.22   942.8   36.78 942.522   75.42  941.61
  100.49  941.76   167.3  943.03  185.96944.8469  201.86  948.57  208.33  949.49
  235.49  950.66  278.63  954.74   298.2  954.59  312.57  957.53  351.16  959.98
#Mann= 5 ,-1,0
 -171.12     .14       0   -6.49     .04       0   10.72     .14       0
   36.78      .1       0  185.96     .14       0
Bank Sta=-6.49,10.72
XS Rating Curve= 0 ,0
Exp/Cntr=0.3,0.1

Type RM Length L Ch R = 1 ,48667.24,459.8952,475.5148,473.1491
XS GIS Cut Line= 3
   1487250.35171   1129112.55676   1487186.11549   1129208.91142
   1487001.21916   1129491.02986
#Sta/Elev= 30
 -117.05  960.72  -95.89  957.46  -79.01  955.58  -71.67  952.85  -62.76  950.58
  -46.17  943.06  -38.27  942.02  -19.33   941.5  -15.22  940.66  -14.77  936.09
    -3.6  933.96    6.06  933.17   14.34  934.49   15.44  936.02   18.95  941.01
   23.31  941.29   42.11  939.08   49.62  938.97   71.33  940.75   80.57  940.36
  174.92  941.31  212.27  942.79  237.61  944.83  246.91   946.8  267.31  948.45
  280.41  954.68  283.83  955.71  296.06  958.24  304.22  961.14  336.06  967.66
#Mann= 5 ,-1,0
 -117.05     .14       0  -14.77     .04       0   15.44     .14       0
68.49001      .1       0  246.91     .14       0
Bank Sta=-14.77,15.44
XS Rating Curve= 0 ,0
Exp/Cntr=0.3,0.1

Type RM Length L Ch R = 1 ,48191.72,414.4393,414.3247,402.1916
XS GIS Cut Line= 3
   1486947.39961   1128873.08169   1486806.34055   1128978.33333
   1486647.91995    1129103.1168
#Sta/Elev= 30
 -182.38  982.42 -156.63  979.27 -128.36  974.56 -110.03  968.79 -100.64  965.11
  -88.07  961.76  -79.03  958.55  -60.37  950.69  -51.31   946.2  -39.07  941.75
  -31.53  939.74  -23.01  936.52   -15.9  937.09  -14.77  935.67    -3.6  933.54
    6.06  932.75   14.34  934.07   19.91  936.69   29.81  939.78    37.8  939.08
   53.27  941.22   83.87  945.89   89.89  946.09  120.19  951.56  127.65  952.02
  140.57  952.18  157.45  954.71  175.67  958.67  195.26  960.37  195.29  960.37
#Mann= 6 ,-1,0
 -182.38     .14       0  -14.77     .04       0   19.91     .14       0
   53.27      .1       0  127.65     .14       0  195.26      .1       0
Bank Sta=-14.77,19.91
XS Rating Curve= 0 ,0
Exp/Cntr=0.3,0.1

Type RM Length L Ch R = 1 ,47777.40,468.511,425.6777,370.561
XS GIS Cut Line= 3
   1486764.02231   1128491.89567   1486609.07415   1128629.91699
   1486334.33432   1128842.15682
#Sta/Elev= 30
  -212.4   955.9 -148.15   951.6 -112.73  947.96   -92.3  946.59  -54.59  942.05
  -21.47  941.31  -18.25  940.93  -17.65  938.02  -15.86     936  -14.55  934.41
    -3.6  932.54    6.06  931.75   14.34  933.07   16.57  935.98   16.57  936.03
   19.22  939.63   42.34  938.07  115.31  938.96  174.93  941.36  193.82  942.41
  201.21  943.96  211.64  947.43  224.87  948.16   233.1  951.42  266.31  956.36
  274.13  958.61   300.4  960.26   318.9   962.6  331.74  965.33  342.28  965.68
#Mann= 6 ,-1,0
  -212.4     .14       0  -15.86     .04       016.57001     .14       0
   42.34      .1       0  174.93     .14       0  266.31      .1       0
Bank Sta=-15.86,16.57
XS Rating Curve= 0 ,0
Exp/Cntr=0.3,0.1

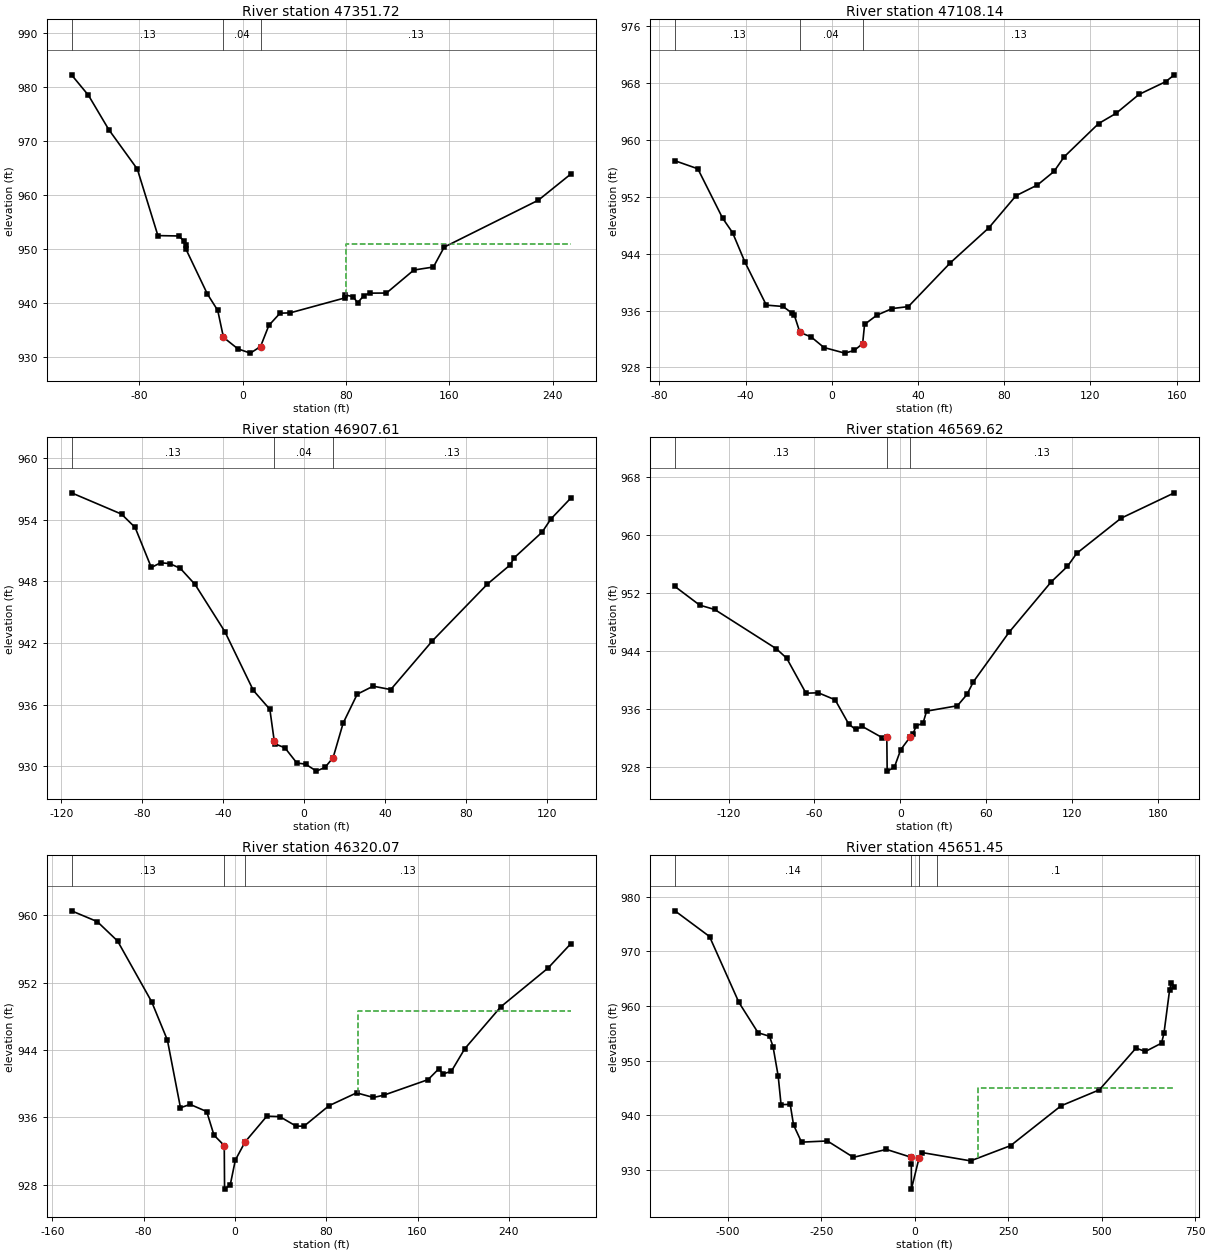
Type RM Length L Ch R = 1 ,47351.72,223.5139,243.5831,252.1278
BEGIN DESCRIPTION:
TWE_26X
END DESCRIPTION:
XS GIS Cut Line= 4
   1486278.34449   1128257.52034   1486278.29724   1128391.04462
   1486275.74016     1128478.875   1486118.18766   1128528.35433
#Sta/Elev= 30
 -132.37  982.22 -119.24  978.42 -103.55  972.08  -81.43  964.76  -65.51  952.44
  -49.39  952.37  -45.33  951.45  -44.01  950.76   -43.9  949.98  -27.24  941.63
   -19.2  938.58  -14.77  933.59    -3.6  931.46    6.06  930.67   13.93  931.89
   20.38  935.81   29.03  938.07   36.87  938.13   79.22   940.9   79.64  941.45
   85.77   941.1   89.02  939.98   93.93  941.34   98.42  941.78  111.37   941.8
  132.57  946.06  147.72  946.62  156.08  950.31  228.95     959  254.16  963.86
#Mann= 3 ,-1,0
 -132.37     .13       0  -14.77     .04       013.92999     .13       0
#XS Ineff= 2 , 0
                           80.12          950.95
Permanent Ineff=
       F       F
Bank Sta=-14.77,13.93
XS Rating Curve= 0 ,0
Exp/Cntr=0.3,0.1

Type RM Length L Ch R = 1 ,47108.14,198.8914,200.5286,202.0965
XS GIS Cut Line= 3
   1486105.99541   1128248.25525   1486064.94915   1128307.43832
   1485979.03871   1128442.03182
#Sta/Elev= 30
  -72.74  957.06  -62.12  955.93  -50.61  948.98     -46  946.95  -40.19  942.76
  -30.34  936.76  -22.59  936.57  -18.64  935.68  -17.38  935.37  -14.77932.9301
   -9.52  932.28    -3.6   930.8    6.06  930.01   10.37  930.38   14.34  931.33
   15.24  934.05   20.91  935.34   28.07  936.28   35.54  936.55   55.06  942.72
   72.89  947.63   85.48  952.14   95.43  953.65  103.11  955.55   107.8   957.6
  123.82  962.29  131.89  963.72  142.53  966.38  154.88  968.17  158.95  969.14
#Mann= 3 ,-1,0
  -72.74     .13       0  -14.77     .04       0   14.34     .13       0
Bank Sta=-14.77,14.34
XS Rating Curve= 0 ,0
Exp/Cntr=0.3,0.1

Type RM Length L Ch R = 1 ,46907.61,353.2054,337.9913,322.8637
XS GIS Cut Line= 3
   1485965.67454   1128104.11581   1485900.76411   1128194.79954
   1485817.71719   1128301.71063
#Sta/Elev= 30
    -115   956.6  -90.27  954.53  -83.55  953.23  -75.55  949.34  -70.94   949.8
  -66.46  949.72  -61.24  949.26  -53.92  947.69  -39.21  943.11  -25.12  937.39
  -16.95  935.55  -14.77  932.46  -14.55   932.2   -9.52  931.81    -3.6  930.33
     .73  930.22    6.06  929.54   10.37  929.91   14.34  930.86   19.29  934.21
   26.24  937.02   34.11   937.8   42.82  937.47   63.41  942.21   90.62  947.73
  101.73  949.57  103.88  950.29  117.61  952.77  122.01  954.06  131.89   956.1
#Mann= 3 ,-1,0
    -115     .13       0  -14.77     .04       0   14.34     .13       0
Bank Sta=-14.77,14.34
XS Rating Curve= 0 ,0
Exp/Cntr=0.3,0.1

Type RM Length L Ch R = 1 ,46569.62,253.0367,249.5448,234.6748
XS GIS Cut Line= 3
   1485649.71391   1127866.42913   1485612.71818   1128019.44948
   1485566.66667   1128205.29987
#Sta/Elev= 30
 -157.45   952.9 -140.15  950.33 -129.68  949.73  -86.55  944.31  -79.36  943.01
   -65.9  938.19  -57.32  938.25  -45.53  937.28  -36.04  933.94   -31.3   933.2
  -26.56  933.61  -12.79  932.08   -9.43  932.12   -9.17  927.45   -4.18  927.97
     .28   930.4    6.91  932.16    8.74  932.52   11.16  933.71   15.84  934.04
   18.37  935.72   39.89  936.46   46.58  938.02    51.1  939.78   75.86  946.56
  105.35  953.52  116.79  955.68  123.24  957.47  154.21  962.31  191.45  965.81
#Mann= 3 ,0,0
 -157.45     .13       0   -9.43     .04       0    6.91     .13       0
Bank Sta=-9.43,6.91
XS Rating Curve= 0 ,0
Exp/Cntr=0.3,0.1

Type RM Length L Ch R = 1 ,46320.07,355.7927,668.618,610.6862
XS GIS Cut Line= 4
   1485380.84941   1127792.95899   1485379.57185   1127937.06726
   1485379.11319    1128128.0292   1485444.48228   1128207.20899
#Sta/Elev= 30
 -143.32  960.53 -120.76  959.25 -102.96  956.95  -73.09  949.74  -59.27  945.18
  -47.81  937.15  -39.37  937.55  -24.83   936.7  -18.44   933.9   -9.43  932.66
   -9.17  927.49   -4.18     928     .28  930.94     8.8  933.09   27.88  936.15
    39.2   936.1   53.54  934.97   60.45  934.96   82.32  937.39  106.58  938.92
  121.29  938.37  130.33  938.64  169.23  940.49  178.52  941.76  182.38  941.17
  189.58  941.47  201.39  944.16  232.91  949.13  274.41  953.74  294.43  956.64
#Mann= 3 ,-1,0
 -143.32     .13       0-9.42999     .04       08.800003     .13       0
#XS Ineff= 2 , 0
                          107.42          948.64
Permanent Ineff=
       F       F
Bank Sta=-9.43,8.8
XS Rating Curve= 0 ,0
Exp/Cntr=0.3,0.1

Type RM Length L Ch R = 1 ,45651.45,594.5614,684.3304,641.0182
XS GIS Cut Line= 3
   1485248.56266    1127619.9101    1484906.6145   1128163.62927
   1484787.67585   1128847.52559
#Sta/Elev= 30
    -642  977.44 -549.45  972.73 -470.79  960.65 -419.48  955.09 -388.91  954.45
 -379.49  952.55 -365.67  947.16 -357.98  941.92 -333.47  941.96 -324.59   938.2
 -303.25  935.04 -234.06  935.26 -164.41  932.26     -76  933.71   -9.89  932.27
   -9.43   931.1   -9.17  926.43   11.24  932.12    19.5  933.13  149.23  931.61
  256.22   934.4  391.24   941.7  493.77  944.63  591.71  952.27  617.05  951.66
  660.24  953.19  666.64  954.99  681.75  962.92  686.42   964.3  694.47  963.51
#Mann= 4 ,-1,0
    -642     .14       0-9.89001    .045       011.23999     .14       0
59.15997      .1       0
#XS Ineff= 2 , 0
                             170             945
Permanent Ineff=
       F       F
Bank Sta=-9.89,11.24
XS Rating Curve= 0 ,0
Exp/Cntr=0.5,0.3

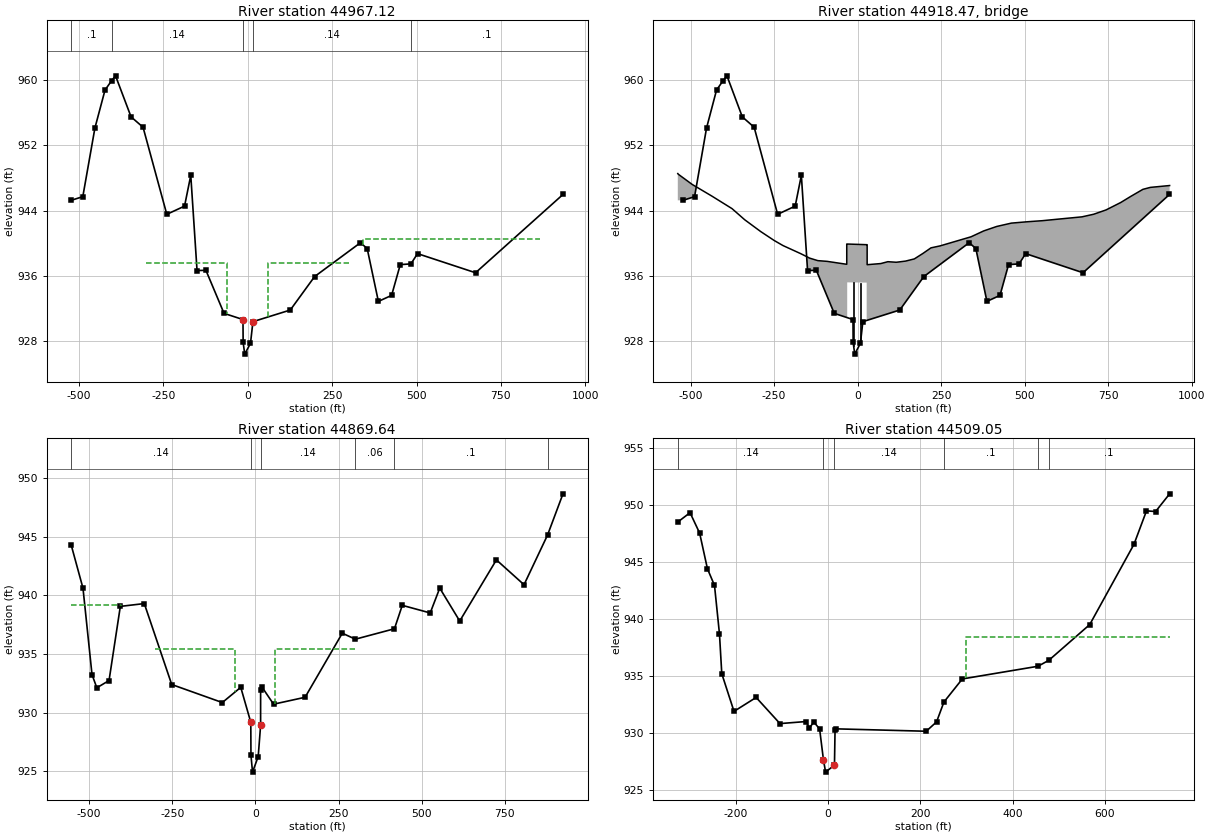
Type RM Length L Ch R = 1 ,44967.12,106.6229,97.47809,96.2407
BEGIN DESCRIPTION:
SC Hwy 178 (TWE_25) - US
END DESCRIPTION:
XS GIS Cut Line= 6
   1484418.68406   1127191.89534   1484472.19357   1127488.53675
   1484670.55512    1127777.4416   1484750.20636    1127913.0643
    1484797.5666   1128227.36483   1484793.26115   1128649.30217
#Sta/Elev= 30
-522.704  945.26-488.133  945.71-452.274  954.15-422.392  958.81-402.527  959.98
-391.194  960.56-345.281  955.52-309.741  954.24-239.452  943.54-186.905  944.55
-168.459  948.33-149.881  936.63-123.598  936.66 -69.979  931.37  -13.86  930.61
 -13.409   927.8  -8.664  926.36   8.382  927.69  15.608  930.35  126.22  931.78
   198.2  935.89 333.929  940.05 353.879  939.34 387.059  932.84 426.207  933.58
  451.87  937.36 483.378  937.45 502.999  938.71 674.812  936.36 933.632  945.98
#Mann= 5 ,-1,0
-522.704      .1       0-402.527     .14       0-13.8598    .045       0
15.60797     .14       0 483.378      .1       0
#XS Ineff= 3 ,-1
    -300     -60   937.5      60     300   937.5  340.45  866.36  940.56
Permanent Ineff=
       F       F       F
Bank Sta=-13.86,15.608
XS Rating Curve= 0 ,0
Skew Angle= 20
Exp/Cntr=0.5,0.3

Type RM Length L Ch R = 3 ,44918.47,,,
BEGIN DESCRIPTION:
SC Hwy 178 (TWE_25) - TOR
Skew = 20 Degrees
END DESCRIPTION:
Bridge Culvert--1,0,-1,-1, 0
Deck Dist Width WeirC Skew NumUp NumDn MinLoCord MaxHiCord MaxSubmerge Is_Ogee
29.1,39.1,2.6,20, 46, 46, 937.35, , 0.95, 0, 0,0,,
-538.369-536.978-495.124 -435.97-376.018 -337.97-290.083 -249.62-223.384-170.526
-149.524-143.923-119.162 -91.254 -32.589 -32.589 -31.179  27.091  28.501  28.501
   69.34  90.511 115.704 142.908   143.2  169.68 195.315 218.873 219.475 246.716
 339.577 377.315 416.453 460.167  509.05 553.357 605.735 638.587 671.476 706.555
 743.607 787.491 817.918 854.011 876.273 934.054
  948.55  948.47  947.21  945.77  944.24  942.87  941.42  940.32   939.7  938.71
  938.28  938.16  937.85  937.76   937.4  939.89  939.89  939.81  939.81  937.35
  937.49  937.72  937.65  937.79  937.79  938.06  938.73   939.4  939.42  939.66
  940.78   941.5  942.05  942.46  942.63  942.76  942.97   943.1  943.23  943.55
  944.08  944.99  945.75  946.61  946.85  947.08
                                                                                
                                                  935.18  935.15
                                                                                
                                                                                
                                                
-554.419-536.978-495.124 -435.97-376.018 -337.97-290.083 -249.62-223.384-170.526
-149.524-143.923-119.162 -91.254 -32.589 -32.589 -31.179  27.091  28.501  28.501
   69.34  90.511 115.704 142.908   143.2  169.68 195.315 218.873 219.475 246.716
 339.577 377.315 416.453 460.167  509.05 553.357 605.735 638.587 671.476 706.555
 743.607 787.491 817.918 854.011 876.273 934.054
  948.55  948.47  947.21  945.77  944.24  942.87  941.42  940.32   939.7  938.71
  938.28  938.16  937.85  937.76   937.4  939.89  939.89  939.81  939.81  937.35
  937.49  937.72  937.65  937.79  937.79  938.06  938.73   939.4  939.42  939.66
  940.78   941.5  942.05  942.46  942.63  942.76  942.97   943.1  943.23  943.55
  944.08  944.99  945.75  946.61  946.85  947.08
                                                                                
                                                  935.22  935.14
                                                                                
                                                                                
                                                
Pier Skew, UpSta & Num, DnSta & Num=  ,-11.934, 4 ,-11.934, 4 , 3 , 3 , 0 ,,
       1       1       2       2
     925  933.18  933.18     936
       1       1       2       2
     925  933.18  933.18     936
Pier Skew, UpSta & Num, DnSta & Num=  ,7.987, 4 ,7.987, 4 , 3 , 3 , 0 ,,
       1       1       2       2
     925  933.18  933.18     936
       1       1       2       2
     925  933.18  933.18     936
Abutment Skew #Up #Dn= , 2 , 2
  -31.18  -22.99
  935.18  931.73
  -31.18  -22.99
  935.18  930.73
Abutment Skew #Up #Dn= , 2 , 2
   21.34   27.09
  930.89  935.15
   21.34   27.09
  930.89  935.14
BR Coef=-1 ,-1 , 0 ,, 0 ,,,0.8,0,2,0,
WSPro=,,,, 1 ,,,, 0 ,,,, 0 ,,,,-1 ,-1 ,-1 , 0 , 0 , 0 , 0 , 0
BC Design=,, 0 ,, 0 ,,,,,,
BC Use User HTab Curves=0
BC User HTab FreeFlow(D)= 0

Type RM Length L Ch R = 1 ,44869.64,347.6826,360.594,387.4614
BEGIN DESCRIPTION:
SC Hwy 178 (TWE_25) - DS
END DESCRIPTION:
XS GIS Cut Line= 6
   1484269.63222   1127201.15223   1484356.43832       1127501.5
     1484520.396   1127724.93077   1484657.63845   1128012.09022
   1484697.35728   1128274.56496   1484664.09678    1128670.8294
#Sta/Elev= 30
-553.855  944.32-518.212  940.61-491.121  933.24-476.659  932.11-439.917  932.73
-406.004  939.06-333.939   939.3-251.556  932.39 -99.532  930.85 -44.043  932.15
  -13.86  929.16 -13.409  926.35  -8.664  924.91   8.382  926.24  15.608   928.9
  15.665  931.88  20.504  932.14  54.549  930.71 149.289   931.3 261.141  936.77
  300.41  936.26 417.853  937.15 441.402  939.15 525.354   938.5 554.024  940.62
  614.07  937.81 724.306  943.03 807.337  940.91 878.152  945.16 924.385  948.67
#Mann= 6 ,-1,0
-553.855     .14       0-13.8599    .045       015.60797     .14       0
  300.41     .06       0 417.853      .1       0 878.152     .06       0
#XS Ineff= 3 ,-1
 -561.64 -403.25   939.2  -300.5   -60.5   935.4      60     300   935.4
Permanent Ineff=
       F       F       F
Bank Sta=-13.86,15.608
XS Rating Curve= 0 ,0
Skew Angle= 20
Exp/Cntr=0.5,0.3

Type RM Length L Ch R = 1 ,44509.05,237.2591,247.1265,233.693
XS GIS Cut Line= 4
   1484195.95112    1127330.7185   1484175.11778   1127648.42749
   1484141.26345   1127960.92815   1483891.26312   1128315.09547
#Sta/Elev= 30
 -325.68  948.48 -299.13   949.3 -278.32  947.51 -261.44  944.39 -246.11  942.93
 -235.34  938.69 -230.32   935.2 -203.83   931.9 -155.84  933.12 -104.17  930.83
  -47.69  931.01  -40.38  930.44  -30.83  930.97  -18.23  930.36    -9.9  927.65
   -5.26  926.58   13.97   927.2   15.23  930.29   17.12  930.37  212.89  930.16
  235.29  930.98  251.25  932.72  291.13  934.74  455.08  935.85  478.61  936.37
  567.32   939.5  663.24  946.53  690.39  949.46  710.08   949.4  740.55  950.95
#Mann= 6 ,-1,0
 -325.68     .14       0-9.89999     .04       0   13.97     .14       0
  251.25      .1       0  455.08     .06       0  478.61      .1       0
#XS Ineff= 2 , 0
                          300.16          938.42
Permanent Ineff=
       F       F
Bank Sta=-9.9,13.97
XS Rating Curve= 0 ,0
Exp/Cntr=0.3,0.1