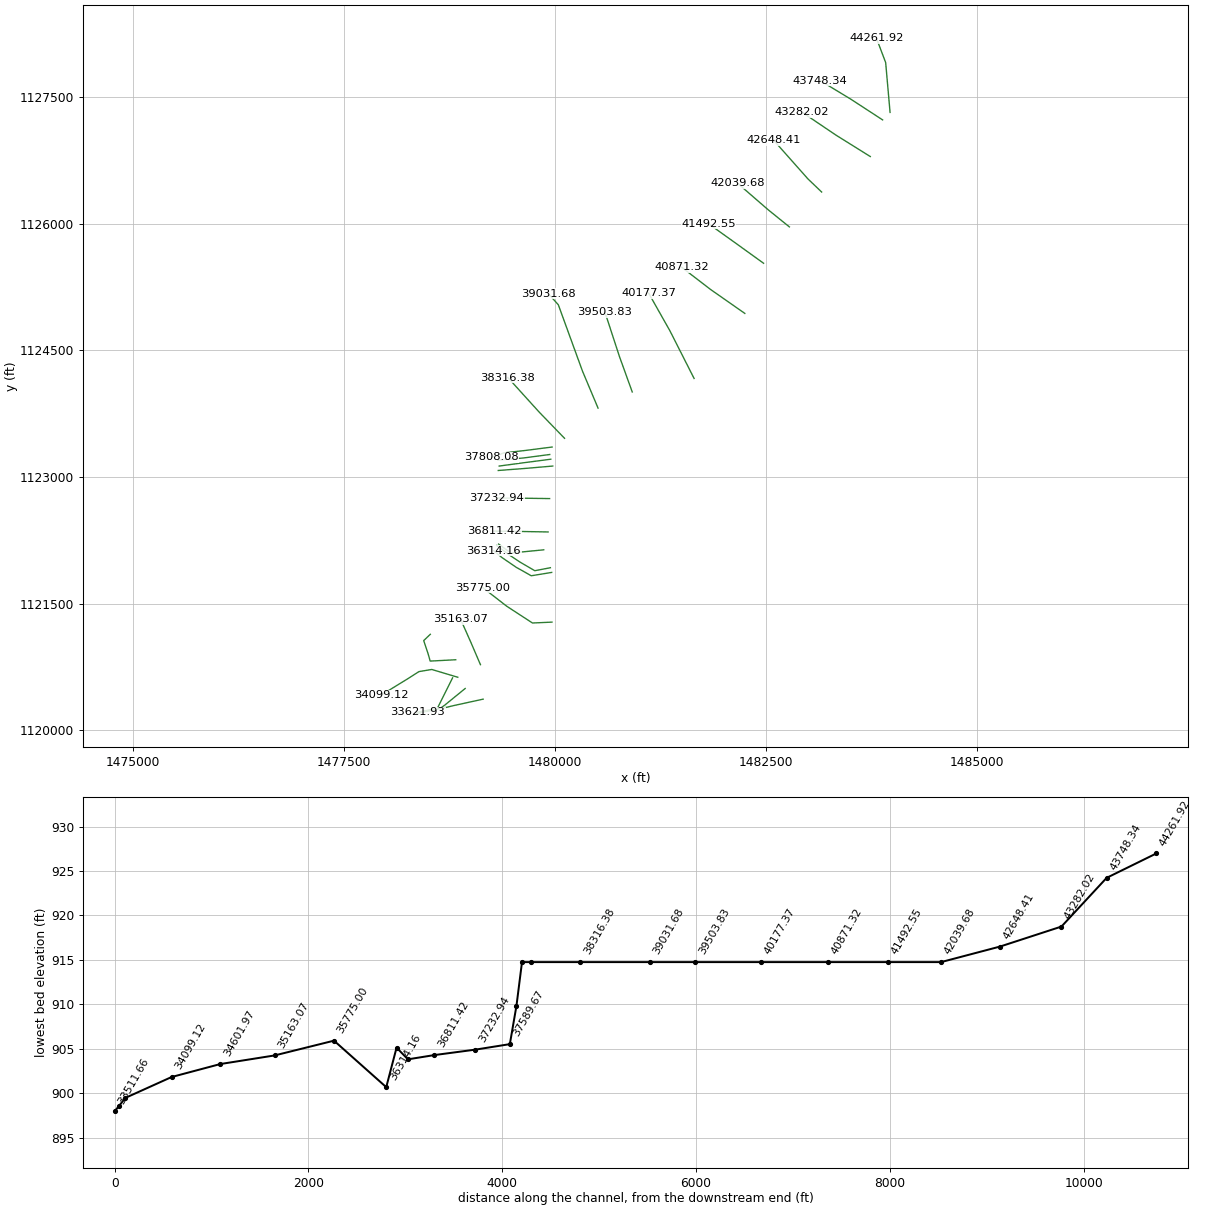
HEC-RAS study 12mile_Combined.prj: 12mile Creek Combined Model

--- 12mile_Combined.g07 (geometry) --- (continued)

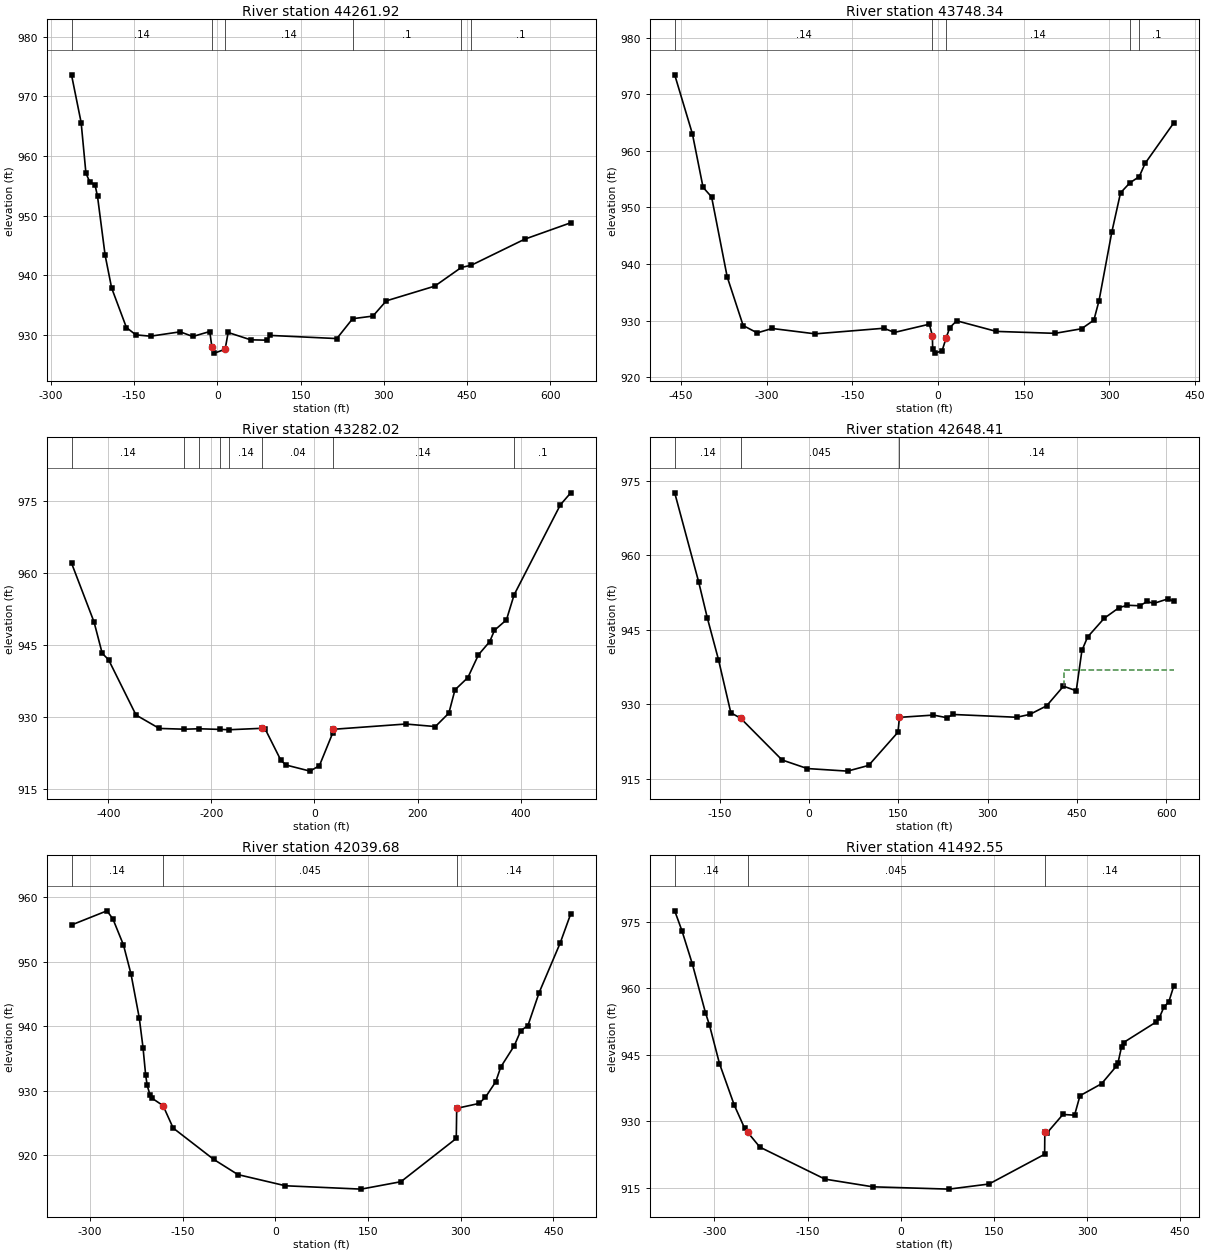
Type RM Length L Ch R = 1 ,44261.92,355.2933,513.582,597.9077
BEGIN DESCRIPTION:
TWE_24X
END DESCRIPTION:
XS GIS Cut Line= 4
   1483968.18602   1127318.16699    1483945.0351   1127579.95341
   1483916.10269   1127908.64272    1483807.2851   1128195.50033
#Sta/Elev= 30
 -262.81  973.63 -245.44  965.63 -236.81  957.13 -229.54  955.61 -220.51  955.21
 -215.94  953.26 -202.27  943.41 -190.53  937.91 -163.86  931.27 -146.81  930.04
 -120.46  929.82  -67.04  930.55  -44.29  929.77  -13.69   930.6    -9.9  928.05
   -5.26  926.98   14.02  927.63   19.45  930.44   60.13  929.21   89.84  929.15
   95.06  929.95  215.24  929.42  243.76  932.75  280.33  933.19  304.38  935.74
  391.77  938.21  439.57  941.34  457.77  941.72  553.83  946.08  636.76  948.83
#Mann= 6 ,-1,0
 -262.81     .14       0-9.89999     .04       014.01999     .14       0
  243.76      .1       0  439.57     .06       0  457.77      .1       0
Bank Sta=-9.9,14.02
XS Rating Curve= 0 ,0
Exp/Cntr=0.3,0.1

Type RM Length L Ch R = 1 ,43748.34,466.6915,466.3208,455.0912
XS GIS Cut Line= 3
   1483879.97835   1127229.59022   1483501.50525   1127476.11811
   1483140.39337   1127694.86844
#Sta/Elev= 30
 -460.95  973.45 -429.95     963 -411.31  953.55 -396.37  951.85  -369.1  937.73
 -341.15  929.11 -316.54  927.81 -290.43  928.59    -215  927.64  -94.83  928.63
  -76.25  927.89  -15.18  929.35    -9.9   927.3   -9.38  924.95   -5.26  924.23
    7.09  924.64   13.97  926.85   20.48  928.73   32.65  929.95  102.06  928.07
  204.74  927.73  251.16  928.54   272.8  930.06  281.76  933.48  304.22  945.64
  319.46  952.58  335.97  954.36   352.2  955.44  362.44  957.78  412.94  964.99
#Mann= 5 ,-1,0
 -460.95     .14       0-9.89999    .045       0   13.97     .14       0
  335.97     .06       0   352.2      .1       0
Bank Sta=-9.9,13.97
XS Rating Curve= 0 ,0
Exp/Cntr=0.3,0.1

Type RM Length L Ch R = 1 ,43282.02,652.4951,633.6125,557.1238
XS GIS Cut Line= 3
   1483734.14469   1126795.56135    1483327.8937   1127049.03379
   1482921.64304   1127323.34022
#Sta/Elev= 30
 -471.63  962.13 -427.84  949.83 -412.07  943.32 -399.67  941.97 -346.42  930.45
 -301.27  927.65 -252.35  927.49 -224.41  927.58 -183.08  927.45 -165.27  927.38
 -101.45  927.68  -95.59  927.51   -65.2     921  -55.45  920.03   -8.62  918.75
    9.62   919.9   35.01   926.6   35.13  927.46  177.27  928.57  234.64  928.04
  260.86  930.85  272.69  935.69  297.77  938.26  318.32  943.01  340.12  945.74
  349.38  948.11  372.65  950.29  387.43  955.49  477.31  974.27   497.4  976.77
#Mann= 8 ,-1,0
 -471.63     .14       0 -252.35    .045       0 -224.41     .14       0
 -183.08    .045       0 -165.27     .14       0 -101.45     .04       0
   35.13     .14       0  387.43      .1       0
Bank Sta=-101.45,35.13
XS Rating Curve= 0 ,0
Exp/Cntr=0.3,0.1

Type RM Length L Ch R = 1 ,42648.41,585.2552,608.7328,625.9509
XS GIS Cut Line= 3
   1483157.75459   1126375.42159   1482994.55971   1126531.67192
   1482588.30906   1126990.00623
#Sta/Elev= 30
 -225.36  972.56 -185.22  954.66  -170.6  947.37 -151.85  938.96  -131.1  928.25
 -114.65  927.16-45.0831  918.75 -2.6883  917.02 64.8694   916.5100.3117  917.65
 149.659  924.35  152.03  927.33  209.18  927.79  231.65  927.26  242.35  927.91
  349.03  927.35   371.1  927.93  399.21  929.65  427.52  933.61  448.97  932.69
  458.51   940.8  468.07  943.52  495.96  947.29     521  949.44  534.97  949.91
  555.54  949.81  568.21  950.67  579.03  950.28  602.26  951.17  613.04  950.72
#Mann= 3 ,-1,0
 -225.36     .14       0 -114.65    .045       0  152.03     .14       0
#XS Ineff= 2 , 0
                          427.84          936.96
Permanent Ineff=
       F       F
Bank Sta=-114.65,152.03
XS Rating Curve= 0 ,0
Exp/Cntr=0.3,0.1

Type RM Length L Ch R = 1 ,42039.68,546.5081,547.122,564.7739
XS GIS Cut Line= 3
   1482775.80938   1125962.22638   1482522.33661   1126167.08793
   1482157.75262    1126483.0607
#Sta/Elev= 30
  -330.3  955.66  -272.9  957.85  -263.3   956.6 -246.14  952.56 -233.92  948.05
 -220.56  941.26  -214.5  936.67 -210.21   932.4  -207.7   930.8 -203.31  929.37
 -199.51   928.8 -182.03  927.68  -165.7  924.21 -100.25  919.37  -60.85     917
   16.12  915.27  138.77  914.75  203.12   915.9  292.71   922.6  293.44  927.26
  329.69  928.02  340.03  928.99  356.65  931.38  364.74  933.65  386.71  936.97
  397.24  939.31  408.68  940.06  426.97   945.2  460.97  952.86  478.06  957.38
#Mann= 3 ,-1,0
  -330.3     .14       0 -182.03    .045       0  293.44     .14       0
Bank Sta=-182.03,293.44
XS Rating Curve= 0 ,0
Exp/Cntr=0.3,0.1

Type RM Length L Ch R = 1 ,41492.55,619.7957,621.235,614.1196
XS GIS Cut Line= 3
   1482470.25328   1125531.66995    1482171.6414   1125746.94816
   1481817.47408   1126000.42093
#Sta/Elev= 30
 -363.79  977.43 -352.06  972.91  -335.3  965.42 -314.32   954.5 -307.85   951.7
 -291.69  943.02  -267.8  933.63 -251.06  928.41 -246.12  927.51  -226.7  924.21
 -121.85     917  -44.88  915.27   77.77  914.75  142.12   915.9  231.71   922.6
  232.04  927.63  236.14   927.5  261.19  931.57  279.88   931.4  288.61  935.79
  323.38  938.49  347.08  942.42  349.65  943.09  355.48  946.77  358.79  947.77
  411.36   952.4  416.47  953.38  423.51  955.67  431.75     957  439.86   960.6
#Mann= 3 ,-1,0
 -363.79     .14       0 -246.12    .045       0  232.04     .14       0
Bank Sta=-246.12,232.04
XS Rating Curve= 0 ,0
Exp/Cntr=0.3,0.1

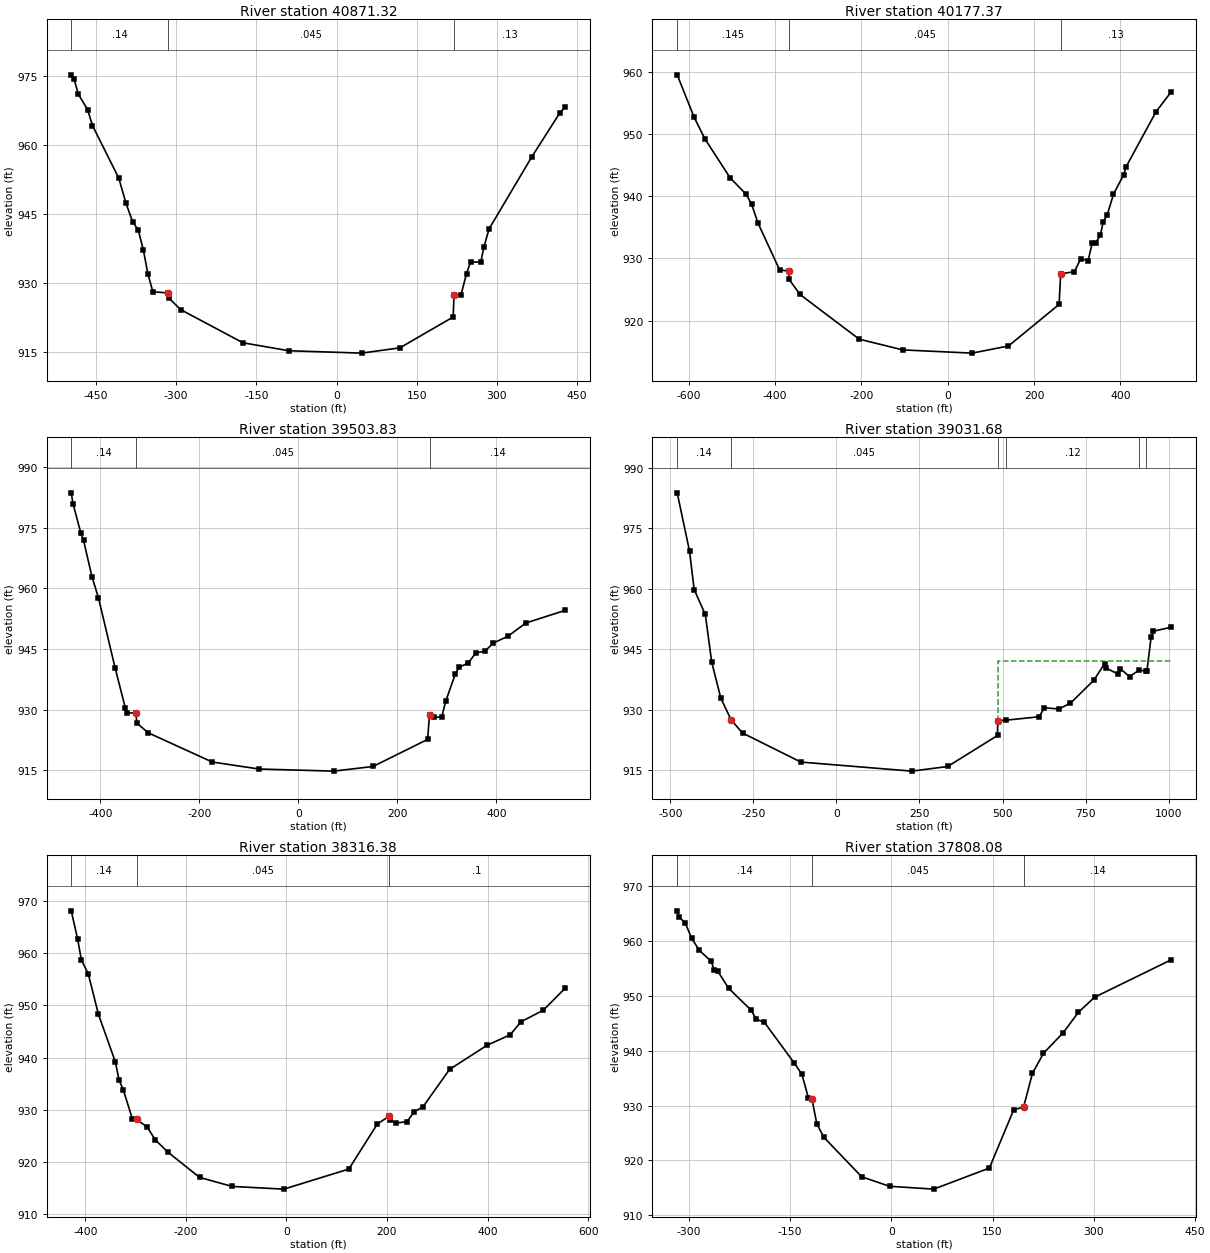
Type RM Length L Ch R = 1 ,40871.32,814.6174,693.9553,607.2974
XS GIS Cut Line= 3
   1482248.03051   1124937.91896   1481845.25197   1125219.16929
   1481501.50131   1125483.05873
#Sta/Elev= 30
  -496.3  975.24 -491.19  974.33 -482.95  971.02  -465.6  967.65 -456.56  964.22
 -407.22  952.75 -393.99  947.35 -381.24  943.24 -371.02  941.54 -361.35  937.15
 -352.81  931.92 -343.56  928.08  -314.6  927.83-313.257  926.67-291.667  924.21
-175.041     917-89.4288  915.27 46.9984  914.75118.5712   915.9 218.224   922.6
  219.92  927.42  232.71  927.31  243.23  932.05  250.69   934.5  269.96  934.58
  276.03  937.92   285.4  941.75  365.02  957.34  417.52  966.91  428.32  968.31
#Mann= 3 ,-1,0
  -496.3     .14       0  -314.6    .045       0  219.92     .13       0
Bank Sta=-314.6,219.92
XS Rating Curve= 0 ,0
Exp/Cntr=0.3,0.1

Type RM Length L Ch R = 1 ,40177.37,701.7444,673.5378,623.1429
XS GIS Cut Line= 3
   1481647.33497   1124167.08399   1481361.55217   1124730.74049
   1481109.13944   1125177.50262
#Sta/Elev= 30
 -626.95  959.58 -587.84  952.77 -562.86  949.27 -504.31  942.99  -467.5  940.36
 -454.61  938.75 -439.87  935.72 -389.82  928.18 -368.29  927.95 -368.04  926.67
 -342.61  924.21 -205.24     917 -104.39  915.27    56.3  914.75  140.61   915.9
  257.99   922.6   261.6  927.52  293.41  927.87   308.1  929.96  325.12  929.64
   334.6  932.45  343.18  932.55   353.3  933.73  360.38   935.9  369.33  936.98
     384  940.35   407.6   943.5  413.14  944.76  482.48  953.62  518.15  956.88
#Mann= 3 ,-1,0
 -626.95    .145       0 -368.29    .045       0   261.6     .13       0
Bank Sta=-368.29,261.6
XS Rating Curve= 0 ,0
Exp/Cntr=0.3,0.1

Type RM Length L Ch R = 1 ,39503.83,458.49,472.1489,560.1823
XS GIS Cut Line= 3
   1480914.69455   1124007.36122   1480761.91667   1124430.97343
   1480591.77723   1124951.80774
#Sta/Elev= 30
 -458.58  983.63 -455.09  980.98 -439.42  973.77 -433.73  971.85 -416.79  962.89
 -403.58  957.63 -370.14  940.38 -349.48  930.44 -346.07  929.15 -327.48  929.15
-326.506  926.67-302.632  924.21-173.671     917 -79.003  915.27  71.854  914.75
 150.997   915.9  261.19   922.6  265.12  928.75  274.87  928.05  289.83  928.17
  297.86  932.07  317.13  938.76   324.9  940.46  343.56  941.51  358.04  943.95
   377.4  944.48  394.05  946.46  423.29  948.12  459.84  951.42  539.66  954.56
#Mann= 3 ,-1,0
 -458.58     .14       0 -327.48    .045       0  265.12     .14       0
Bank Sta=-327.48,265.12
XS Rating Curve= 0 ,0
Exp/Cntr=0.3,0.1

Type RM Length L Ch R = 1 ,39031.68,611.2044,715.2979,1057.36
XS GIS Cut Line= 4
    1480509.8645   1123816.19882   1480325.40256   1124254.56759
   1480039.26969   1125040.27362   1479921.75591   1125170.36811
#Sta/Elev= 30
  -479.1  983.83 -442.03  969.38 -428.07  959.82 -394.54  953.64  -375.3  941.84
 -347.92  932.88  -317.1   927.5  -282.5  924.21    -107     917  227.13  914.75
  334.83   915.9  484.79   923.6  485.34  927.28  510.95   927.4  610.09  928.25
  625.97  930.49   669.3  930.17  704.09   931.6  774.34  937.29  807.23  941.44
  812.52   940.3  848.35  938.81  854.47  940.17  881.96  938.21  911.23  939.84
  930.77  939.57  934.26  939.53  946.86  947.92  953.72  949.48    1008  950.48
#Mann= 6 ,-1,0
  -479.1     .14       0  -317.1    .045       0  485.34     .12       0
  510.95     .12       0  911.23     .06       0  930.77     .14       0
#XS Ineff= 2 , 0
                             486             942
Permanent Ineff=
       F       F
Bank Sta=-317.1,485.34
XS Rating Curve= 0 ,0
Exp/Cntr=0.3,0.1

Type RM Length L Ch R = 1 ,38316.38,404.1435,508.2958,1291.599
XS GIS Cut Line= 3
   1480112.60958   1123458.74934   1479810.52559      1123771.25
   1479442.46949   1124177.50066
#Sta/Elev= 30
 -427.92  968.15 -415.07  962.65 -407.85  958.75 -394.05  956.05 -373.89   948.3
 -340.04  939.11 -332.91  935.69 -324.45  933.81 -306.31   928.2 -298.02  928.12
 -277.05  926.67 -260.75  924.21 -236.02  921.87 -172.72     917  -108.1  915.27
   -5.12  914.75  124.12   918.6  180.89  927.26  203.56  928.69  205.54  928.01
  218.31  927.42  239.73  927.71  254.53  929.63  271.27   930.5  324.41  937.72
  398.97  942.35  444.86  944.36  466.59  946.87  511.07  949.09   554.9  953.36
#Mann= 3 ,-1,0
 -427.92     .14       0 -298.02    .045       0  203.56      .1       0
Bank Sta=-298.02,203.56
XS Rating Curve= 0 ,0
Exp/Cntr=0.3,0.1

Type RM Length L Ch R = 1 ,37808.08,94.4441,93.02459,116.6445
BEGIN DESCRIPTION:
TWE_23USX
END DESCRIPTION:
XS GIS Cut Line= 4
   1479966.13451   1123355.31037   1479652.45768   1123315.19062
   1479398.33268   1123286.39469   1479247.14206      1123234.25
#Sta/Elev= 30
 -317.04  965.54 -314.47  964.45 -305.15  963.31 -295.64  960.53 -284.13   958.3
 -266.39  956.31 -262.58  954.73 -257.28  954.59 -240.85   951.4 -207.77  947.44
  -199.7  945.73 -187.95   945.2 -143.68  937.76 -132.31   935.7  -122.7  931.37
 -117.55  931.21 -110.22  926.67  -99.84  924.21  -43.77     917   -2.61  915.27
   62.98  914.75   145.3   918.6  181.46  929.26   195.9  929.69  209.03  935.86
  225.46  939.55  254.95  943.33  277.13  947.02  301.04  949.77  414.88  956.62
#Mann= 3 ,-1,0
 -317.04     .14       0 -117.55    .045       0   195.9     .14       0
Bank Sta=-117.55,195.9
XS Rating Curve= 0 ,0
Exp/Cntr=0.5,0.3

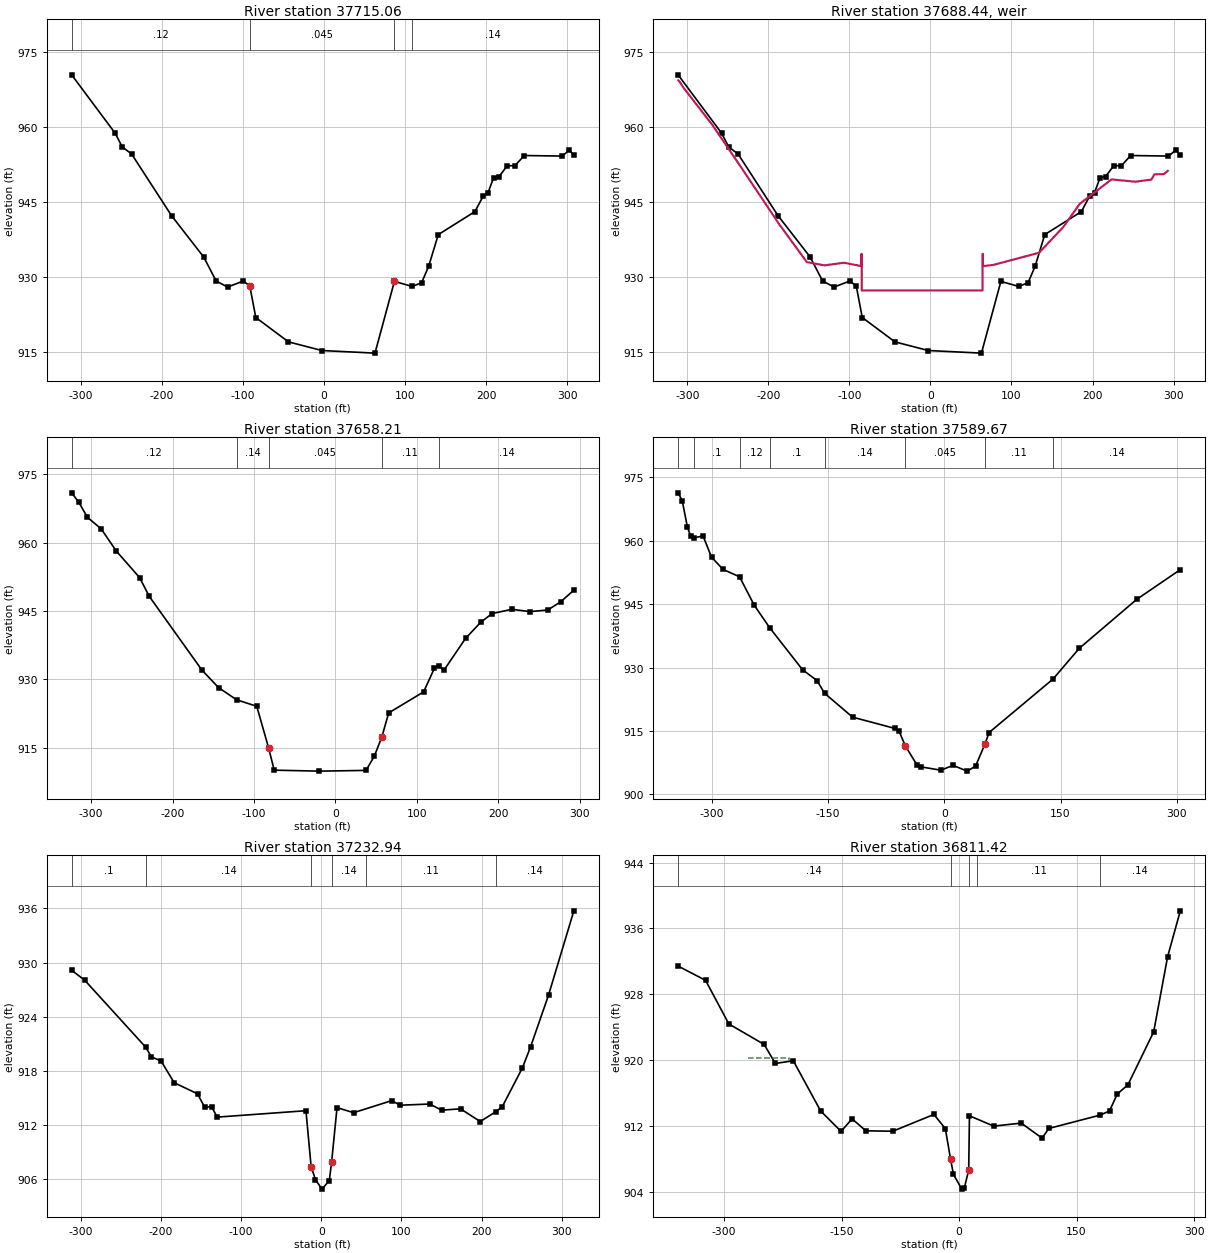
Type RM Length L Ch R = 1 ,37715.06,56.72282,56.84711,65.36195
BEGIN DESCRIPTION:
Weir N.of Gravley Rd (TWE_23) - US
END DESCRIPTION:
XS GIS Cut Line= 3
   1479937.71161   1123266.88353    1479628.2185   1123225.82841
   1479321.88353   1123200.56365
#Sta/Elev= 30
 -311.27  970.38 -257.65  958.72 -248.81  955.96 -237.32  954.56 -187.78  942.17
 -148.36  933.96 -133.01  929.18 -118.94  927.96  -99.42  929.16  -91.48  928.17
  -84.09  921.87  -43.77     917   -2.61  915.27   62.98  914.75   86.94  929.09
  108.87  928.08  120.48  928.82  129.18   932.1  141.05  938.44  186.27  943.04
  196.37  946.11   202.5  946.84  209.33  949.83  216.05  950.04  226.12   952.2
  235.59  952.22  247.21  954.25  293.74  954.14   302.8  955.31  308.31  954.29
#Mann= 4 ,-1,0
 -311.27     .12       0  -91.48    .045       0   86.94     .11       0
  108.87     .14       0
Bank Sta=-91.48,86.94
XS Rating Curve= 0 ,0
Exp/Cntr=0.5,0.3

Type RM Length L Ch R = 5 ,37688.44,,,
BEGIN DESCRIPTION:
Weir N.of Gravley Rd (TWE_23) - TOR
END DESCRIPTION:
IW Pilot Flow=0
#Inline Weir SE= 28
 -311.06  969.28 -309.15  968.96 -305.89  968.07  -268.9  960.34 -236.65  952.64
 -186.79  940.57 -152.47  932.94 -130.81  932.29 -106.69  932.82  -85.26  932.15
  -85.26  934.58  -84.76  934.58  -84.76  927.28   64.29  927.28   64.29  934.58
   64.79  934.58   64.79  932.15   77.57  932.38     134  934.81  164.01  939.97
  184.23  944.59  223.49  949.48  252.96  949.01  272.64  949.44  276.25  950.49
  287.62  950.53  288.63   950.6  292.86  951.19
IW Dist,WD,Coef,Skew,MaxSub,Min_El,Is_Ogee,SpillHt,DesHd
20.5,12.3,2.6,0,0.98,, 0 ,,,0,0,
Inline Weir Flap Gates= 0
IW Outlet Rating Curve= 0 ,False,,

Type RM Length L Ch R = 1 ,37658.21,72.11755,68.54593,67.13055
BEGIN DESCRIPTION:
Weir N.of Gravley Rd (TWE_23) - DS
END DESCRIPTION:
XS GIS Cut Line= 3
   1479950.34383   1123211.09088    1479628.2185   1123168.98294
   1479338.72671   1123130.03314
#Sta/Elev= 30
 -323.93  970.93 -315.26  968.88 -304.53  965.55 -287.73  963.03 -269.03  958.15
  -240.4  952.31 -228.56   948.2 -163.91  932.03 -143.51  928.19 -121.31  925.51
  -96.52  924.08     -82  914.97   -75.1  910.06  -19.64  909.85   37.72  910.01
   47.97  913.16      57  917.28   65.62  922.63  108.53  927.25  121.82  932.47
  127.39  932.94  133.52  932.01  160.02  938.99  178.43  942.48  192.55  944.43
  216.85  945.37  238.94  944.86  261.01  945.21  277.35  947.07  293.03  949.58
#Mann= 5 ,-1,0
 -323.93     .12       0 -121.31     .14       0     -82    .045       0
      57     .11       0  127.39     .14       0
Bank Sta=-82,57
XS Rating Curve= 0 ,0
Exp/Cntr=0.5,0.3

Type RM Length L Ch R = 1 ,37589.67,363.8515,356.7317,357.6269
BEGIN DESCRIPTION:
TWE_23DSX
END DESCRIPTION:
XS GIS Cut Line= 3
   1479973.50328   1123130.03314   1479632.30052   1123100.65978
    1479328.1998   1123077.39797
#Sta/Elev= 30
 -343.04  971.32 -337.76  969.48 -331.16  963.31 -326.78  961.02 -322.98  960.68
 -310.89  961.11 -299.98  956.12 -285.18  953.22 -263.85  951.47 -244.91  944.75
 -225.07  939.44 -182.52  929.47 -164.01  926.94  -154.2  923.92 -118.07  918.28
  -63.58  915.62  -58.12  914.94  -50.17  911.52  -35.12  906.99  -29.82  906.52
   -4.23  905.74   11.41  906.88   29.64  905.52   40.45   906.7   52.76  912.02
   57.88  914.64  140.29  927.29  174.27  934.57     248   946.1  304.41  953.16
#Mann= 8 ,-1,0
 -343.04     .12       0 -322.98      .1       0 -263.85     .12       0
 -225.07      .1       0  -154.2     .14       0  -50.17    .045       0
52.76001     .11       0  140.29     .14       0
Bank Sta=-50.17,52.76
XS Rating Curve= 0 ,0
Exp/Cntr=0.3,0.1

Type RM Length L Ch R = 1 ,37232.94,395.0482,421.5169,394.4343
BEGIN DESCRIPTION:
TWE_22X
END DESCRIPTION:
XS GIS Cut Line= 3
   1479936.39403   1122744.77198    1479626.4977    1122749.1122
   1479309.65682   1122751.71621
#Sta/Elev= 30
 -311.63  929.15 -295.43  928.06 -219.22  920.63 -212.03  919.55 -200.11  919.11
 -183.63  916.69 -154.52  915.46 -145.61  913.98    -137  914.03 -129.93  912.88
  -19.21  913.59  -12.75   907.4   -7.41  905.96     .79   904.9    9.96  905.85
   12.87  907.94   19.58  913.93    40.3  913.37   87.63   914.7   98.72   914.2
   135.3  914.33  150.02  913.65  173.71   913.8  198.33  912.39  217.61  913.47
   225.9  914.05  250.86  918.32  261.22  920.68  283.65  926.42  315.15  935.74
#Mann= 6 ,-1,0
 -311.63      .1       0 -219.22     .14       0  -12.75    .045       0
   12.87     .14       055.92999     .11       0  217.61     .14       0
Bank Sta=-12.75,12.87
XS Rating Curve= 0 ,0
Exp/Cntr=0.3,0.1

Type RM Length L Ch R = 1 ,36811.42,230.7124,273.8848,256.8954
XS GIS Cut Line= 3
   1479918.38189   1122349.48031   1479561.39304   1122355.99081
   1479277.10466   1122359.24606
#Sta/Elev= 30
 -358.87  931.41 -323.82  929.68 -294.05  924.37 -249.12  921.89 -234.63  919.57
 -211.79   919.9 -176.88   913.8 -150.77  911.31  -136.7  912.84 -119.13  911.38
  -84.77  911.33  -32.19  913.37  -17.61  911.65  -10.93  907.95   -7.23  906.07
    3.52  904.29    6.77  904.48   12.26  906.63   13.19  913.21   44.19  911.95
   79.36  912.32   105.9  910.49  114.64  911.67  180.43   913.3  192.06   913.8
  201.97  915.86  215.55  916.97   248.5  923.42  266.22  932.53  282.48  938.13
#Mann= 5 ,-1,0
 -358.87     .14       0-10.9299    .045       012.26001     .14       0
23.39999     .11       0  180.43     .14       0
#XS Ineff= 1 ,-1
 -270.07 -217.01  920.19
Permanent Ineff=
       F
Bank Sta=-10.93,12.26
XS Rating Curve= 0 ,0
Exp/Cntr=0.3,0.1

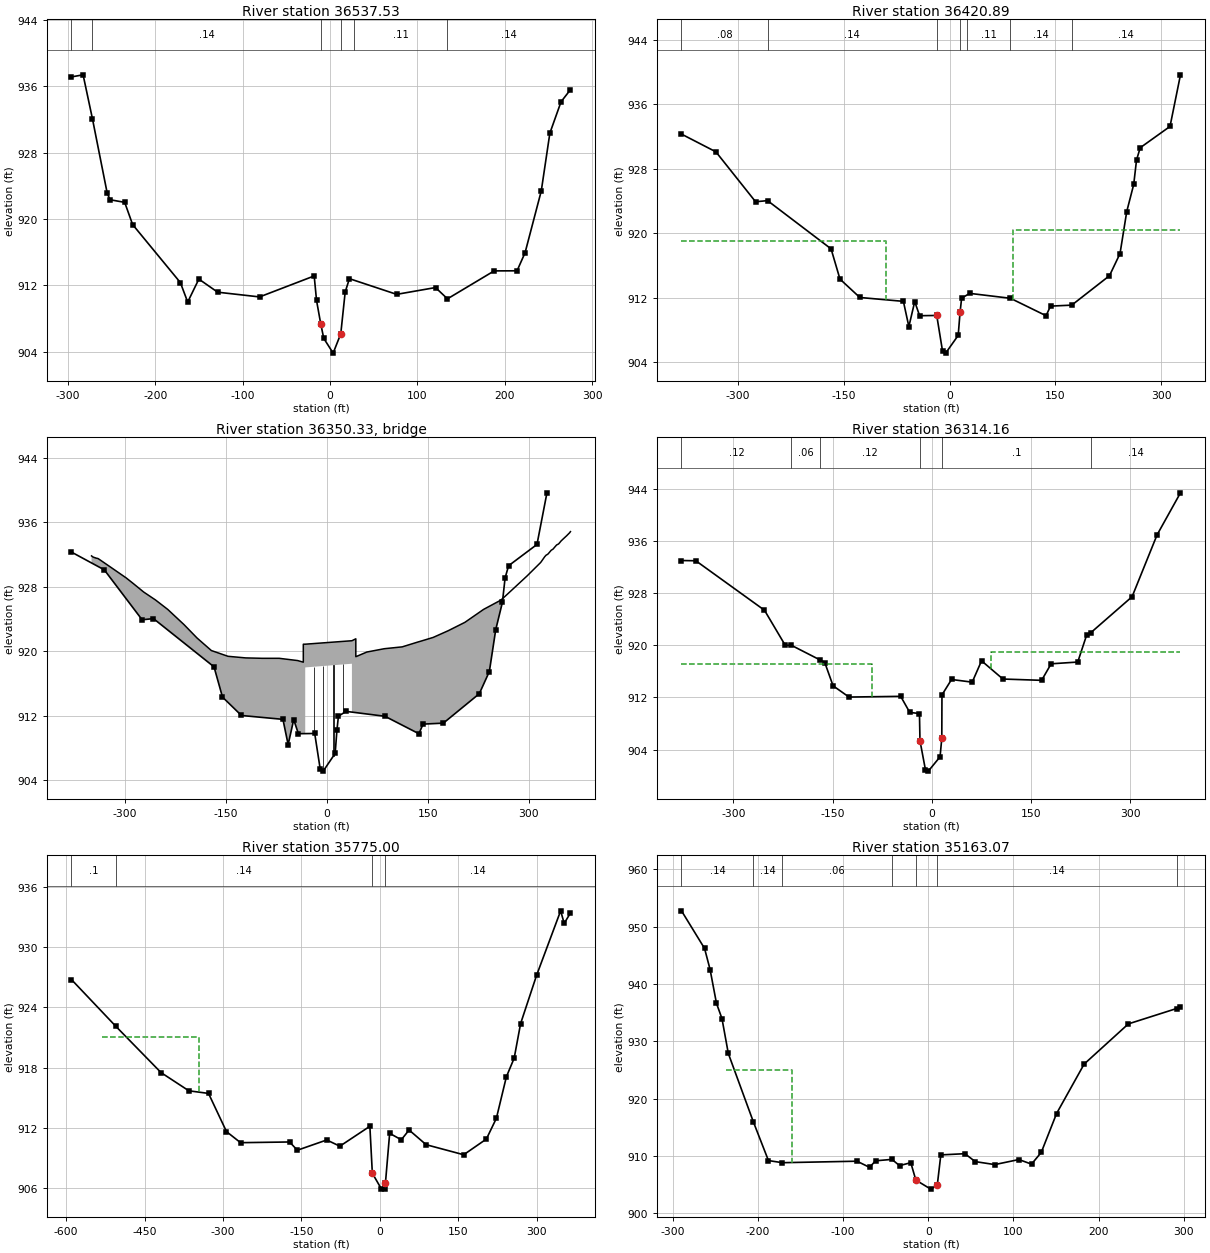
Type RM Length L Ch R = 1 ,36537.53,214.562,116.6427,97.99628
BEGIN DESCRIPTION:
TWE_21USX
END DESCRIPTION:
XS GIS Cut Line= 4
   1479866.29823    1122137.8914   1479571.85728   1122109.14698
   1479478.92782   1122099.91371   1479331.35794   1122206.25098
#Sta/Elev= 30
 -295.97  937.13 -282.68  937.38 -272.03   932.1 -255.04  923.08 -251.77  922.31
 -235.09     922 -226.01  919.32 -171.35  912.32 -162.97  909.97 -150.18  912.74
 -128.64  911.16  -80.69  910.59  -18.18  913.12  -15.48  910.16  -10.75  907.38
   -7.23  905.59    3.52  903.81   12.26  906.15   17.29  911.18   22.15  912.79
   76.22   910.9  120.69  911.72  134.37  910.36  187.82  913.73     214  913.74
  223.19  915.92  241.75  923.38  251.56  930.34  264.37  934.13  275.15  935.59
#Mann= 6 ,-1,0
 -295.97     .08       0 -272.03     .14       0  -10.75    .045       0
12.26001     .14       026.88998     .11       0  134.37     .14       0
Bank Sta=-10.75,12.26
XS Rating Curve= 0 ,0
Exp/Cntr=0.5,0.3

Type RM Length L Ch R = 1 ,36420.89,77.48199,106.7328,110.8034
BEGIN DESCRIPTION:
Gravley Rd (TWE_21) - US
END DESCRIPTION:
XS GIS Cut Line= 5
   1479945.50066   1121926.00558    1479760.8773   1121890.45833
    1479585.5502   1121992.59678   1479453.26837   1122080.78445
   1479308.38845   1122189.66962
#Sta/Elev= 30
-379.338  932.29-330.627  930.09-274.468   923.9-257.535  924.04-167.636  918.06
-155.041  914.31-126.913  912.03 -65.277  911.55 -57.531  908.42 -49.243  911.52
 -42.317  909.77 -18.063   909.8  -9.823  905.35  -5.457  905.13  12.306  907.33
  14.933   910.2  17.145  911.94  28.553  912.54  86.276  911.93  136.65  909.77
 142.957  910.96 173.007  911.08 226.413  914.73 241.346  917.48 250.861  922.69
 260.713  926.05 264.712  929.08 269.918   930.6 312.091  933.24 326.889  939.64
#Mann= 7 ,-1,0
-379.338     .08       0-257.535     .14       0-18.0629     .04       0
14.93301     .14       024.90201     .11       0  86.276     .14       0
 173.007     .14       0
#XS Ineff= 2 , 0
             -90     919      90           920.4
Permanent Ineff=
       F       F
Bank Sta=-18.063,14.933
XS Rating Curve= 0 ,0
Skew Angle= 15
Exp/Cntr=0.5,0.3

Type RM Length L Ch R = 3 ,36350.33,,,
BEGIN DESCRIPTION:
Gravley Rd (TWE_21) - TOR
Skew = 15 degrees
END DESCRIPTION:
Bridge Culvert--1,0,-1,-1, 0
Deck Dist Width WeirC Skew NumUp NumDn MinLoCord MaxHiCord MaxSubmerge Is_Ogee
56.81,27.5,2.6,15, 68, 68, 918.79, , 0.95, 0, 0,0,,
-349.559-347.579-344.101-343.715-342.817-341.397-339.958 -339.31-323.228-298.268
-287.373 -272.13-254.647-250.146-236.323-212.349-192.741-171.539-167.665-146.888
 -141.73-120.538 -95.801 -70.783  -43.36     -35     -35 -32.175  37.198      43
      43  59.433  85.301 111.931 134.766 140.127  157.89 180.174 204.989 232.836
 258.105 262.162 297.582 317.258 318.157 323.508 325.643 327.797 328.241 328.859
 333.225 335.775 336.026 337.755 341.175 341.358 344.159 344.266 344.884 348.081
 348.622 352.041 352.302 356.195 360.232 360.368 360.735 361.816
  931.82  931.69  931.58  931.58  931.54  931.52  931.49  931.46  930.54   929.1
  928.38  927.34  926.36  926.07  925.18  923.31  921.63  920.08  919.97  919.37
  919.33  919.17  919.12  919.12  918.84  918.64  920.87  920.87   921.3  921.54
  919.32   919.9  920.31  920.54  921.13  921.26  921.71  922.54  923.58  925.19
  926.32  926.61  929.35  930.98  931.07  931.71  931.91  932.01  932.04  932.09
  932.52  932.65  932.67  932.84  933.17  933.18   933.3  933.31  933.37  933.69
  933.73     934  934.02  934.32  934.66  934.67  934.71  934.83
                                                                                
                                                                                
                                                          917.99  918.45
                                                                                
                                                                                
                                                                                
                                                                
-349.559-347.579-344.101-343.715-342.817-341.397-339.958 -339.31-323.228-298.268
-287.373 -272.13-254.647-250.146-236.323-212.349-192.741-171.539-167.665-146.888
 -141.73-120.538 -95.801 -70.783  -43.36     -35     -35 -32.175  37.198      43
      43  59.433  85.301 111.931 134.766 140.127  157.89 180.174 204.989 232.836
 258.105 262.162 297.582 317.258 318.157 323.508 325.643 327.797 328.241 328.859
 333.225 335.775 336.026 337.755 341.175 341.358 344.159 344.266 344.884 348.081
 348.622 352.041 352.302 356.195 360.232 360.368 360.735 361.816
  931.82  931.69  931.58  931.58  931.54  931.52  931.49  931.46  930.54   929.1
  928.38  927.34  926.36  926.07  925.18  923.31  921.63  920.08  919.97  919.37
  919.33  919.17  919.12  919.12  918.84  918.64  920.87  920.87   921.3  921.54
  919.32   919.9  920.31  920.54  921.13  921.26  921.71  922.54  923.58  925.19
  926.32  926.61  929.35  930.98  931.07  931.71  931.91  932.01  932.04  932.09
  932.52  932.65  932.67  932.84  933.17  933.18   933.3  933.31  933.37  933.69
  933.73     934  934.02  934.32  934.66  934.67  934.71  934.83
                                                                                
                                                                                
                                                          917.93  918.43
                                                                                
                                                                                
                                                                                
                                                                
Pier Skew, UpSta & Num, DnSta & Num=  ,-19.319, 2 ,-19.319, 2 , 0 , 0 , 0 ,,
       1       1
     900     920
       1       1
     900     920
Pier Skew, UpSta & Num, DnSta & Num=  ,-5.796, 2 ,-5.796, 2 , 0 , 0 , 0 ,,
       1       1
     900     920
       1       1
     900     920
Pier Skew, UpSta & Num, DnSta & Num=  ,9.659, 2 ,9.659, 2 , 0 , 0 , 0 ,,
       1       1
     900     920
       1       1
     900     920
Pier Skew, UpSta & Num, DnSta & Num=  ,24.148, 2 ,24.148, 2 , 0 , 0 , 0 ,,
       1       1
     900     920
       1       1
     900     920
Abutment Skew #Up #Dn= , 2 , 2
  -32.17  -19.31
  917.99   909.7
  -32.17  -19.31
  917.93     909
Abutment Skew #Up #Dn= , 2 , 2
   24.38    37.2
  912.17  918.45
   24.38    37.2
  912.17  918.43
BR Coef=-1 ,-1 , 0 ,, 0 ,,,0.8,0,1.2,0,
WSPro=,,,, 1 ,,,, 0 ,,,, 0 ,,,,-1 ,-1 ,-1 , 0 , 0 , 0 , 0 , 0
BC Design=,, 0 ,, 0 ,,,,,,
BC Use User HTab Curves=0
BC User HTab FreeFlow(D)= 0

Type RM Length L Ch R = 1 ,36314.16,482.54,539.155,447.0775
BEGIN DESCRIPTION:
Gravley Rd (TWE_21) - DS
END DESCRIPTION:
XS GIS Cut Line= 6
   1479960.79856   1121870.21358   1479718.73163   1121830.61909
   1479588.65486   1121904.39829   1479543.20013   1121929.10531
   1479368.80741   1122048.68471    1479274.0351   1122127.02953
#Sta/Elev= 30
-378.604  933.04-356.919     933 -253.15   925.4 -221.68     920-212.591  920.02
-169.269  917.77-162.005  917.37-149.438  913.79-125.368  912.06 -47.214  912.17
 -33.489   909.7 -18.836  909.53 -18.063  905.35  -9.823   900.9  -5.457  900.68
  12.306  902.88  14.933  905.75  15.175  912.39  29.673  914.76  60.892  914.35
  75.033  917.63 107.324  914.83 165.849  914.63 180.213  917.17 220.453  917.44
 233.822  921.56 240.342  921.96 302.625  927.48 340.383  936.98 375.755  943.44
#Mann= 6 ,-1,0
-378.604     .12       0-212.591     .06       0-169.269     .12       0
-18.0629     .04       014.93301      .1       0 240.342     .14       0
#XS Ineff= 2 , 0
             -90   917.2      90             919
Permanent Ineff=
       F       F
Bank Sta=-18.063,14.933
XS Rating Curve= 0 ,0
Skew Angle= 15
Exp/Cntr=0.5,0.3

Type RM Length L Ch R = 1 ,35775.00,702.2434,611.939,557.5637
XS GIS Cut Line= 4
   1479964.17192   1121281.66142   1479733.26837   1121271.24475
   1479429.44882   1121469.16175   1479144.72572   1121689.64829
#Sta/Elev= 30
 -589.61  926.75 -505.34922.1296 -418.39   917.5 -365.26  915.69 -327.67  915.43
 -293.29  911.63  -266.4  910.53 -172.75   910.6 -157.79  909.78 -101.66   910.8
   -76.6  910.18  -19.22  912.16  -14.51  907.49    2.99  905.91    9.86  905.97
   10.62  906.56    18.6  911.46   40.86  910.82   55.76  911.79   88.32  910.33
  160.14  909.33  203.49  910.89  222.65  912.96  241.72  917.08  256.64  918.94
   268.9  922.37  299.51  927.18  345.48  933.59  352.24  932.34  364.24  933.38
#Mann= 4 ,-1,0
 -589.61      .1       0 -505.34     .14       0  -14.51     .04       0
   10.62     .14       0
#XS Ineff= 1 ,-1
 -531.03 -346.45  921.04
Permanent Ineff=
       F
Bank Sta=-14.51,10.62
XS Rating Curve= 0 ,0
Exp/Cntr=0.3,0.1

Type RM Length L Ch R = 1 ,35163.07,561.3027,561.0966,515.2526
XS GIS Cut Line= 3
   1479116.94816   1120778.18799   1479005.83661   1121036.86942
   1478882.57251   1121314.64764
#Sta/Elev= 30
 -289.45  952.79 -262.38  946.23  -255.9  942.55  -248.4  936.65 -241.98  934.01
 -234.51  927.91 -205.06915.9555 -187.43  909.23 -171.03908.8605  -83.58  909.12
  -68.78  908.05  -61.79  909.19  -42.58909.4362  -33.61  908.35  -20.41  908.86
  -14.51  905.83    2.99  904.25   10.62   904.9   14.81  910.22    43.1  910.43
   55.17  909.05   78.14  908.53   106.4  909.41  121.24  908.61  132.67  910.66
  150.63  917.44  182.97  926.06  234.86  933.07  291.35935.7462  295.99  935.94
#Mann= 7 ,-1,0
 -289.45     .14       0 -205.06     .14       0 -171.03     .06       0
  -42.58     .14       0  -14.51     .04       0   10.62     .14       0
  291.35      .1       0
#XS Ineff= 1 ,-1
 -236.71 -160.04  925.05
Permanent Ineff=
       F
Bank Sta=-14.51,10.62
XS Rating Curve= 0 ,0
Exp/Cntr=0.3,0.1

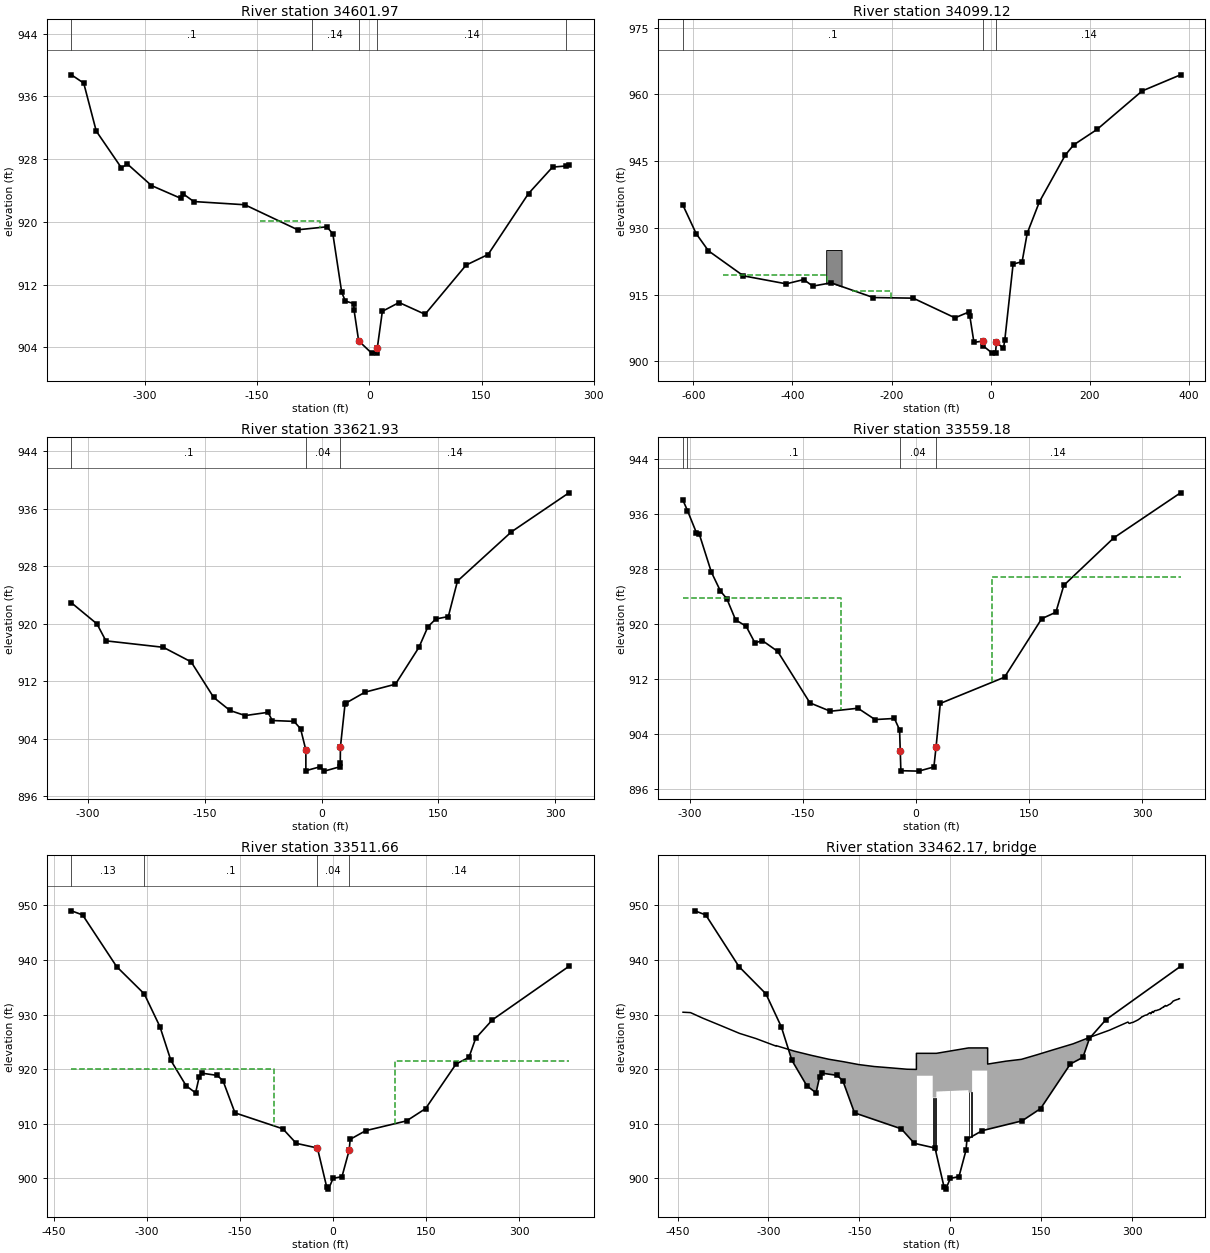
Type RM Length L Ch R = 1 ,34601.97,289.236,502.8473,547.3459
BEGIN DESCRIPTION:
TWE_20X
END DESCRIPTION:
XS GIS Cut Line= 5
   1478823.84186   1120835.94324   1478521.75853   1120820.31824
   1478495.97178   1120910.65584   1478445.07185   1121062.91109
   1478523.19685   1121137.56365
#Sta/Elev= 30
 -398.24  938.75 -381.77  937.69 -365.05  931.58 -331.51  926.91 -323.28  927.37
 -291.28  924.64 -251.56  922.99 -248.45  923.55 -234.73   922.6 -166.45  922.19
  -95.76     919  -56.71  919.38  -48.76  918.47  -36.92  911.02  -32.08  909.92
   -20.8  909.59  -20.53  908.82   -14.3  904.85    2.99  903.28    9.86  903.34
   10.62  903.93   17.39  908.61   39.74  909.73   74.49  908.23  129.34   914.5
  158.73  915.85  212.74  923.62  244.89  926.99   262.5  927.13  266.78  927.22
#Mann= 5 ,-1,0
 -398.24      .1       0-76.7399     .14       0-14.2999     .04       0
   10.62     .14       0   262.5      .1       0
#XS Ineff= 1 ,-1
 -146.55  -66.33  920.15
Permanent Ineff=
       F
Bank Sta=-14.3,10.62
XS Rating Curve= 0 ,0
Exp/Cntr=0.3,0.1

Type RM Length L Ch R = 1 ,34099.12,423.6966,477.193,491.4279
XS GIS Cut Line= 5
   1478848.58169   1120628.91207   1478540.55774   1120720.89633
   1478388.55709   1120695.70276   1478264.29429   1120615.93602
    1477939.4895   1120416.51181
#Sta/Elev= 30
 -620.98  935.04 -594.28  928.66 -569.64  924.82 -499.08   919.2 -412.66   917.4
 -377.43  918.36 -358.97  916.89 -321.91  917.63 -236.84  914.32 -156.29  914.18
  -72.03  909.76  -44.53  911.04  -42.06   910.2  -33.72  904.25  -15.35  904.52
  -14.51   903.4    2.99  901.82    9.86  901.88   11.71   904.3    25.8  902.88
   28.61   904.8   45.34  921.84   63.55  922.38   73.83  928.77   98.55  935.87
  150.67  946.35  167.57  948.64   214.8  952.12  305.81  960.77  383.36   964.4
#Mann= 3 ,-1,0
 -620.98      .1       0-15.3499     .04       011.71002     .14       0
#XS Ineff= 2 ,-1
 -539.55 -330.22  919.41 -280.39  -201.9915.8724
Permanent Ineff=
       F       F
#Block Obstruct= 1 ,-1
    -332    -301     925
Bank Sta=-15.35,11.71
XS Rating Curve= 0 ,0
Exp/Cntr=0.3,0.1

Type RM Length L Ch R = 1 ,33621.93,97.44409,62.74402,45.65453
BEGIN DESCRIPTION:
TWE_19USX
END DESCRIPTION:
XS GIS Cut Line= 4
   1478787.08629   1120621.93766   1478643.54954   1120333.91404
   1478607.60761   1120262.62959   1478375.24672   1120214.30676
#Sta/Elev= 30
 -321.33  922.92 -288.51  919.98 -277.03  917.62  -203.3  916.72 -167.56  914.69
 -138.64  909.74 -117.69  907.92  -98.17  907.21   -68.9  907.66  -63.32  906.52
  -35.39   906.4  -27.01  905.37  -20.22   902.4  -20.22  899.53   -1.49  900.09
     3.5  899.47   23.59  900.08   23.96  900.62   24.15  902.82    30.1  908.84
   30.76  908.92   55.75  910.47   94.84  911.58  124.99  916.71  136.55  919.59
  146.76  920.67  162.73     921   174.5  925.95  243.86  932.81  317.64  938.24
#Mann= 3 ,-1,0
 -321.33      .1       0  -20.22     .04       024.14999     .14       0
Bank Sta=-20.22,24.15
XS Rating Curve= 0 ,0
Exp/Cntr=0.3,0.1

Type RM Length L Ch R = 1 ,33559.18,63.0086,47.51963,28.5916
BEGIN DESCRIPTION:
Pipeline Crossing
END DESCRIPTION:
XS GIS Cut Line= 4
   1478935.83169   1120495.33924   1478696.24836    1120300.0269
   1478646.76936   1120264.43668   1478362.91503   1120205.40879
#Sta/Elev= 30
 -309.19  938.03 -303.33  936.55  -291.4  933.31  -287.5  933.08 -271.67   927.6
 -259.58  924.83 -251.08   923.7 -239.51  920.64 -225.43  919.69 -213.76  917.27
 -203.96  917.61 -183.64  916.04 -140.84  908.54 -113.78  907.32  -77.12  907.76
  -54.47  906.11   -28.8  906.27  -21.92  904.62  -21.03  901.56  -20.22  898.66
     3.5   898.6   23.59  899.21   26.52  902.16    32.1  908.46  117.29  912.28
  166.65   920.8  185.42  921.74  195.94  925.66  262.34  932.58  350.79  939.13
#Mann= 4 ,-1,0
 -309.19     .14       0 -303.33      .1       0  -21.03     .04       0
26.51999     .14       0
#XS Ineff= 2 ,-1
 -309.19  -99.88  923.88  100.11  350.79  926.93
Permanent Ineff=
       F       F
#XS Lid=2
     -26  905.73  904.73      34  908.46  907.46
Bank Sta=-21.03,26.52
XS Rating Curve= 0 ,0
Exp/Cntr=0.5,0.3

Type RM Length L Ch R = 1 ,33511.66,107.9683,102.7682,116.1268
BEGIN DESCRIPTION:
Red Hill Rd (TWE_19) - US
END DESCRIPTION:
XS GIS Cut Line= 4
   1479149.44029   1120369.55676   1478796.78642   1120292.44554
   1478725.84416   1120274.96719   1478365.99311   1120200.94094
#Sta/Elev= 30
 -421.52  949.02 -403.54  948.27  -348.7  938.79 -304.21  933.79 -278.88  927.76
  -261.3  921.58 -236.68  916.92 -221.52  915.63 -215.57   918.6 -211.48  919.24
  -186.6  918.83 -177.27  917.83 -158.06  911.96  -80.87  909.03  -59.35  906.37
  -25.22  905.51  -10.31  898.37    -7.4  897.97    -.01  899.94   14.34  900.27
   25.92   905.1   27.52  907.11   52.71   908.7  118.42  910.49  148.99  912.74
  198.08  920.92  218.85  922.14  229.67  925.63  256.56  929.02  379.92  938.84
#Mann= 4 ,-1,0
 -421.52     .13       0 -304.21      .1       0  -25.22     .04       0
25.92001     .14       0
#XS Ineff= 2 , 0
             -95     920     100           921.4
Permanent Ineff=
       F       F
Bank Sta=-25.22,25.92
XS Rating Curve= 0 ,0
Exp/Cntr=0.5,0.3

Type RM Length L Ch R = 3 ,33462.17,,,
BEGIN DESCRIPTION:
Red Hill Rd (TWE_19) - TOR
END DESCRIPTION:
Bridge Culvert--1,0,-1,-1, 0
Deck Dist Width WeirC Skew NumUp NumDn MinLoCord MaxHiCord MaxSubmerge Is_Ogee
31.7,35.6,2.6,0, 101, 101, 919.93, , 0.95, 0, 0,0,,
    -441 -428.71  -408.2 -378.44 -347.84  -320.7 -287.82 -287.65 -276.58  -257.4
 -228.83  -200.7 -176.08 -151.09 -125.57 -100.99     -71  -69.91  -55.92  -55.92
   -55.1     -29     -29     -23     -23      30      30      36      36   60.85
   61.65   61.65   91.71  117.39  142.83  172.23  202.77  228.76  262.52  293.15
  295.02  296.54  297.54  299.14  301.55  304.41  305.72  309.58  309.73  310.08
  312.92  313.45  314.58  316.19  317.35  318.94  319.33  320.89  322.36  322.88
  325.14  326.61  329.44  330.72  331.27  333.02  334.06  335.24   336.7  338.47
  339.91  342.86  343.87  346.44  347.11  347.25  347.33   347.4  347.64  351.31
  351.86  352.79  355.02  356.22  357.58  360.56  360.99  362.61  364.01  365.35
  366.88  367.84  368.95  369.95  370.08  370.32  373.52  374.53  375.93  376.84
  378.12
  930.42  930.35  929.32  927.96  926.54  925.59  924.22   924.3  923.93  923.28
   922.5   921.8  921.34  920.82  920.46  920.24  919.96  919.96  919.93  922.88
  922.88  922.88  922.88  922.88  922.88  923.87  923.87  923.87  923.87  923.87
  923.87  920.91  921.44  921.78  922.61  923.61  924.63  925.76  927.12  928.62
  928.37  928.39  928.44  928.51  928.56  928.73  928.79  929.01  929.02  929.04
  929.27  929.29  929.42  929.59  929.61  929.72  929.74  929.83  929.88  929.88
  929.96  930.12  930.32  930.15  930.18  930.51  930.54  930.38  930.66  930.73
  930.72  930.85  930.86  931.01  931.06  931.07  931.08  931.07   931.1  931.36
  931.31  931.48  931.65  931.54  931.59  931.81  931.83   931.9  932.03  932.16
  932.35  932.48  932.51  932.57  932.57  932.59  932.72  932.76  932.78  932.89
   932.9
                                                                                
                                                                                
  918.77  918.77  914.77  914.77  915.87  916.12  915.71  915.71  919.71  919.71
                                                                                
                                                                                
                                                                                
                                                                                
                                                                                
                                                                                
                                                                                
        
    -441 -428.71  -408.2 -378.44 -347.84  -320.7 -287.82 -287.65 -276.58  -257.4
 -228.83  -200.7 -176.08 -151.09 -125.57 -100.99     -71  -69.91  -55.92  -55.92
   -55.1     -29     -29     -23     -23      30      30      36      36   60.85
   61.65   61.65   91.71  117.39  142.83  172.23  202.77  228.76  262.52  293.15
  295.02  296.54  297.54  299.14  301.55  304.41  305.72  309.58  309.73  310.08
  312.92  313.45  314.58  316.19  317.35  318.94  319.33  320.89  322.36  322.88
  325.14  326.61  329.44  330.72  331.27  333.02  334.06  335.24   336.7  338.47
  339.91  342.86  343.87  346.44  347.11  347.25  347.33   347.4  347.64  351.31
  351.86  352.79  355.02  356.22  357.58  360.56  360.99  362.61  364.01  365.35
  366.88  367.84  368.95  369.95  370.08  370.32  373.52  374.53  375.93  376.84
  378.12
  930.42  930.35  929.32  927.96  926.54  925.59  924.22   924.3  923.93  923.28
   922.5   921.8  921.34  920.82  920.46  920.24  919.96  919.96  919.93  922.88
  922.88  922.88  922.88  922.88  922.88  923.87  923.87  923.87  923.87  923.87
  923.87  920.91  921.44  921.78  922.61  923.61  924.63  925.76  927.12  928.62
  928.37  928.39  928.44  928.51  928.56  928.73  928.79  929.01  929.02  929.04
  929.27  929.29  929.42  929.59  929.61  929.72  929.74  929.83  929.88  929.88
  929.96  930.12  930.32  930.15  930.18  930.51  930.54  930.38  930.66  930.73
  930.72  930.85  930.86  931.01  931.06  931.07  931.08  931.07   931.1  931.36
  931.31  931.48  931.65  931.54  931.59  931.81  931.83   931.9  932.03  932.16
  932.35  932.48  932.51  932.57  932.57  932.59  932.72  932.76  932.78  932.89
   932.9
                                                                                
                                                                                
  918.04  918.04  914.04  914.04  915.87  916.12     915     915     919     919
                                                                                
                                                                                
                                                                                
                                                                                
                                                                                
                                                                                
                                                                                
        
Pier Skew, UpSta & Num, DnSta & Num=  ,-28, 2 ,-28, 2 , 0 , 0 , 0 ,,
       1       1
     900     920
       1       1
     900     920
Pier Skew, UpSta & Num, DnSta & Num=  ,-24, 2 ,-24, 2 , 0 , 0 , 0 ,,
       1       1
     900     920
       1       1
     900     920
Pier Skew, UpSta & Num, DnSta & Num=  ,31, 2 ,31, 2 , 0 , 0 , 0 ,,
       1       1
     900     920
       1       1
     900     920
Pier Skew, UpSta & Num, DnSta & Num=  ,35, 2 ,35, 2 , 0 , 0 , 0 ,,
       1       1
     900     920
       1       1
     900     920
Abutment Skew #Up #Dn= , 2 , 2
   -55.1     -28
  918.77  905.71
   -55.1     -28
  918.04  905.71
Abutment Skew #Up #Dn= , 2 , 2
      35   60.85
  907.19  919.71
      35   60.85
   901.3     919
BR Coef=-1 ,-1 , 0 ,, 0 ,,,0.8,0,1.2,0,
WSPro=,,,, 1 ,,,, 0 ,,,, 0 ,,,,-1 ,-1 ,-1 , 0 , 0 , 0 , 0 , 0
BC Design=,, 0 ,, 0 ,,,,,,
BC Use User HTab Curves=0
BC User HTab FreeFlow(D)= 0