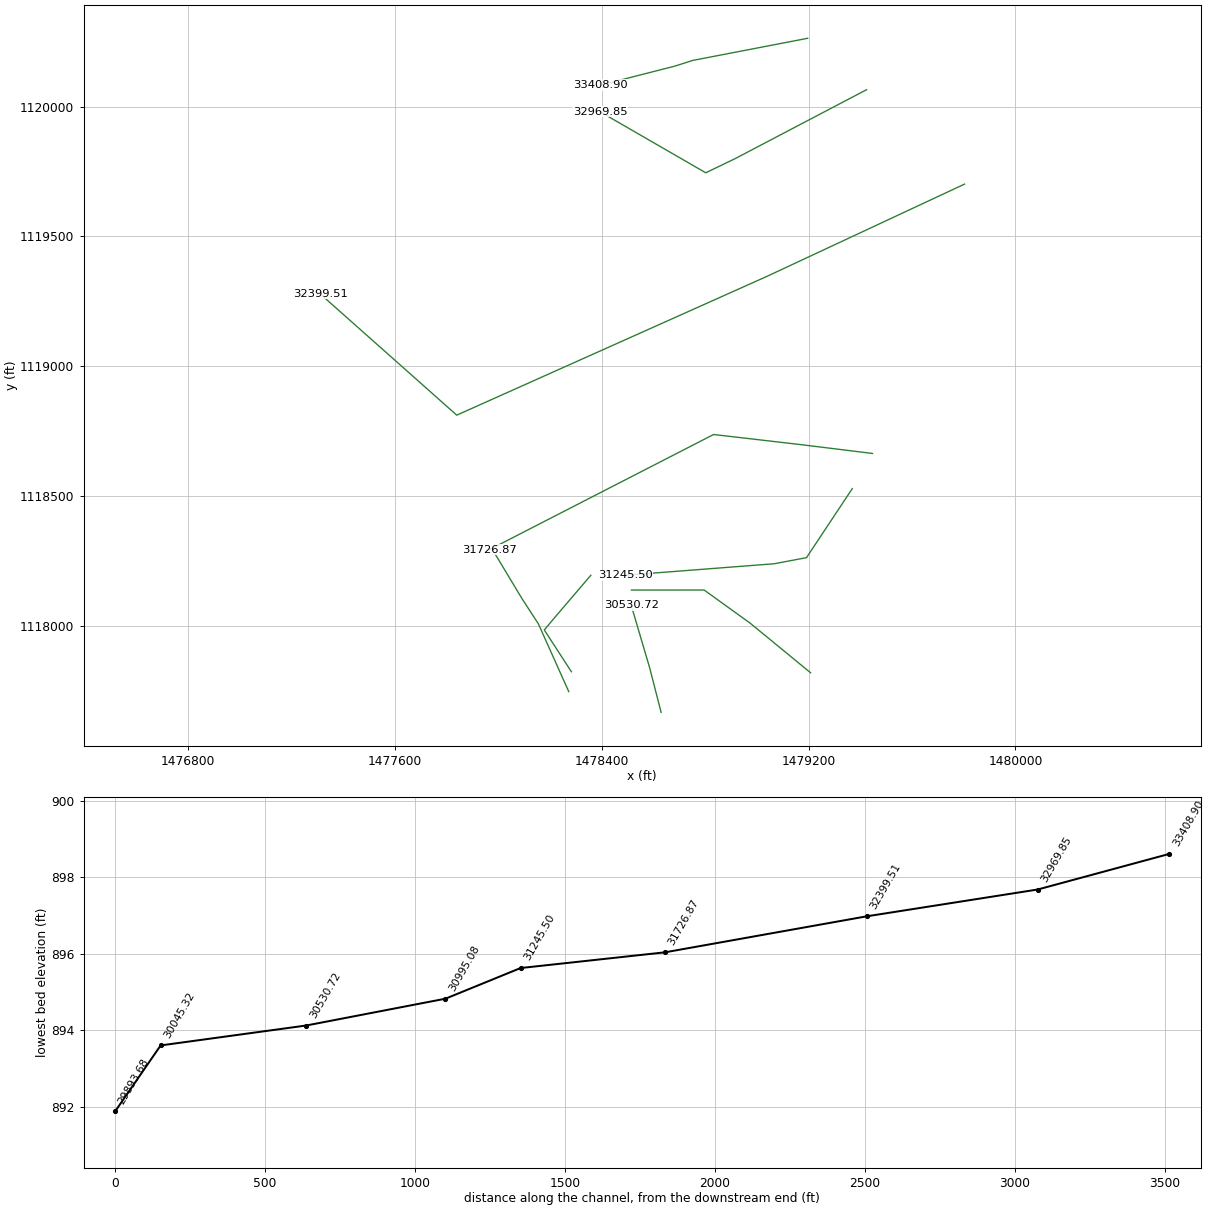
HEC-RAS study 12mile_Combined.prj: 12mile Creek Combined Model

--- 12mile_Combined.g07 (geometry) --- (continued)

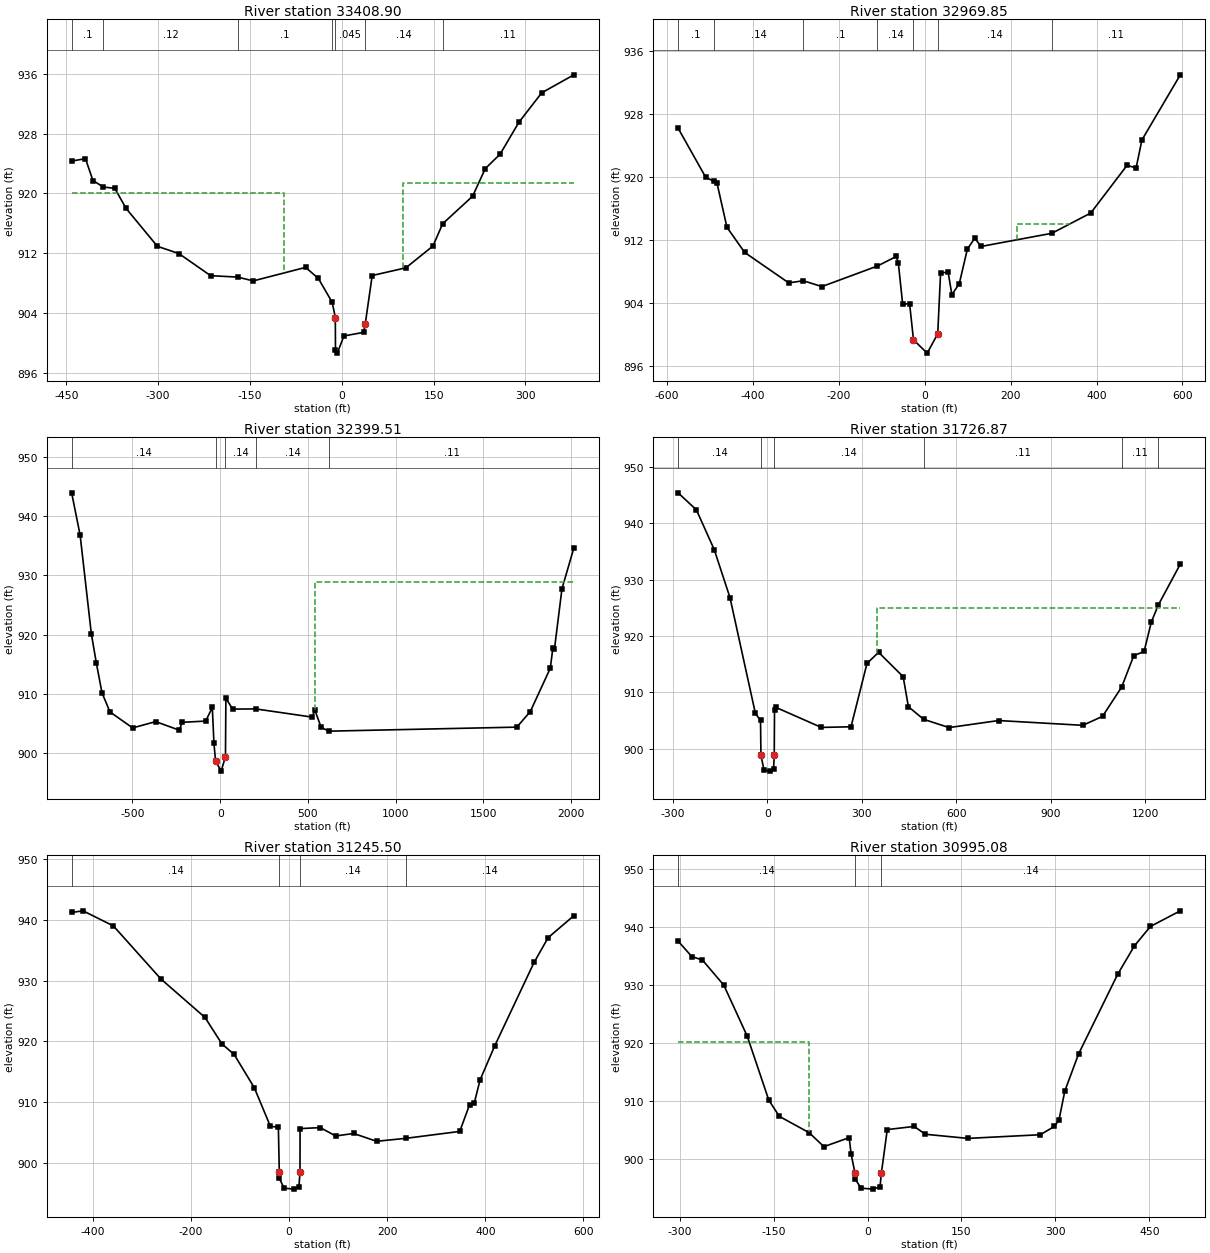
Type RM Length L Ch R = 1 ,33408.90,429.2785,439.0403,382.9909
BEGIN DESCRIPTION:
Red Hill Rd (TWE_19) - DS
END DESCRIPTION:
XS GIS Cut Line= 4
   1479196.73491   1120262.62959    1478751.5479   1120177.29364
   1478683.69029    1120155.7021    1478396.8376   1120082.70407
#Sta/Elev= 30
 -441.35  924.32  -418.8  924.65 -406.53  921.71 -389.49  920.85 -370.85  920.67
 -352.57     918 -301.24  912.91 -266.13  911.94 -214.34  908.98 -170.13  908.79
  -144.6  908.28   -59.1  910.09  -38.37  908.62   -15.7  905.42  -10.55  903.38
  -10.31  899.01    -7.4  898.61    3.59  900.91   35.77  901.39   38.33  902.52
   49.71     909  104.67  910.03  148.98  912.95  164.79  915.93  213.77  919.62
   234.4  923.31   258.7  925.25  289.41  929.52  326.65  933.46  379.15  935.87
#Mann= 7 ,-1,0
 -441.35      .1       0 -389.49     .12       0 -170.13      .1       0
   -15.7     .14       0-10.5499    .045       038.32999     .14       0
  164.79     .11       0
#XS Ineff= 2 , 0
             -95     92099.99997           921.4
Permanent Ineff=
       F       F
Bank Sta=-10.55,38.33
XS Rating Curve= 0 ,0
Exp/Cntr=0.5,0.3

Type RM Length L Ch R = 1 ,32969.85,484.9809,570.3428,730.3533
BEGIN DESCRIPTION:
TWE_18X
END DESCRIPTION:
XS GIS Cut Line= 4
   1479424.24049   1120064.64501   1478916.31004   1119799.55643
   1478802.59646   1119744.93504   1478394.60925   1119979.31037
#Sta/Elev= 30
 -574.55  926.21 -510.05  919.96 -491.04  919.48 -483.93  919.23 -460.83  913.64
 -419.51  910.45 -316.93  906.59  -282.9  906.86 -239.66  906.12  -110.2  908.73
   -66.5  909.94  -61.66  909.11  -51.57   903.9  -35.39  903.94  -26.34  899.36
    5.51  897.68   30.09  900.12   36.77  907.86   54.33  907.94   63.08  905.09
   80.32   906.5   99.14  910.88   116.4  912.26  130.95  911.21  295.85  912.88
  386.46  915.45  471.21  921.51   492.1  921.16  505.67  924.72  595.07  932.98
#Mann= 7 ,-1,0
 -574.55      .1       0 -491.04     .14       0  -282.9      .1       0
  -110.2     .14       0  -26.34    .045       030.09003     .14       0
  295.85     .11       0
#XS Ineff= 1 ,-1
  213.92  341.07  914.02
Permanent Ineff=
       F
Bank Sta=-26.34,30.09
XS Rating Curve= 0 ,0
Exp/Cntr=0.3,0.1

Type RM Length L Ch R = 1 ,32399.51,860.4338,672.6442,491.1495
XS GIS Cut Line= 4
   1479803.44718   1119701.43241   1479038.20407   1119345.88878
   1477839.47474   1118812.22146   1477310.60564   1119279.52165
#Sta/Elev= 30
 -846.45  943.91 -797.99  936.74 -734.41  920.17 -705.66  915.19 -673.51  910.19
 -628.11  906.96 -498.89  904.27  -367.3  905.33 -232.78  903.88 -217.24  905.21
  -82.52  905.42  -44.92  907.72  -35.56  901.66  -26.34  898.66    5.51  896.98
   30.09  899.42   32.44  909.28   70.56  907.44  202.93  907.47  523.88  906.09
  539.76  907.25  575.06  904.37  618.87  903.72 1690.45   904.4 1767.02  907.02
 1881.24  914.35 1895.79  917.75    1905  917.61 1947.41   927.7 2015.25  934.62
#Mann= 5 ,-1,0
 -846.45     .14       0  -26.34     .04       030.09003     .14       0
  202.93     .14       0620.9899     .11       0
#XS Ineff= 2 , 0
                        539.9999          928.95
Permanent Ineff=
       F       F
Bank Sta=-26.34,30.09
XS Rating Curve= 0 ,0
Exp/Cntr=0.3,0.1

Type RM Length L Ch R = 1 ,31726.87,456.2632,481.3701,514.452
XS GIS Cut Line= 4
   1479447.31332   1118664.81759   1479171.27165   1118698.67192
   1478832.72999   1118737.73425   1477964.48294   1118293.91273
#Sta/Elev= 30
 -282.94  945.44 -224.86  942.41 -168.33  935.36 -118.29  926.84  -37.69  906.29
  -21.37  905.03  -20.05  898.82  -10.23  896.21    8.91  896.04   20.01  896.46
   22.16  898.82   23.04  906.92   26.77  907.37  171.64   903.8  265.84  903.91
  316.62  915.16  353.44  917.13  431.47  912.79  447.93  907.48  496.22905.2398
  577.02  903.77  734.25  905.02 1001.59  904.17 1064.16  905.76 1124.92 910.963
 1163.22  916.52 1196.18  917.29 1219.13  922.52 1241.71925.5745 1311.07  932.79
#Mann= 6 ,-1,0
 -282.94     .14       0-20.0499     .04       0   22.16     .14       0
  496.22     .11       0 1124.92     .11       0 1241.71     .14       0
#XS Ineff= 2 , 0
                          348.07             925
Permanent Ineff=
       F       F
Bank Sta=-20.05,22.16
XS Rating Curve= 0 ,0
Exp/Cntr=0.3,0.1

Type RM Length L Ch R = 1 ,31245.50,294.3723,250.416,146.7567
XS GIS Cut Line= 4
   1479369.18832   1118529.40092   1479192.10499   1118263.77592
   1479067.10499   1118240.33858   1478491.58399   1118196.06759
#Sta/Elev= 30
  -443.3  941.22 -420.09  941.49 -358.18     939 -261.37  930.26 -171.51  923.92
 -137.08  919.57 -112.07  917.82  -71.05  912.35   -38.1  905.96  -21.93  905.86
  -20.05  898.41  -19.93  897.39  -10.23   895.8    8.91  895.63   20.01  896.05
   22.16  898.41   22.28   905.6   63.49  905.77   94.81  904.39  131.58   904.8
  178.27  903.51  238.59904.0079  347.75  905.14  367.78  909.53  377.48  909.85
  389.24  913.63  418.78  919.19  499.21  932.98  528.07  937.08  580.34  940.68
#Mann= 4 ,-1,0
  -443.3     .14       0-20.0499     .04       0   22.16     .14       0
  238.59     .14       0
Bank Sta=-20.05,22.16
XS Rating Curve= 0 ,0
Exp/Cntr=0.3,0.1

Type RM Length L Ch R = 1 ,30995.08,457.8576,464.3595,353.1964
BEGIN DESCRIPTION:
TWE_17X
END DESCRIPTION:
XS GIS Cut Line= 4
   1479208.09285   1117820.67388   1478974.16339   1118011.68602
   1478796.23425   1118139.20538    1478515.0351   1118139.11155
#Sta/Elev= 30
 -302.51   937.6  -280.7  934.94 -263.64  934.33 -229.52     930 -192.14  921.21
  -157.6  910.16 -140.75  907.37  -93.15  904.56  -69.63  902.15  -29.29  903.71
   -26.2   900.9  -20.05  897.61  -19.93  896.59  -10.23     895    8.91  894.83
   20.01  895.25   22.16  897.61   31.55   905.1   74.58  905.64   92.34  904.29
  160.27  903.58  275.99  904.21  298.57  905.65  305.91   906.8  315.14  911.75
  337.22  918.17  399.48  931.86  426.34  936.78  451.92  940.13   499.6  942.82
#Mann= 3 ,-1,0
 -302.51     .14       0-20.0499     .04       0   22.16     .14       0
#XS Ineff= 2 , 0
          -93.87  920.13
Permanent Ineff=
       F       F
Bank Sta=-20.05,22.16
XS Rating Curve= 0 ,0
Exp/Cntr=0.3,0.1

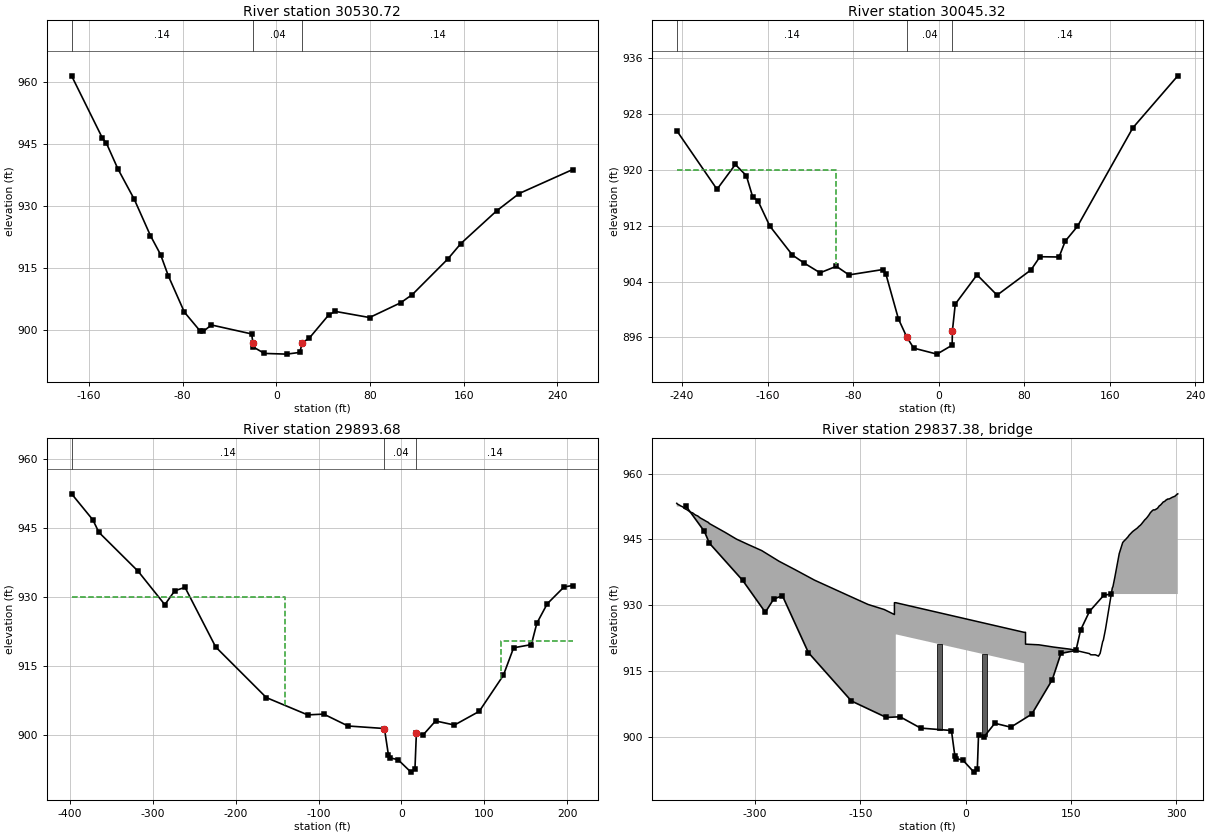
Type RM Length L Ch R = 1 ,30530.72,488.9278,485.3971,368.1059
XS GIS Cut Line= 3
   1478629.86745   1117668.50951   1478585.23228    1117840.9626
   1478514.22244   1118080.36844
#Sta/Elev= 30
 -174.87  961.43 -148.48  946.33 -145.11  945.13  -135.4  938.97 -121.29  931.54
 -107.56   922.8  -98.89  918.21  -92.25  913.05  -78.57  904.29  -64.83  899.63
  -62.43  899.63  -55.42  901.18  -21.11  899.01  -20.05  896.91  -19.93  895.89
  -10.23   894.3    8.91  894.13   20.01  894.55   22.16  896.91      28  897.96
   44.71  903.61   50.21  904.47   79.58  902.98  106.15  906.55   116.1  908.53
  146.42  917.14   157.6  920.88  187.99  928.75  207.27  932.96  252.98  938.76
#Mann= 3 ,0,0
 -174.87     .14       0  -20.05     .04       0   22.16     .14       0
Bank Sta=-20.05,22.16
XS Rating Curve= 0 ,0
Exp/Cntr=0.3,0.1

Type RM Length L Ch R = 1 ,30045.32,97.19073,151.6482,202.5759
BEGIN DESCRIPTION:
TWE_16USX
END DESCRIPTION:
XS GIS Cut Line= 4
   1478282.83957   1117824.84547   1478178.07054     1117985.479
   1478212.42881   1118026.38156        1478358.   1118196.01345
#Sta/Elev= 30
 -244.99  925.59 -207.34   917.2  -190.2  920.75 -179.89  919.15 -173.99  916.12
 -169.03  915.55 -157.98  911.95  -136.8  907.79 -125.96  906.66 -110.93  905.25
   -95.7  906.18  -83.89  904.95  -52.41  905.71  -49.39   905.1  -37.59  898.64
  -29.78  896.05  -23.32  894.47   -1.57  893.61   12.66  894.89   12.87  896.92
   15.57  900.77   35.94  904.96   54.69  902.05   86.41  905.66    94.8  907.55
  112.69  907.51  118.41  909.77  129.86  911.89  181.72     926  223.74  933.44
#Mann= 3 ,-1,0
 -244.99     .14       0  -29.78     .04       012.87001     .14       0
#XS Ineff= 2 , 0
          -96.08  920.03
Permanent Ineff=
       F       F
Bank Sta=-29.78,12.87
XS Rating Curve= 0 ,0
Exp/Cntr=0.5,0.3

Type RM Length L Ch R = 1 ,29893.68,109.4181,105.9196,106.1071
BEGIN DESCRIPTION:
Reece Mill Rd (TWE_16) - US
END DESCRIPTION:
XS GIS Cut Line= 4
   1478272.65551   1117748.29692   1478155.16437   1118008.97999
   1478091.17356   1118107.06398   1477982.04626   1118287.61352
#Sta/Elev= 30
 -398.03  952.52-372.287  946.83-365.108  944.14-317.729  935.65-285.496  928.37
-273.461  931.41-261.132  932.14-224.123  919.16-162.976  908.13-113.085  904.36
 -93.714  904.53 -64.357  901.94 -20.464  901.39  -15.58  895.57 -13.777     895
  -4.018   894.6  11.562  891.89  16.377  892.52   18.12  900.43  26.344  900.02
  41.303  903.04  64.081  902.15  93.961  905.13 123.071  912.97  135.46  918.98
  156.87  919.67 163.468  924.32 176.074  928.57 196.371  932.24 206.662  932.54
#Mann= 3 ,-1,0
 -398.03     .14       0-20.4639     .04       0   18.12     .14       0
#XS Ineff= 2 , 0
            -140     930     120           920.4
Permanent Ineff=
       F       F
Bank Sta=-20.464,18.12
XS Rating Curve= 0 ,0
Skew Angle= 10
Exp/Cntr=0.5,0.3

Type RM Length L Ch R = 3 ,29837.38,,,
BEGIN DESCRIPTION:
Reece Mill Rd (TWE_16) - TOR
Skew = 10 Degrees
END DESCRIPTION:
Bridge Culvert--1,0,-1,-1, 0
Deck Dist Width WeirC Skew NumUp NumDn MinLoCord MaxHiCord MaxSubmerge Is_Ogee
38.75,35.1,2.6,10, 140, 140, 919.17, , 0.95, 0, 0,0,,
-411.591-411.413-410.911-409.247-405.879-405.337-404.766-403.584-403.555-403.417
-399.221-397.902-397.754-397.242-394.031-393.204-392.357-390.654-389.147-386.803
-386.488-386.439 -386.36-384.804-383.376-382.421-381.711-380.215-378.521 -377.27
-374.276-373.872-372.425-371.657-369.401-366.989-365.964-365.186-342.467-326.523
-310.175-290.558-265.819-243.228-215.328-191.604-164.148-139.153-116.099-101.652
-101.652 -99.682  83.039  85.009  85.009 103.996 125.061 149.159 171.179 176.261
 177.551 180.643 183.539 184.415 185.636 185.814 188.187 188.807 191.299 194.992
 195.731 198.921  206.79 207.942 208.307 208.543 209.498 210.572 212.167 217.258
  218.45  221.03 223.413 224.162  224.94 226.998 227.313 228.436 228.456 231.046
 232.159 232.454 232.927 236.462 237.004 238.648 240.933 243.395 244.449 245.621
 247.128 248.408 250.013 251.845 252.347  253.49 254.839 256.542 258.286 260.738
 261.979 262.865 265.819 267.178 268.793 268.981 269.118 270.123 272.605 273.363
 275.579 275.992 277.115 278.996 280.454 281.212 282.246 283.004  285.19 286.353
 286.874 289.888 292.941  293.65 294.054 297.373  297.52 298.535 301.184 301.824
  953.25   953.2  953.11  952.95   952.6   952.6  952.55  952.49  952.49  952.47
  951.92  951.92  951.91  951.78  951.45  951.33  951.27  951.14  951.08  950.78
  950.75  950.74  950.73  950.56  950.46   950.4  950.36  950.17  949.95  949.83
  949.58  949.56   949.4  949.32  949.11  948.92  948.78  948.63  946.59  945.07
  943.86  942.45  940.01  938.11   935.7  933.96  931.97  930.16     929  927.86
  930.56  930.56   923.8   923.8   921.1  920.95  920.43  919.94  919.12  918.93
  918.69  918.66  918.66  918.67  918.58  918.58  918.42  918.35  919.01  921.75
  921.93  924.52  932.27  933.41  933.72   933.9  934.22  935.03  936.34  940.64
  941.76  943.05   944.3  944.42  944.58  944.93  944.94  945.16  945.16  945.61
   945.9  945.95  946.03  946.62  946.71  946.94   947.2  947.47  947.63  947.84
  948.07  948.22   948.5  948.88  948.98   949.2  949.48  949.73  950.05  950.58
  950.91  951.12  951.61  951.75  951.73  951.73  951.74  951.83  952.07  952.19
  952.68  952.72  952.83  953.15  953.44  953.57  953.61  953.66  954.01  954.07
   954.2  954.26  954.51  954.59  954.63  954.82  954.84  954.99  955.36  955.41
                                                                                
                                                                                
                                                                                
                                                                                
                                                                                
          923.34  916.73
                                                                                
                                                                                
                                                                                
                                                                                
                                                                                
                                                                                
                                                                                
                                                                                
-411.591-411.413-410.911-409.247-405.879-405.337-404.766-403.584-403.555-403.417
-399.221-397.902-397.754-397.242-394.031-393.204-392.357-390.654-389.147-386.803
-386.488-386.439 -386.36-384.804-383.376-382.421-381.711-380.215-378.521 -377.27
-374.276-373.872-372.425-371.657-369.401-366.989-365.964-365.186-342.467-326.523
-310.175-290.558-265.819-243.228-215.328-191.604-164.148-139.153-116.099-101.652
-101.652 -99.682  83.039  85.009  85.009 103.996 125.061 149.159 171.179 176.261
 177.551 180.643 183.539 184.415 185.636 185.814 188.187 188.807 191.299 194.992
 195.731 198.921  206.79 207.942 208.307 208.543 209.498 210.572 212.167 217.258
  218.45  221.03 223.413 224.162  224.94 226.998 227.313 228.436 228.456 231.046
 232.159 232.454 232.927 236.462 237.004 238.648 240.933 243.395 244.449 245.621
 247.128 248.408 250.013 251.845 252.347  253.49 254.839 256.542 258.286 260.738
 261.979 262.865 265.819 267.178 268.793 268.981 269.118 270.123 272.605 273.363
 275.579 275.992 277.115 278.996 280.454 281.212 282.246 283.004  285.19 286.353
 286.874 289.888 292.941  293.65 294.054 297.373  297.52 298.535 301.184 301.824
  953.25   953.2  953.11  952.95   952.6   952.6  952.55  952.49  952.49  952.47
  951.92  951.92  951.91  951.78  951.45  951.33  951.27  951.14  951.08  950.78
  950.75  950.74  950.73  950.56  950.46   950.4  950.36  950.17  949.95  949.83
  949.58  949.56   949.4  949.32  949.11  948.92  948.78  948.63  946.59  945.07
  943.86  942.45  940.01  938.11   935.7  933.96  931.97  930.16     929  927.86
  930.56  930.56   923.8   923.8   921.1  920.95  920.43  919.94  919.12  918.93
  918.69  918.66  918.66  918.67  918.58  918.58  918.42  918.35  919.01  921.75
  921.93  924.52  932.27  933.41  933.72   933.9  934.22  935.03  936.34  940.64
  941.76  943.05   944.3  944.42  944.58  944.93  944.94  945.16  945.16  945.61
   945.9  945.95  946.03  946.62  946.71  946.94   947.2  947.47  947.63  947.84
  948.07  948.22   948.5  948.88  948.98   949.2  949.48  949.73  950.05  950.58
  950.91  951.12  951.61  951.75  951.73  951.73  951.74  951.83  952.07  952.19
  952.68  952.72  952.83  953.15  953.44  953.57  953.61  953.66  954.01  954.07
   954.2  954.26  954.51  954.59  954.63  954.82  954.84  954.99  955.36  955.41
                                                                                
                                                                                
                                                                                
                                                                                
                                                                                
          923.41  916.69
                                                                                
                                                                                
                                                                                
                                                                                
                                                                                
                                                                                
                                                                                
                                                                                
Pier Skew, UpSta & Num, DnSta & Num=  ,-37.423, 4 ,-37.423, 4 , 3 , 3 , 0 ,,
       4       4       6       6
     900     919     919     922
       4       4       6       6
     900     919     919     922
Pier Skew, UpSta & Num, DnSta & Num=  ,26.59, 4 ,26.59, 4 , 3 , 3 , 0 ,,
       4       4       6       6
     900     917     917     919
       4       4       6       6
     900     917     917     919
Abutment Skew #Up #Dn= , 2 , 2
  -99.68     -39
  923.34  901.83
  -99.68     -39
  923.34  901.83
Abutment Skew #Up #Dn= , 2 , 2
   26.34   83.04
  900.02  916.73
   26.34   83.04
  897.68  916.69
BR Coef=-1 ,-1 , 0 ,, 0 ,,,0.8,0,1.2,0,
WSPro=,,,, 1 ,,,, 0 ,,,, 0 ,,,,-1 ,-1 ,-1 , 0 , 0 , 0 , 0 , 0
BC Design=,, 0 ,, 0 ,,,,,,
BC Use User HTab Curves=0
BC User HTab FreeFlow(D)= 0