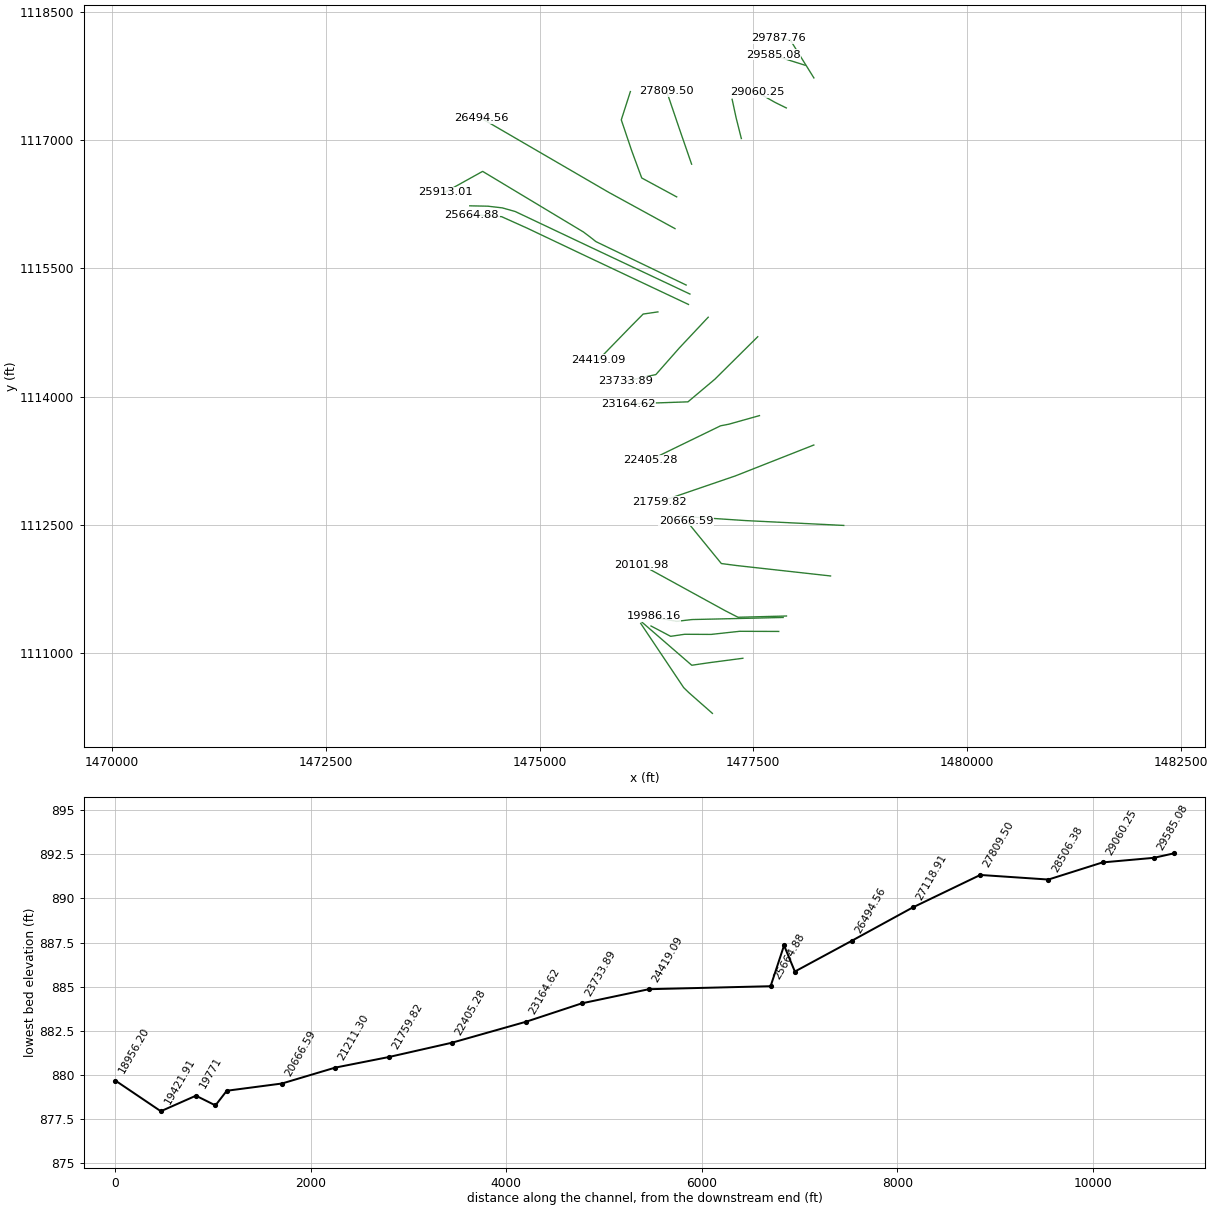
HEC-RAS study 12mile_Combined.prj: 12mile Creek Combined Model

--- 12mile_Combined.g07 (geometry) --- (continued)

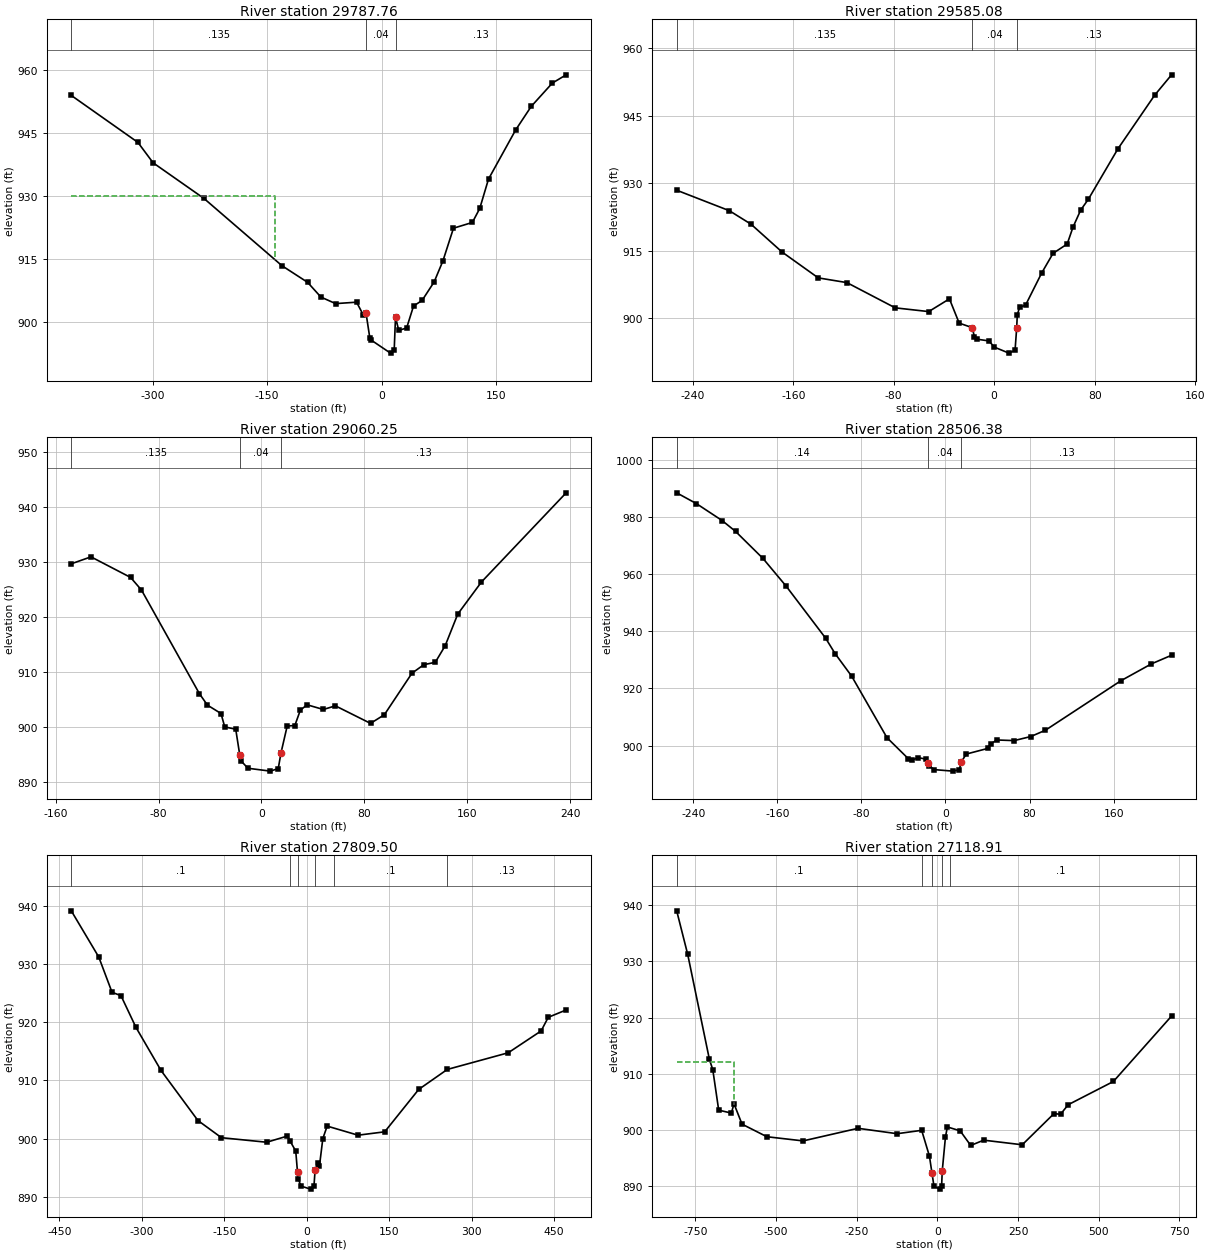
Type RM Length L Ch R = 1 ,29787.76,135.3192,202.6774,209.5373
BEGIN DESCRIPTION:
Reece Mill Rd (TWE_16) - DS
END DESCRIPTION:
XS GIS Cut Line= 4
   1478209.16765   1117726.30545   1477987.82644   1118081.65387
    1477932.0479   1118173.25098   1477800.65157   1118189.38812
#Sta/Elev= 30
-406.617  953.96-319.353  942.77-299.401   937.9 -232.72   929.4-130.625  913.38
 -97.023  909.42 -79.622  905.91 -60.369  904.35 -32.873  904.69 -24.128  901.66
 -20.464  902.05  -15.58  896.23 -13.777  895.66  11.562  892.55  16.377  893.18
   18.12  901.09  22.365  897.97  32.686  898.54  41.746  903.78  52.924   905.1
   68.74  909.52  80.301  914.56  94.049  922.32 118.788  923.69 128.468  927.02
 139.941  934.03 175.542  945.74 195.908  951.34 223.601  956.91 241.662  958.87
#Mann= 3 ,0,0
-406.617    .135       0 -20.464     .04       0   18.12     .13       0
#XS Ineff= 2 ,-1
-406.617    -140     930     120 241.662     920
Permanent Ineff=
       F       F
Bank Sta=-20.464,18.12
XS Rating Curve= 0 ,0
Skew Angle= 10
Exp/Cntr=0.5,0.3

Type RM Length L Ch R = 1 ,29585.08,525.2546,524.8339,510.5764
XS GIS Cut Line= 3
   1478107.04823   1117874.35433    1477866.1624   1117950.30906
   1477733.78346   1118000.22244
#Sta/Elev= 30
 -252.81   928.5 -210.91  923.95 -193.67  920.96 -168.93  914.77 -140.09  909.02
 -117.28  907.97  -78.77  902.36  -52.13  901.53  -35.63  904.36  -27.87  898.97
  -17.37  897.95  -15.82  895.98  -13.99  895.41   -4.08895.0099    -.02  893.65
   11.74   892.3   16.63  892.93   17.95  897.99    18.4  900.84    20.3  902.49
   24.98  902.96   37.82   910.1    46.9  914.48   58.13  916.54   62.78   920.3
   68.89  924.09   74.92  926.46   98.59  937.72  127.78  949.61  141.25  954.14
#Mann= 3 ,0,0
 -252.81    .135       0  -17.37     .04       0   17.95     .13       0
Bank Sta=-17.37,17.95
XS Rating Curve= 0 ,0
Exp/Cntr=0.3,0.1

Type RM Length L Ch R = 1 ,29060.25,559.6938,553.8696,444.6545
XS GIS Cut Line= 3
       1477886.5   1117375.23753    1477752.8189   1117441.20965
   1477547.95768   1117557.52953
#Sta/Elev= 30
 -147.81  929.64 -132.49   930.9 -101.73  927.17  -93.25  924.88  -48.21  906.08
  -41.98  904.01  -31.45  902.49  -28.53  900.06  -19.99  899.64  -16.84  894.94
  -15.63  893.84  -10.51  892.56    6.95  892.04   13.06  892.51   15.18  895.33
   20.01  900.22   25.96  900.31   30.22  903.09   35.47  904.07   48.11  903.22
    57.5  903.88   84.79   900.7   95.55  902.27     117   909.8  126.21  911.34
  135.13  911.78  142.79  914.77  152.59  920.52  171.01  926.34  236.84  942.51
#Mann= 3 ,0,0
 -147.81    .135       0  -16.84     .04       0   15.18     .13       0
Bank Sta=-16.84,15.18
XS Rating Curve= 0 ,0
Exp/Cntr=0.3,0.1

Type RM Length L Ch R = 1 ,28506.38,675.5677,696.8746,683.6249
XS GIS Cut Line= 3
   1477360.45735   1117017.59744   1477299.69324   1117258.91765
   1477252.81791   1117475.93176
#Sta/Elev= 30
 -255.76  988.36 -237.05   984.6 -212.58  978.68 -199.74  974.87 -173.68  965.43
 -151.56  955.71 -114.07  937.56 -105.09  932.18  -89.26  924.26  -55.66  902.75
  -35.54  895.48  -31.78  894.86  -26.23  895.81  -18.85  895.28  -16.84  893.97
  -15.63  892.87  -10.51  891.59    6.95  891.07   13.06  891.54   15.18  894.36
   19.73  897.03   40.34  899.02   42.94  900.56    48.8  901.96   65.29  901.74
   81.17  903.16    95.1  905.37  166.96  922.68  195.92  928.56  215.11  931.58
#Mann= 3 ,-1,0
 -255.76     .14       0  -16.84     .04       015.18001     .13       0
Bank Sta=-16.84,15.18
XS Rating Curve= 0 ,0
Exp/Cntr=0.3,0.1

Type RM Length L Ch R = 1 ,27809.50,648.7662,690.5974,614.9048
XS GIS Cut Line= 3
    1476778.8586   1116717.68406   1476635.62959   1117131.74705
    1476487.1916   1117569.24803
#Sta/Elev= 30
 -428.32  939.11 -378.33  931.18 -354.24  925.13 -337.93  924.54 -310.62  919.09
 -265.07   911.7 -197.96  903.11 -155.14  900.16  -72.85  899.38  -35.26  900.44
  -30.62  899.62  -20.04  897.87  -16.84  894.23  -15.63  893.13  -10.51  891.85
    6.95  891.33   13.06   891.8   15.18  894.62      20  895.82   22.98  895.22
   29.25  900.02   37.12  902.15   93.27  900.59  141.78  901.17  203.64  908.45
  255.63  911.88  366.47  914.74  426.27  918.49  439.29  920.83  471.81  922.09
#Mann= 6 ,-1,0
 -428.32      .1       0  -30.62     .12       0  -16.84    .045       0
15.17999     .12       049.35999      .1       0  255.63     .13       0
Bank Sta=-16.84,15.18
XS Rating Curve= 0 ,0
Exp/Cntr=0.3,0.1

Type RM Length L Ch R = 1 ,27118.91,335.1646,624.3409,764.4692
BEGIN DESCRIPTION:
TWE_15X
END DESCRIPTION:
XS GIS Cut Line= 5
   1476604.37927   1116334.87041   1476195.52428   1116556.22539
   1476077.06693    1116877.9626   1475956.37434   1117235.91404
   1476062.71161   1117566.64403
#Sta/Elev= 30
 -807.49     939 -773.33  931.24 -706.15  912.57 -695.71  910.75 -677.36  903.54
 -638.16  903.02 -629.96  904.67 -605.11  901.05 -528.12  898.81 -415.78  898.07
 -245.71  900.31 -124.73  899.35  -48.63  899.95  -24.53  895.35  -16.84  892.39
  -10.51  890.01    6.95  889.49   13.06  889.96   15.18  892.78   25.14  898.82
   31.07  900.55   70.61  899.86   103.3  897.26  143.47   898.2  262.92  897.38
  361.15  902.92  381.55  902.81  405.36  904.51  545.26  908.64  725.44  920.28
#Mann= 5 ,-1,0
 -807.49      .1       0  -48.63     .12       0  -16.84    .045       0
15.17999     .12       039.66998      .1       0
#XS Ineff= 2 , 0
         -631.09  912.19
Permanent Ineff=
       F       F
Bank Sta=-16.84,15.18
XS Rating Curve= 0 ,0
Exp/Cntr=0.3,0.1

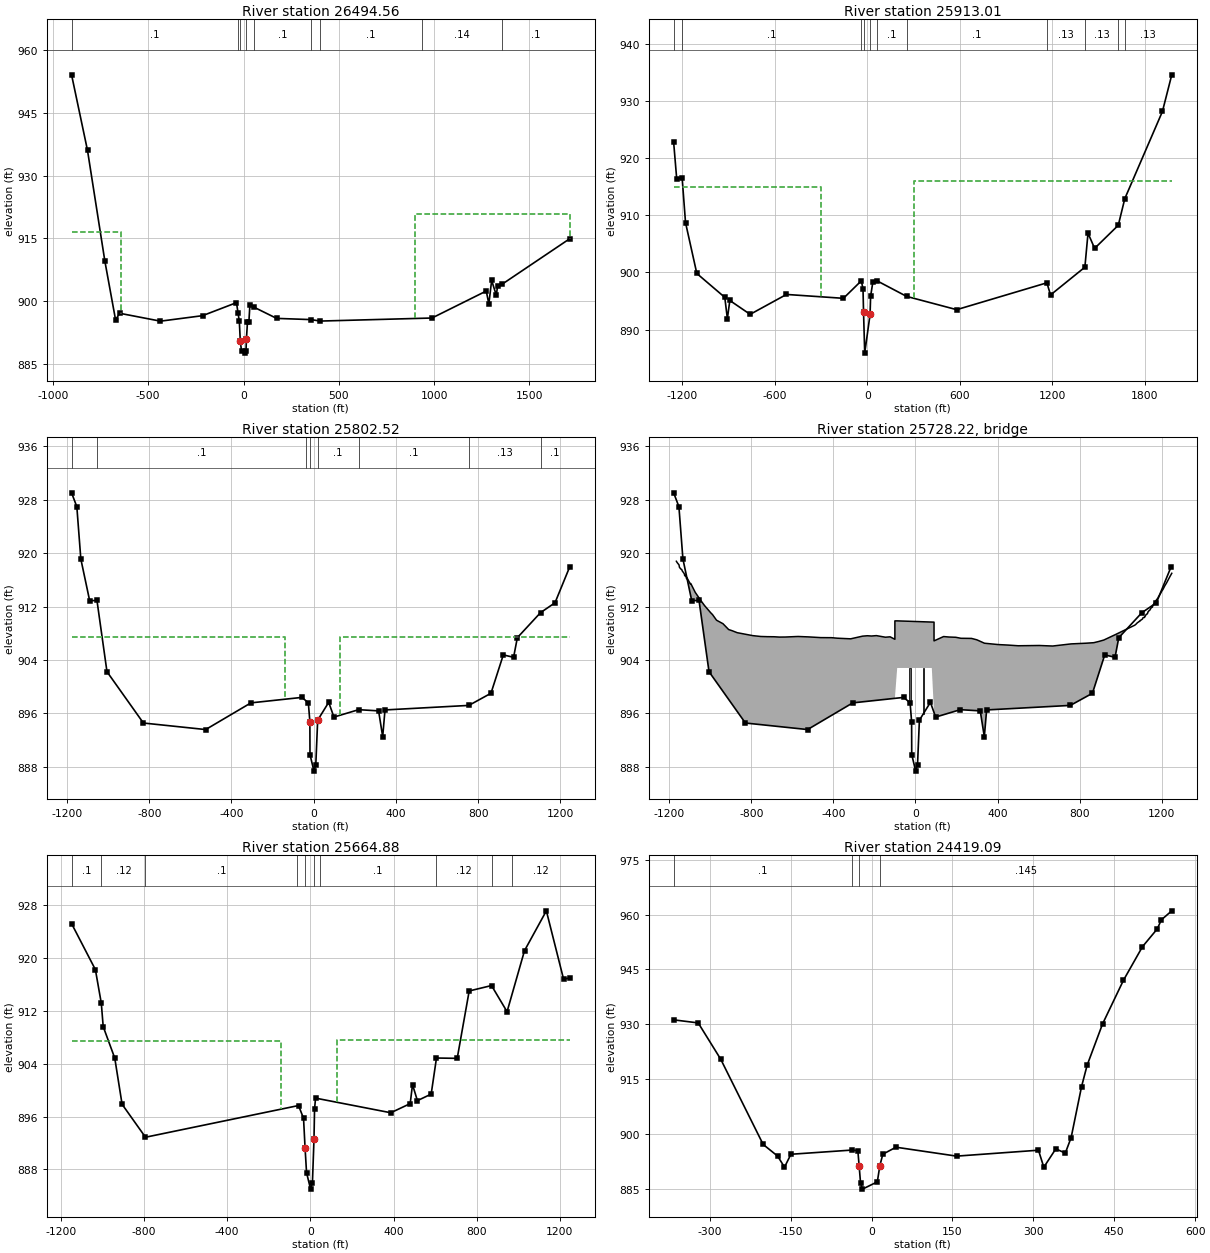
Type RM Length L Ch R = 1 ,26494.56,575.6857,581.5507,592.2119
XS GIS Cut Line= 3
   1476584.84777   1115963.77625   1475807.93701   1116389.12434
   1474314.87795   1117257.18143
#Sta/Elev= 30
 -901.87   954.1 -818.26  936.03 -727.05  909.53 -671.11  895.56 -649.38  897.12
 -435.53  895.24 -214.75  896.55  -36.95  899.66  -28.71  897.23  -21.88  895.16
  -16.84   890.5  -10.51  888.12    6.95   887.6   13.06  888.07   15.18  890.89
   20.89  895.07   28.15  894.97   33.45  899.07   56.12  898.55  173.89   895.9
  354.96  895.61  401.79  895.26  988.69  895.99 1273.45  902.44 1286.94  899.35
 1301.65  904.96 1325.94  901.46 1332.65  903.54 1356.64  904.07 1710.92  914.93
#Mann= 9 ,-1,0
 -901.87      .1       0  -28.71     .12       0  -16.84    .045       0
15.17999     .12       0   56.12      .1       0  354.96     .14       0
  401.79      .1       0935.7001     .14       0 1356.64      .1       0
#XS Ineff= 2 , 0
         -640.37  916.44  898.15          920.86
Permanent Ineff=
       F       F
Bank Sta=-16.84,15.18
XS Rating Curve= 0 ,0
Exp/Cntr=0.3,0.1

Type RM Length L Ch R = 1 ,25913.01,85.88181,110.4947,145.8901
BEGIN DESCRIPTION:
TWE_14USX
END DESCRIPTION:
XS GIS Cut Line= 6
   1476715.05643   1115304.05249   1475660.69915    1115811.4416
   1475593.04396   1115864.89698    1475514.5315   1115923.92126
   1474334.68832   1116633.46621   1473897.18734   1116390.41043
#Sta/Elev= 30
-1256.71   922.8-1237.02  916.43-1201.79  916.62 -1179.8  908.75 -1106.5  899.83
 -925.01  895.64  -908.3  891.91 -892.27  895.09 -760.54  892.66  -524.8  896.15
 -155.33  895.47  -39.15  898.54  -28.22  897.12  -24.72  893.03  -17.13  885.86
   17.58  892.64   21.18  895.85   35.94  898.36   63.37  898.53  254.61  895.81
  579.62  893.48 1165.01  898.19 1188.41  896.06 1411.34  900.93 1431.63  906.89
 1474.59  904.23 1628.11  908.28 1670.38  912.95 1914.45  928.23 1975.08  934.66
#Mann= 11 ,-1,0
-1256.71     .12       0-1201.79      .1       0  -39.15     .12       0
-24.7198    .045       017.57996     .12       0   63.37      .1       0
  254.61      .1       0 1165.01     .13       0 1411.34     .13       0
 1628.11      .1       0 1670.38     .13       0
#XS Ineff= 2 , 0
         -299.48  915.05  300.29          916.01
Permanent Ineff=
       F       F
Bank Sta=-24.72,17.58
XS Rating Curve= 0 ,0
Exp/Cntr=0.5,0.3

Type RM Length L Ch R = 1 ,25802.52,124.8866,137.6429,124.5588
BEGIN DESCRIPTION:
Shady Grove RD (TWE_14) - US
END DESCRIPTION:
XS GIS Cut Line= 6
   1476759.38911   1115198.56726   1475535.42848   1115775.82579
    1474715.1145   1116164.28117   1474564.28937   1116206.59875
   1474397.18832   1116226.13058   1474184.51444    1116230.4708
#Sta/Elev= 30
-1178.08  929.05-1152.49  926.97-1133.01  919.13-1089.97  912.87-1054.58  912.93
-1005.82  902.24-828.613  894.55-525.582  893.57 -305.43  897.57 -57.192  898.39
 -26.041  897.58 -18.628  894.76 -18.022  889.83    1.29  887.34  10.262  888.32
  19.347  894.98  73.058  897.65  98.406  895.44 218.723  896.55 315.788  896.37
 335.697   892.5 346.956  896.51 755.001  897.19 862.535  899.01 922.508  904.76
  972.59   904.4 990.889  907.341103.585  911.091174.097  912.571245.483  917.94
#Mann= 8 ,-1,0
-1178.08     .12       0-1054.58      .1       0-38.2088     .12       0
 -18.628    .045       019.34705      .1       0 218.723      .1       0
 755.001     .13       01103.585      .1       0
#XS Ineff= 2 , 0
            -140   907.4     130           907.5
Permanent Ineff=
       F       F
Bank Sta=-18.628,19.347
XS Rating Curve= 0 ,0
Skew Angle= 30
Exp/Cntr=0.5,0.3

Type RM Length L Ch R = 3 ,25728.22,,,
BEGIN DESCRIPTION:
Shady Grove RD (TWE_14) - TOR
Skew = 30 Degrees
END DESCRIPTION:
Bridge Culvert--1,0,-1,-1, 0
Deck Dist Width WeirC Skew NumUp NumDn MinLoCord MaxHiCord MaxSubmerge Is_Ogee
52.6,43.4,2.6,30, 164, 164, 905.93, , 0.95, 0, 0,0,,
-1164.89-1164.77-1160.34 -1154.4-1152.03 -1151.8-1149.83-1143.38-1138.84 -1135.7
-1127.87-1125.65-1124.21-1122.77-1121.62-1117.94 -1116.7-1115.34 -1115.2-1112.69
-1112.22 -1110.6-1099.83-1096.92-1094.73 -1072.7-1045.73-1027.84-997.427-988.715
-969.212-938.018-910.149-892.656-868.537-818.281-793.097 -753.91-721.174-689.815
-662.319-633.628-572.183-522.326-461.107-408.054-379.397-315.536-257.556-236.105
-234.199-213.882-190.465-167.896-146.176-123.435 -100.13 -100.13 -88.872  79.804
   90.63   90.63 137.213 163.202 196.484 221.625 273.525 299.333 336.477  402.52
  452.49 500.277 603.992 668.857 717.433 759.063 829.834  869.03 894.292 918.091
 976.894 1068.711074.7121080.8171087.9361089.5291093.6081094.9851097.3581100.883
1106.0881109.4221112.7731116.2811117.398 1118.81 1120.811122.689 1125.591130.007
1130.9861132.3631132.6661135.922    11361139.1261141.7161143.3091144.8331146.895
1148.1851150.8441154.3251157.556 1159.141160.2921161.6431163.5221165.6441167.212
1168.5971170.2171171.1951172.7111175.1961175.2831177.6391179.3271181.3021183.294
1185.0081187.1561187.9271191.6081192.9071194.8471195.9121197.0721199.2721201.298
1202.4761203.4381205.3081207.6381208.8331211.8641215.3021215.4231218.6541220.585
1222.646 1225.01  1227.61229.2621231.3491234.225  1234.91237.6111239.2481240.521
1243.6211245.743 1248.151249.068
  918.79  918.78  918.57  918.35  918.25  918.21  917.88  917.64  917.55  917.32
     917  916.85  916.62  916.73  916.73  916.46  916.38  916.18  916.17  916.31
  916.29  916.17  915.58  915.39  915.46  914.12  912.91  912.16  911.07   910.8
  909.96  909.44  908.56  908.38  908.09   907.8  907.65  907.52  907.49  907.48
  907.43  907.44  907.52  907.46  907.35  907.34  907.26  907.17  907.57  907.63
  907.63  907.59  907.65  907.53  907.41  907.47   907.1  909.86  909.86  909.67
  909.67  906.86  907.51  907.44   907.4  907.25  907.23  907.02  906.51  906.31
  906.23  906.13  906.17  906.09  906.27  906.41  906.51  906.59  906.78  906.99
  907.84  909.21  909.36  909.56  909.71  909.77   909.8  909.92  909.94  910.02
  910.13  910.35  910.36  910.37  910.47  910.52  910.63  910.74  910.85  910.91
  910.98  911.09  911.18   911.3   911.3  911.41  911.45  911.53  911.63  911.74
  911.79  911.87   911.9  912.19  912.25  912.32  912.38   912.5  912.54  912.59
   912.7  912.83  912.87  912.93  913.04  913.04  913.13  913.19  913.25  913.35
  913.54  913.58  913.62  913.86  913.89  914.02  914.05  914.14  914.27  914.35
  914.38  914.43  914.53  914.66  914.72  914.92  915.13  915.13  915.28  915.39
  915.49  915.63  915.78  915.89  916.04  916.15  916.19   916.4  916.46  916.52
  916.68  916.82  916.93  916.99
                                                                                
                                                                                
                                                                                
                                                                                
                                                                                
                                                     890     890   902.8   902.8
     890     890
                                                                                
                                                                                
                                                                                
                                                                                
                                                                                
                                                                                
                                                                                
                                                                                
                                                                                
                                
-1164.89-1164.77-1160.34 -1154.4-1152.03 -1151.8-1149.83-1143.38-1138.84 -1135.7
-1127.87-1125.65-1124.21-1122.77-1121.62-1117.94 -1116.7-1115.34 -1115.2-1112.69
-1112.22 -1110.6-1099.83-1096.92-1094.73 -1072.7-1045.73-1027.84-997.427-988.715
-969.212-938.018-910.149-892.656-868.537-818.281-793.097 -753.91-721.174-689.815
-662.319-633.628-572.183-522.326-461.107-408.054-379.397-315.536-257.556-236.105
-234.199-213.882-190.465-167.896-146.176-123.435 -100.13 -100.13 -88.872  79.804
   90.63   90.63 137.213 163.202 196.484 221.625 273.525 299.333 336.477  402.52
  452.49 500.277 603.992 668.857 717.433 759.063 829.834  869.03 894.292 918.091
 976.894 1068.711074.7121080.8171087.9361089.5291093.6081094.9851097.3581100.883
1106.0881109.4221112.7731116.2811117.398 1118.81 1120.811122.689 1125.591130.007
1130.9861132.3631132.6661135.922    11361139.1261141.7161143.3091144.8331146.895
1148.1851150.8441154.3251157.556 1159.141160.2921161.6431163.5221165.6441167.212
1168.5971170.2171171.1951172.7111175.1961175.2831177.6391179.3271181.3021183.294
1185.0081187.1561187.9271191.6081192.9071194.8471195.9121197.0721199.2721201.298
1202.4761203.4381205.3081207.6381208.8331211.8641215.3021215.4231218.6541220.585
1222.646 1225.01  1227.61229.2621231.3491234.225  1234.91237.6111239.2481240.521
1243.6211245.743 1248.151249.068
  918.79  918.78  918.57  918.35  918.25  918.21  917.88  917.64  917.55  917.32
     917  916.85  916.62  916.73  916.73  916.46  916.38  916.18  916.17  916.31
  916.29  916.17  915.58  915.39  915.46  914.12  912.91  912.16  911.07   910.8
  909.96  909.44  908.56  908.38  908.09   907.8  907.65  907.52  907.49  907.48
  907.43  907.44  907.52  907.46  907.35  907.34  907.26  907.17  907.57  907.63
  907.63  907.59  907.65  907.53  907.41  907.47   907.1  909.86  909.86  909.67
  909.67  906.86  907.51  907.44   907.4  907.25  907.23  907.02  906.51  906.31
  906.23  906.13  906.17  906.09  906.27  906.41  906.51  906.59  906.78  906.99
  907.84  909.21  909.36  909.56  909.71  909.77   909.8  909.92  909.94  910.02
  910.13  910.35  910.36  910.37  910.47  910.52  910.63  910.74  910.85  910.91
  910.98  911.09  911.18   911.3   911.3  911.41  911.45  911.53  911.63  911.74
  911.79  911.87   911.9  912.19  912.25  912.32  912.38   912.5  912.54  912.59
   912.7  912.83  912.87  912.93  913.04  913.04  913.13  913.19  913.25  913.35
  913.54  913.58  913.62  913.86  913.89  914.02  914.05  914.14  914.27  914.35
  914.38  914.43  914.53  914.66  914.72  914.92  915.13  915.13  915.28  915.39
  915.49  915.63  915.78  915.89  916.04  916.15  916.19   916.4  916.46  916.52
  916.68  916.82  916.93  916.99
                                                                                
                                                                                
                                                                                
                                                                                
                                                                                
                                                     890     890   902.7  902.62
     890     890
                                                                                
                                                                                
                                                                                
                                                                                
                                                                                
                                                                                
                                                                                
                                                                                
                                                                                
                                
Pier Skew, UpSta & Num, DnSta & Num=  ,-25.981, 4 ,-25.981, 4 , 3 , 3 , 0 ,,
     4.5     4.5     6.5     6.5
     890   900.8   900.8   902.9
     4.5     4.5     6.5     6.5
     890   900.8   900.8   902.9
Pier Skew, UpSta & Num, DnSta & Num=  ,38.971, 4 ,38.971, 4 , 3 , 3 , 0 ,,
     4.5     4.5     6.5     6.5
     890   900.8   900.8   902.9
     4.5     4.5     6.5     6.5
     890   900.8   900.8   902.9
Abutment Skew #Up #Dn= , 2 , 2
  -88.87  -26.04
   902.8  897.58
  -88.87  -26.04
  902.62     892
Abutment Skew #Up #Dn= , 2 , 2
   40.47    79.8
  897.05   902.8
   40.47    79.8
  897.05   902.8
BR Coef=-1 ,-1 , 0 ,, 0 ,,,0.8,-1,1.2,0,
WSPro=,,,, 1 ,,,, 0 ,,,, 0 ,,,,-1 ,-1 ,-1 , 0 , 0 , 0 , 0 , 0
BC Design=,, 0 ,, 0 ,,,,,,
BC Use User HTab Curves=0
BC User HTab FreeFlow(D)= 0

Type RM Length L Ch R = 1 ,25664.88,778.3932,1245.781,1447.994
BEGIN DESCRIPTION:
Shady Grove RD (TWE_14) - DS
END DESCRIPTION:
XS GIS Cut Line= 5
   1476742.02822    1115077.0397    1475546.2792   1115641.27657
   1474856.17388    1115968.9685    1474556.6939   1116103.51739
   1474207.30085   1116127.38878
#Sta/Elev= 30
-1147.51  925.15-1033.05   918.2 -1004.6  913.12-995.505  909.59-939.854  904.82
-904.702  897.85-792.197  892.87 -56.603  897.66 -32.485  895.73 -25.141  891.26
 -18.022  887.52    1.29  885.03  10.262  886.01   17.71  892.54   20.43  897.14
  25.279  898.78 386.871  896.57 480.159  897.95 491.288  900.82 514.869   898.4
 581.042  899.39 606.495  904.84 706.174  904.79 763.713  914.97 870.996  915.79
  945.83  911.841029.635  921.061134.658  927.081217.554  916.741246.747  916.95
#Mann= 10 ,-1,0
-1147.51      .1       0 -1004.6     .12       0-792.197      .1       0
-63.5318     .14       0-25.1408    .045       017.70996     .14       0
46.62695      .1       0 606.495     .12       0 870.996     .06       0
971.6631     .12       0
#XS Ineff= 2 ,-1
-1147.51    -140   907.4     1301246.747   907.5
Permanent Ineff=
       F       F
Bank Sta=-25.141,17.71
XS Rating Curve= 0 ,0
Skew Angle= 30
Exp/Cntr=0.5,0.3

Type RM Length L Ch R = 1 ,24419.09,602.4268,685.2051,612.0017
BEGIN DESCRIPTION:
TWE_13X
END DESCRIPTION:
XS GIS Cut Line= 4
   1476384.83694   1114989.85171   1476212.22671   1114964.61581
   1476078.12369   1114829.47835   1475688.55643   1114428.74672
#Sta/Elev= 30
 -366.99  931.18 -321.47  930.34 -279.78  920.42 -201.03  897.09  -174.2   893.9
 -161.46  890.87 -149.51   894.4  -36.12  895.55  -25.42  895.38  -23.07  891.29
  -20.44  886.56  -16.86  884.86   10.66  886.85    15.4  891.29    20.9  894.42
   45.29  896.33  157.65  893.89  309.52  895.51  319.43  890.85  341.68  895.88
  359.27  894.71   370.1  898.96  389.34  912.86  399.79  918.77  428.31  930.04
  467.13  942.01   502.4   951.2  529.76  956.05  537.46  958.55  556.72  961.01
#Mann= 4 ,-1,0
 -366.99      .1       0  -36.12     .14       0  -23.07    .045       0
15.39999    .145       0
Bank Sta=-23.07,15.4
XS Rating Curve= 0 ,0
Exp/Cntr=0.3,0.1

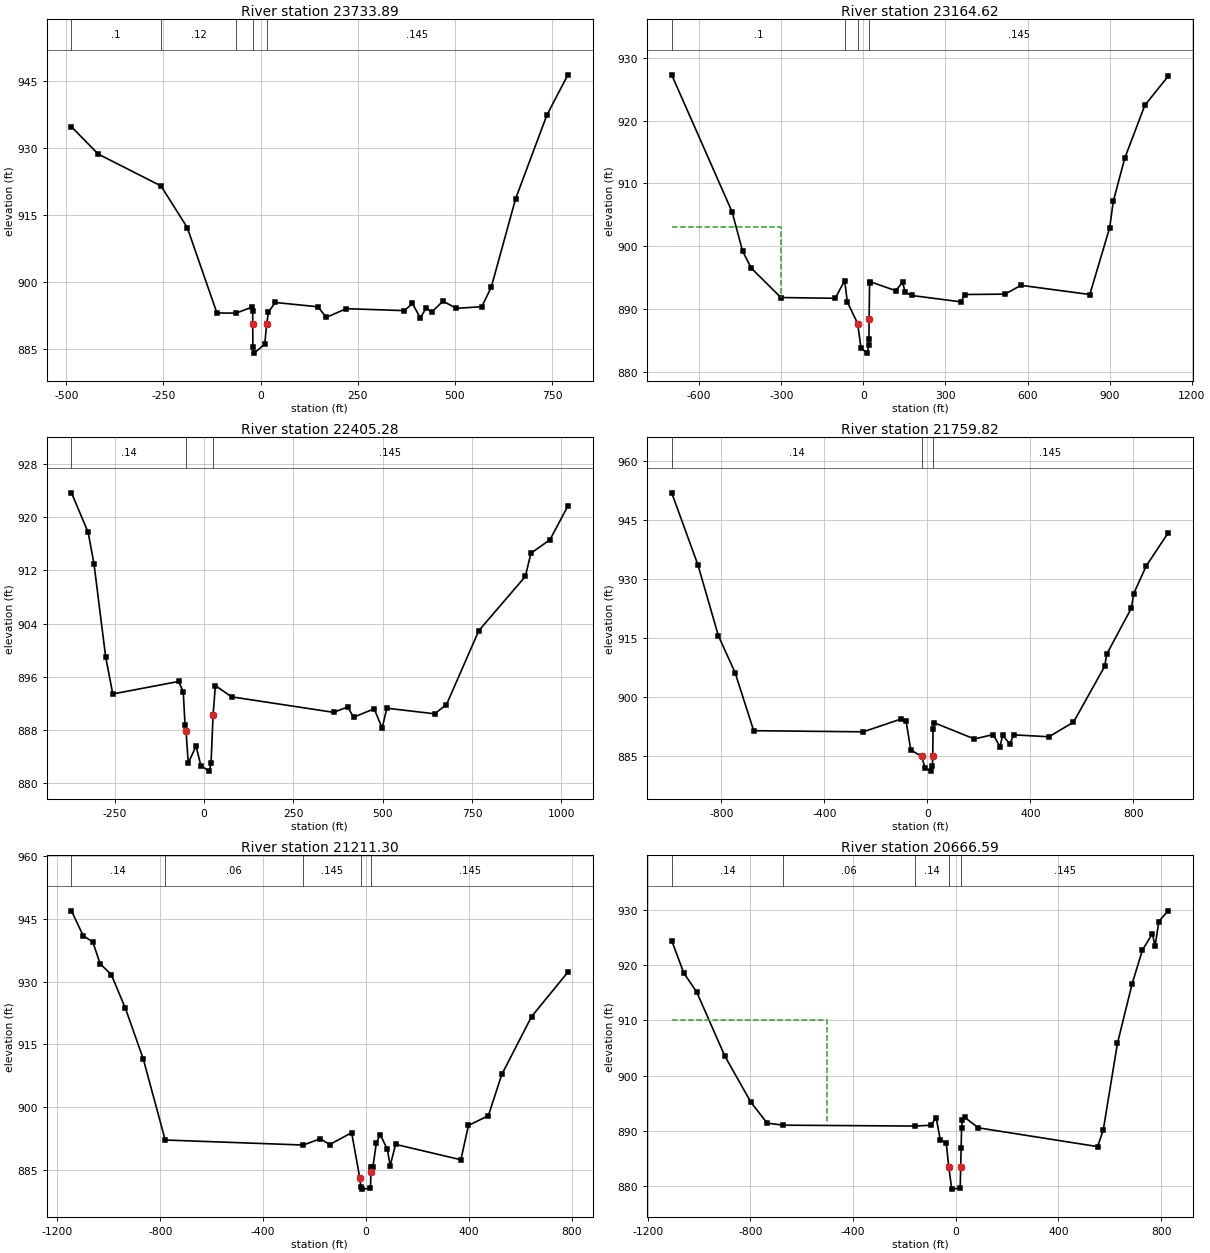
Type RM Length L Ch R = 1 ,23733.89,579.1484,569.2657,513.473
XS GIS Cut Line= 4
   1476972.87861   1114927.45079   1476636.50656   1114569.37697
   1476361.01772   1114257.02723   1476000.65453   1114176.58104
#Sta/Elev= 30
 -486.55  934.67 -418.13  928.58 -256.43  921.45 -188.77  912.14 -112.45  893.04
  -63.14     893   -21.9  894.36  -20.32  893.43   -20.3  890.49  -19.87  885.49
  -16.86  884.06   10.66  886.05    15.4  890.49   20.25   893.3   37.96  895.38
  147.63  894.42  168.79  892.04  220.13     894  369.97  893.56  390.57  895.16
  410.77  891.93  425.79  894.12  439.83  893.24  469.31  895.68  503.53  894.07
  568.88  894.44  593.26  898.76  655.78  918.51  736.26  937.24  790.45  946.28
#Mann= 5 ,-1,0
 -486.55      .1       0 -256.43     .12       0  -63.14     .14       0
-20.2999    .045       015.39999    .145       0
Bank Sta=-20.3,15.4
XS Rating Curve= 0 ,0
Exp/Cntr=0.3,0.1

Type RM Length L Ch R = 1 ,23164.62,718.7921,759.3404,449.3556
XS GIS Cut Line= 4
   1477552.30676   1114699.58563   1477051.00361    1114202.6227
   1476736.33301   1113937.86549   1476039.71686   1113913.99377
#Sta/Elev= 30
  -700.6  927.27 -479.65  905.46 -441.53  899.24 -409.61  896.53 -301.46  891.86
 -102.98  891.74  -68.39  894.55  -58.74  891.16  -20.73   887.7   -8.79  883.82
    14.5  883.02   19.54  884.25   20.29   885.2   20.95  888.41   22.67  894.19
   24.63  894.38  118.11  892.95  143.03  894.28  152.96  892.71  176.29  892.19
  356.84  891.17  370.04  892.34  517.34   892.4  576.03   893.8  827.48  892.34
  900.23  902.98  913.33  907.16  955.07  913.99 1028.51  922.42 1113.54  927.03
#Mann= 4 ,-1,0
  -700.6      .1       0-65.8399     .14       0-20.7299    .045       0
20.95001    .145       0
#XS Ineff= 2 , 0
         -300.44  903.05
Permanent Ineff=
       F       F
Bank Sta=-20.73,20.95
XS Rating Curve= 0 ,0
Exp/Cntr=0.3,0.1

Type RM Length L Ch R = 1 ,22405.28,577.6611,645.4652,592.8043
BEGIN DESCRIPTION:
TWE_12X
END DESCRIPTION:
XS GIS Cut Line= 4
   1477572.31332   1113776.79692   1477215.76673   1113676.70997
   1477117.44488   1113657.45735   1476291.06332   1113255.96358
#Sta/Elev= 30
 -371.09  923.63 -324.44  917.69 -308.15  912.98 -275.51     899 -255.54  893.42
  -71.11   895.3  -58.23  893.73  -53.24   888.7  -50.38  887.83  -44.28  883.02
  -22.55   885.6   -8.79  882.63    14.5  881.83   19.54  883.06   25.19  890.26
   31.62  894.68   76.79  892.99  362.51  890.66   401.8  891.46  418.61  889.93
  476.12  891.19   498.4  888.29  511.38  891.28  645.45  890.44  678.44  891.83
  768.98  902.93  899.13  911.07  914.81  914.56  967.96  916.58 1018.18  921.64
#Mann= 3 ,-1,0
 -371.09     .14       0  -50.38    .045       0   25.19    .145       0
Bank Sta=-50.38,25.19
XS Rating Curve= 0 ,0
Exp/Cntr=0.3,0.1

Type RM Length L Ch R = 1 ,21759.82,703.4542,548.5153,484.4774
XS GIS Cut Line= 3
   1478208.34121    1113433.0899    1477291.6729   1113071.97802
   1476399.30971   1112766.42192
#Sta/Elev= 30
 -993.24  951.97 -891.53  933.64 -811.65  915.49 -746.84  906.11 -674.63  891.33
 -249.12  891.04 -102.69  894.29  -83.06  893.91  -64.33   886.4  -22.55  884.79
   -8.79  881.82    14.5  881.02   19.54  882.25   20.89   884.8   22.18  891.73
   24.83   893.4  182.81  889.22  255.79  890.34  282.19  887.24   292.6  890.14
  320.56  887.96  335.19  890.27  472.34  889.78  567.74   893.5  688.86  907.73
  697.18  910.87  792.75  922.58  801.71  926.27  850.47  933.35  935.22  941.72
#Mann= 3 ,-1,0
 -993.24     .14       0-22.5499    .045       020.89001    .145       0
Bank Sta=-22.55,20.89
XS Rating Curve= 0 ,0
Exp/Cntr=0.3,0.1

Type RM Length L Ch R = 1 ,21211.30,610.2067,544.715,527.129
XS GIS Cut Line= 3
   1478558.16798    1112492.5502   1477412.33235   1112548.97375
   1476631.08104   1112601.05709
#Sta/Elev= 30
-1145.45  946.94-1100.25  941.03-1062.05  939.45-1034.45  934.33 -990.45  931.67
 -935.85  923.65 -866.45  911.57 -781.05  892.16 -243.75  890.96 -178.05  892.46
 -141.45  891.08  -55.95   893.9  -24.55  883.16  -20.25  881.02  -15.75  880.42
   17.15  880.62   19.05  884.43   20.85  885.75   26.55  885.65   40.05  891.47
   55.25  893.46   82.95   889.9   93.95  886.06  114.95  891.12  368.85  887.44
  398.25  895.64  475.65  897.97  527.85  907.82  643.65  921.66  784.85  932.28
#Mann= 5 ,-1,0
-1145.45     .14       0 -781.05     .06       0 -243.75    .145       0
  -20.25     .04       0   20.85    .145       0
Bank Sta=-24.55,19.05
XS Rating Curve= 0 ,0
Exp/Cntr=0.3,0.1

Type RM Length L Ch R = 1 ,20666.59,564.6,564.6,564.6
BEGIN DESCRIPTION:
TWE_11X
END DESCRIPTION:
XS GIS Cut Line= 4
   1478404.08793   1111901.40289   1477303.00787   1112023.66371
   1477126.72736   1112046.60039    1476716.8107   1112548.89272
#Sta/Elev= 30
-1106.95  924.42-1060.05  918.57-1009.25  915.09 -899.75  903.54 -797.75  895.17
 -734.95  891.44 -672.55  891.07 -160.65  890.91  -98.05  891.05  -76.55   892.4
  -60.35  888.42  -37.45  887.88  -27.35  883.53  -15.75  879.52   17.15  879.72
   19.05  883.53   20.75  886.98   22.55   890.6   25.85  892.04   34.25   892.5
   87.85  890.59  552.35   887.2  574.45  890.18  629.75  905.83  686.75  916.56
  727.05  922.69  765.85  925.64  776.45   923.4  791.05  927.85  827.05  929.78
#Mann= 5 ,-1,0
-1106.95     .14       0 -672.55     .06       0 -160.65     .14       0
  -27.35     .04       0   20.75    .145       0
#XS Ineff= 2 , 0
         -499.96     910
Permanent Ineff=
       F       F
Bank Sta=-27.35,19.05
XS Rating Curve= 0 ,0
Exp/Cntr=0.3,0.1

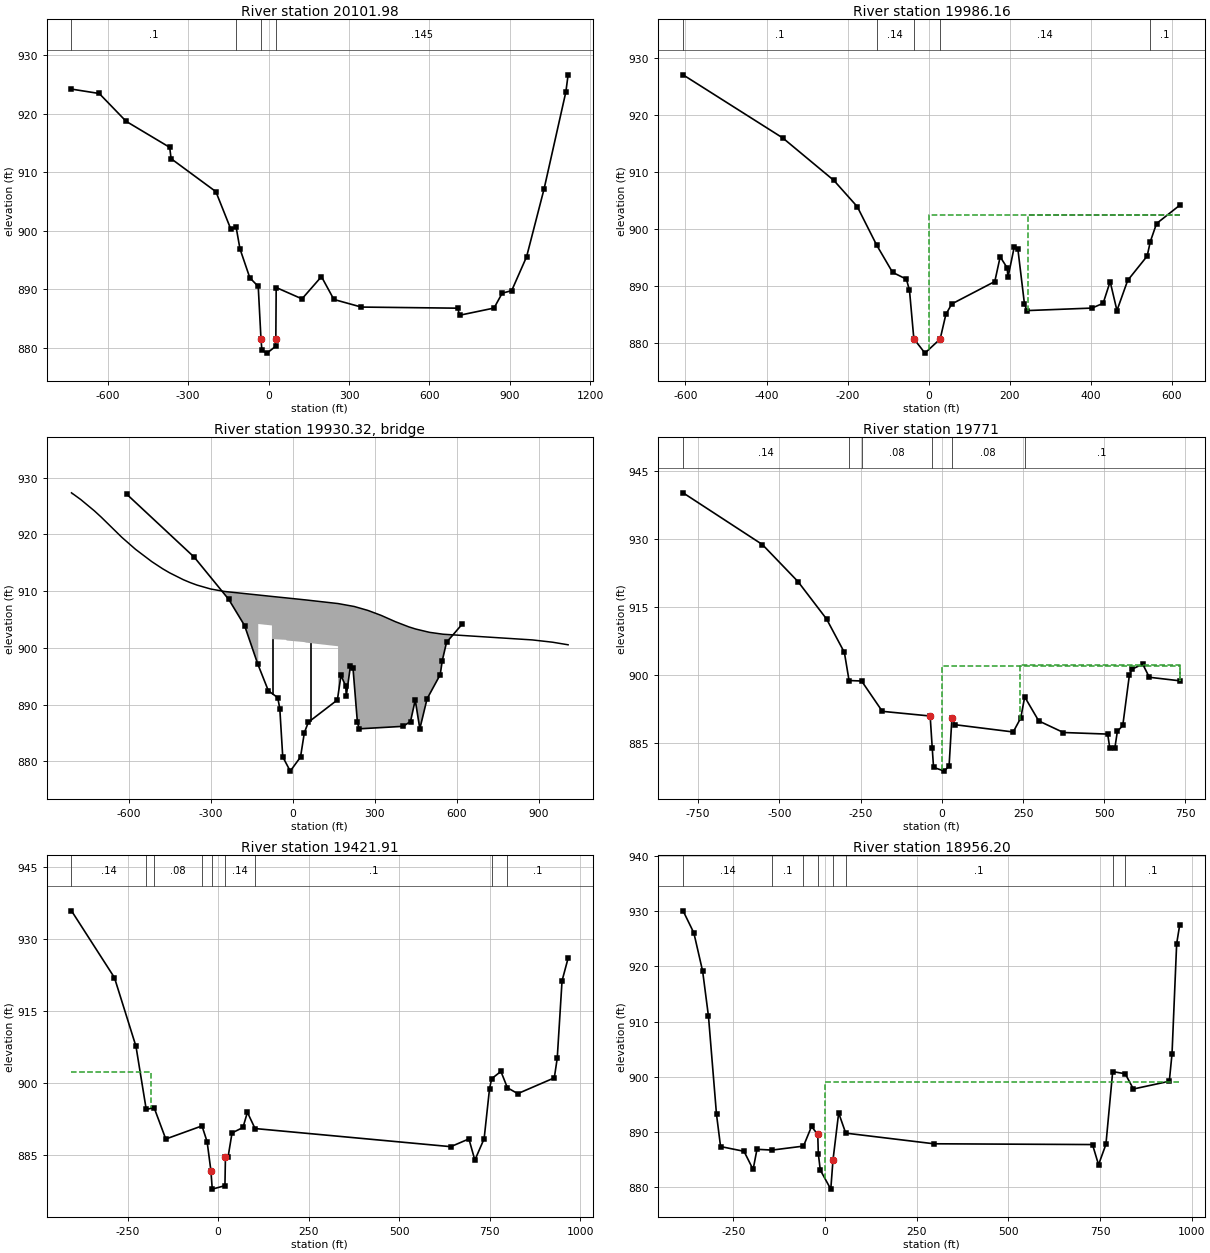
Type RM Length L Ch R = 1 ,20101.98,105.6221,115.8291,169.4414
BEGIN DESCRIPTION:
TWE_10USX
END DESCRIPTION:
XS GIS Cut Line= 4
   1477888.46194   1111433.08596    1477321.6998   1111418.33793
   1477172.48917   1111494.65551     1476193.146    1112032.0456
#Sta/Elev= 30
 -734.65  924.22 -631.22  923.47 -531.05  918.72 -368.59  914.27 -363.18  912.33
 -196.31   906.7 -140.44  900.27 -120.85  900.64 -106.56  896.94  -69.64  891.97
   -38.4  890.51  -28.07  881.46  -24.67  879.57   -5.54  879.11   26.75  880.29
   27.24  881.59   28.54  890.32  124.75  888.38  197.35  892.18  243.65  888.28
  345.95  886.98  705.75  886.79  712.15  885.58  840.85  886.81  871.15  889.35
  906.65  889.79  962.15  895.57 1027.25  907.14 1108.65  923.75 1116.95  926.66
#Mann= 4 ,-1,0
 -734.65      .1       0 -120.85     .14       0  -28.07    .035       0
   27.24    .145       0
Bank Sta=-28.07,27.24
XS Rating Curve= 0 ,0
Exp/Cntr=0.5,0.3

Type RM Length L Ch R = 1 ,19986.16,164.8615,199.5731,183.0735
BEGIN DESCRIPTION:
Walhalla Hwy (TWE_10) - US
END DESCRIPTION:
XS GIS Cut Line= 6
    1477849.2818    1111415.8717    1476783.3071    1111391.5659
    1476604.4875    1111370.7326    1476408.3064    1111407.1909
    1476338.8622    1111433.2326 1476335.59345811111432.77861468
#Sta/Elev= 30
 -605.91  927.02 -359.81  915.96 -233.81  908.53 -176.01  903.93 -127.91  897.17
  -88.91  892.43  -54.81  891.23  -47.16   889.3  -36.41   880.8   -8.96  878.28
   28.61  880.76   42.61  885.05   57.12  886.89  163.39  890.82  176.69  895.15
  193.99  893.21  195.89  891.53  211.29  896.83  220.39  896.49  236.49  886.95
  242.59  885.73  403.29  886.17  430.79  887.01  448.09  890.81  464.89  885.74
  491.39  891.02  539.49  895.28  546.99  897.76  562.59  900.97  619.69  904.17
#Mann= 5 ,-1,0
 -605.91      .1       0 -127.91     .14       0  -36.41    .035       0
   28.61     .14       0  546.99      .1       0
#XS Ineff= 2 , 0
       0 -204.91   902.4  244.91       0   902.4
Permanent Ineff=
       F       F
Bank Sta=-36.41,28.61
XS Rating Curve= 0 ,0
Skew Angle= 35
Exp/Cntr=0.5,0.3

Type RM Length L Ch R = 3 ,19930.32,,,
BEGIN DESCRIPTION:
Walhalla Hwy (TWE_10) - TOR
Skew = 35 Degrees
END DESCRIPTION:
Bridge Culvert--1,0,-1,-1, 0
Deck Dist Width WeirC Skew NumUp NumDn MinLoCord MaxHiCord MaxSubmerge Is_Ogee
79,46.25,2.6,35, 35, 35, 901.51, , 0.95, 0, 0,0,,
 -808.85-774.997-724.997-700.014-624.962-574.997-515.053-474.997-449.997-399.997
-375.008-349.997-299.999-249.997 -125.91 -125.91  -75.91  -75.91 -24.997 -21.027
    41.5  50.017  165.91  165.91 225.003 275.003 323.209 375.144 425.002 450.002
 500.002 550.002 876.349     9501007.043
 927.308 926.124 924.125 923.019 919.478 917.366  915.18 913.914 913.213 912.005
 911.499 911.056 910.366 909.935  909.31  909.31 909.055 909.055 908.805 908.785
 908.472  908.43   907.8   907.8 907.285 906.592 905.723 904.613 903.687 903.311
 902.735 902.398 901.395 900.993 900.537
                                                                                
                                           904.2 903.945 901.535  901.41 901.285
  901.02  900.91  900.28
                                        
 -808.85-774.997-724.997-700.014-624.962-574.997-515.053-474.997-449.997-399.997
-375.008-349.997-299.999-249.997 -125.91 -125.91  -75.91  -75.91 -24.997 -21.027
    41.5  50.017  165.91  165.91 225.003 275.003 323.209 375.144 425.002 450.002
 500.002 550.002 876.349     9501007.043
 927.308 926.124 924.125 923.019 919.478 917.366  915.18 913.914 913.213 912.005
 911.499 911.056 910.366 909.935  909.31  909.31 909.055 909.055 908.805 908.785
 908.472  908.43   907.8   907.8 907.285 906.592 905.723 904.613 903.687 903.311
 902.735 902.398 901.395 900.993 900.537
                                                                                
                                           904.2 903.945 901.535  901.41 901.285
  901.02  900.91  900.28
                                        
Pier Skew, UpSta & Num, DnSta & Num=  ,-75, 2 ,-75, 2 , 0 , 0 , 0 ,,
       4       4
     880     910
       4       4
     880     910
Pier Skew, UpSta & Num, DnSta & Num=  ,65, 2 ,65, 2 , 0 , 0 , 0 ,,
       4       4
     880     910
       4       4
     880     910
Abutment Skew #Up #Dn= , 3 , 3
 -125.91 -123.91 -103.91
  901.08  901.08  891.28
 -125.91 -123.91 -103.91
  901.08  901.08  891.28
Abutment Skew #Up #Dn= , 3 , 3
  145.91  163.91  165.91
  889.35  898.35  898.35
  145.91  163.91  165.91
  889.35  898.35  898.35
BR Coef=-1 ,-1 , 0 ,, 0 ,,,0.8,0,1.2,0,
WSPro=,,,, 1 ,,,, 0 ,,,, 0 ,,,,-1 ,-1 ,-1 , 0 , 0 , 0 , 0 , 0
BC Design=,, 0 ,, 0 ,,9,4925.55,4925.55,25,1
BC Use User HTab Curves=0
BC User HTab FreeFlow(D)= 0

Type RM Length L Ch R = 1 ,19771   ,297.5,359.2,349.6
XS GIS Cut Line= 6
    1477797.9587       1111252.6    1477340.1051    1111254.1761
    1477007.1185    1111217.8214    1476697.2407     1111219.325
     1476533.666    1111195.4944    1476304.3001    1111316.0996
#Sta/Elev= 30
 -796.18  940.23 -552.18  928.82 -442.68  920.66 -354.58  912.39 -299.78  905.02
 -285.38  898.82 -246.78  898.71 -182.98  892.02  -35.78  890.99  -29.38  883.92
  -25.38  879.66    8.12  878.83   22.52  880.03   31.22  890.56   39.82  889.08
  219.82  887.47  243.12  890.57  255.12  895.21  298.32  889.91  374.32  887.35
  510.52     887  517.22  883.83  532.42  883.83  540.32  887.59  557.02   888.9
  577.32  900.01  585.22  901.31  618.32  902.45  638.62  899.54  732.12  898.76
#Mann= 6 ,-1,0
 -796.18     .14       0 -285.38     .06       0 -246.78     .08       0
  -29.38    .035       0   31.22     .08       0  255.12      .1       0
#XS Ineff= 2 , 0
       0 -200.23     902  240.23       0  902.33
Permanent Ineff=
       F       F
Bank Sta=-35.78,31.22
XS Rating Curve= 0 ,0
Exp/Cntr(USF)=0,0
Exp/Cntr=0.5,0.3

Type RM Length L Ch R = 1 ,19421.91,522.9336,465.7054,185.1479
XS GIS Cut Line= 4
   1477377.90814   1110938.60761   1476974.30643   1110885.60925
   1476780.65879   1110857.07185   1476199.35663   1111360.24377
#Sta/Elev= 30
 -405.13  935.83 -286.53  921.94 -227.03  907.64 -198.73  894.53 -176.93  894.89
 -144.73  888.37  -44.73   891.1  -30.53   887.8  -20.13   881.8  -16.33  877.95
   18.67  878.67   20.07  884.68   27.37  884.66   38.27  889.64   68.47  890.77
   80.67  893.92  101.87  890.55  642.47  886.78  692.47  888.39  708.97  883.98
  734.57  888.44  749.47  898.84  755.47  900.92  780.87  902.43  798.87  899.03
  827.47  897.81  928.37  901.09  936.47  905.17  949.77  921.28  966.47  925.97
#Mann= 9 ,-1,0
 -405.13     .14       0 -198.73     .06       0 -176.93     .08       0
  -44.73     .14       0  -16.33    .045       0   20.07     .14       0
  101.87      .1       0  755.47     .06       0  798.87      .1       0
#XS Ineff= 2 , 0
         -186.75  902.26
Permanent Ineff=
       F       F
Bank Sta=-20.13,20.07
XS Rating Curve= 0 ,0
Exp/Cntr=0.5,0.3

Type RM Length L Ch R = 1 ,18956.20,41.10629,40.11645,40.70418
BEGIN DESCRIPTION:
Unnamed Foot Bridge - US
END DESCRIPTION:
XS GIS Cut Line= 4
   1477022.27493   1110294.26903    1476747.2523   1110536.14403
   1476686.03609   1110595.77953   1476183.73163   1111346.35466
#Sta/Elev= 30
 -387.46  930.08 -358.06  926.08 -334.06  919.14 -318.16  910.97 -296.26  893.21
 -285.19   887.4 -221.27  886.54  -196.4  883.25 -185.84   886.9  -144.5  886.76
  -58.94  887.48  -37.06  891.03  -20.04  889.59  -18.48   886.1  -13.12  883.14
   15.54  879.69   21.53  884.95   37.02  893.48   56.28  889.83  296.97   887.9
  729.58  887.76  746.05  884.11  766.15  887.79  784.65  900.97  818.74  900.58
  841.17  897.82  939.09  899.22   946.5  904.18  959.18  924.14   967.4   927.5
#Mann= 8 ,-1,0
 -387.46     .14       0  -144.5      .1       0  -58.94     .14       0
  -20.04    .045       0   21.53     .14       0   56.28      .1       0
  784.65     .06       0  818.74      .1       0
#XS Ineff= 2 , 0
       0    -140  899.01      40       0     890
Permanent Ineff=
       F       F
Bank Sta=-20.04,21.53
XS Rating Curve= 0 ,0
Exp/Cntr=0.5,0.3