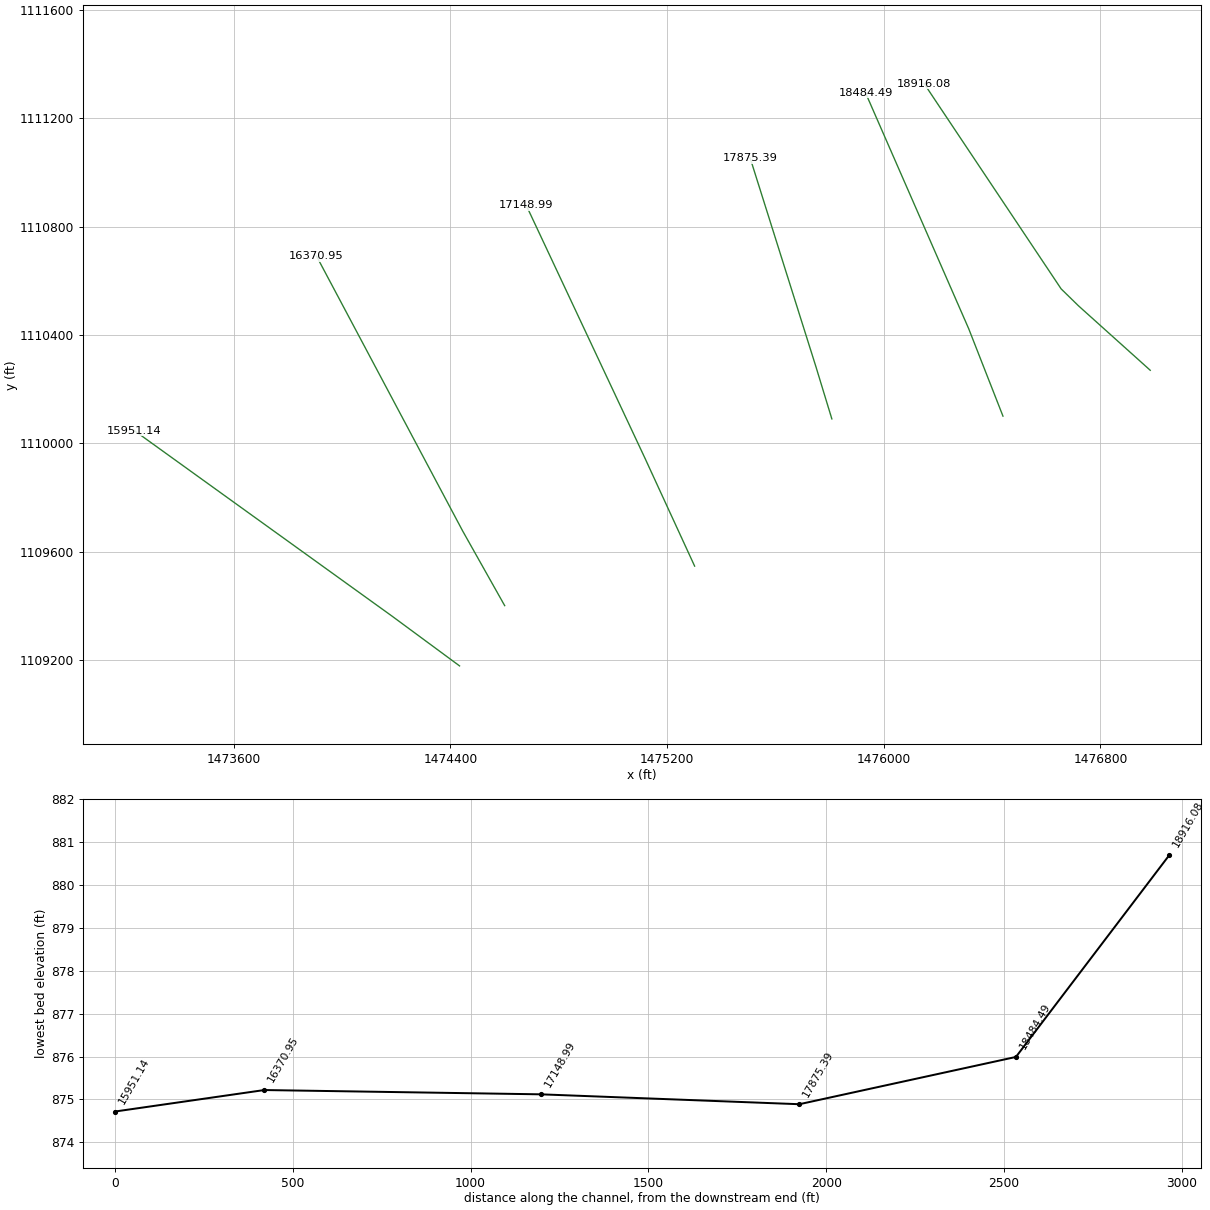
HEC-RAS study 12mile_Combined.prj: 12mile Creek Combined Model

--- 12mile_Combined.g07 (geometry) --- (continued)

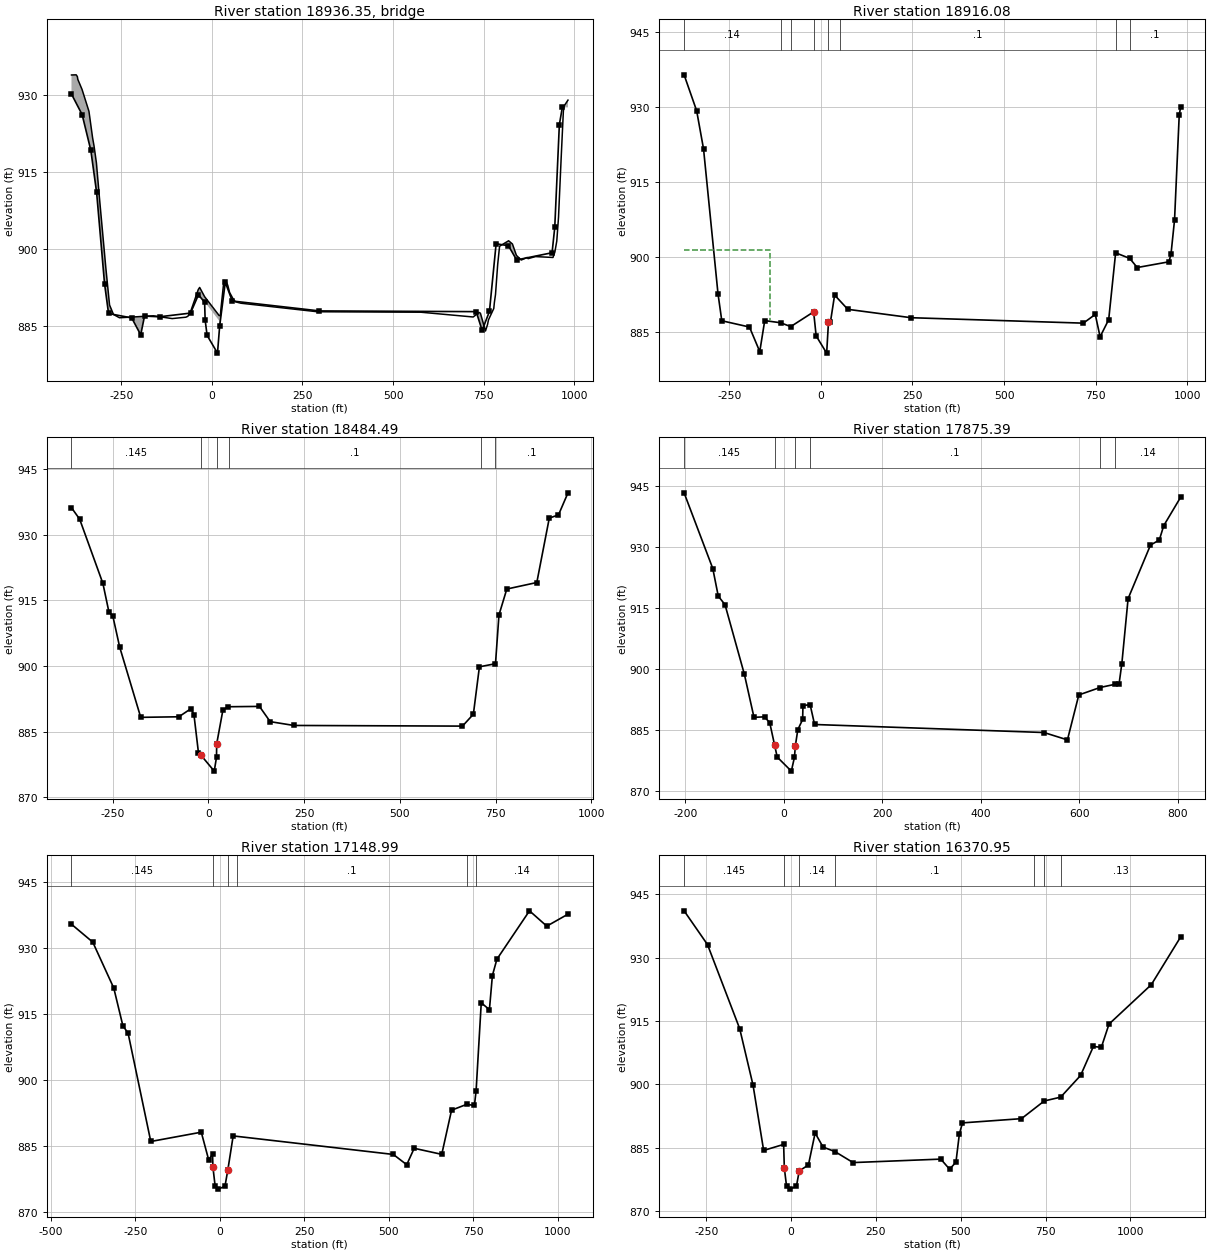
Type RM Length L Ch R = 3 ,18936.35,,,
BEGIN DESCRIPTION:
Unnamed Foot Bridge - TOR
END DESCRIPTION:
Bridge Culvert--1,0,-1,-1, 0
Deck Dist Width WeirC Skew NumUp NumDn MinLoCord MaxHiCord MaxSubmerge Is_Ogee
17.85,4,2.6,0, 60, 60, 886.97, , 0.95, 0, 0,0,,
 -387.46 -374.44 -371.21 -370.04 -358.38 -339.25 -329.24 -325.18 -318.64  -309.7
 -292.62 -282.38 -271.52 -255.01  -161.5 -109.54  -71.74  -66.17  -59.09  -37.51
  -33.68     -20      20   23.52   25.06   33.31   39.03    43.8   48.94   58.89
    64.9   80.15  291.35  576.96  721.22  737.37  741.25  755.29  760.92  763.58
  778.18  779.77  782.94  788.96  794.19   819.1  829.67  840.69  853.93  870.18
  872.93  893.13  941.58  946.81  952.08  956.88  964.09  970.28  972.44     983
   933.8  933.83  933.48  932.95     931  926.73  921.59  919.98  916.68  909.44
  896.26  889.05  887.21  886.57  886.95  886.41  886.68  886.86  887.69  892.06
  892.47  890.67  887.01  886.97   888.3  893.84  893.64   892.9   891.5   890.2
  889.68   889.4  887.74  887.65  886.72   887.6  887.46     884  885.25  886.17
  888.37  889.52  891.09  896.94  900.49  901.55  900.92   898.7   897.8   898.3
  898.07  898.47   898.3  899.36   901.5  906.14  917.52   926.8  927.79  928.91
                                                                                
                                                                                
          889.67  886.01
                                                                                
                                                                                
                                                                                
 -387.46 -374.44 -371.21 -370.04 -358.38 -339.25 -329.24 -325.18 -318.64  -309.7
 -292.62 -282.38 -271.52 -255.01  -161.5 -109.54  -71.74  -66.17  -59.09  -37.51
  -33.68     -20      20   23.52   25.06   33.31   39.03    43.8   48.94   58.89
    64.9   80.15  291.35  576.96  721.22  737.37  741.25  755.29  760.92  763.58
  778.18  779.77  782.94  788.96  794.19   819.1  829.67  840.69  853.93  870.18
  872.93  893.13  941.58  946.81  952.08  956.88  964.09  970.28  972.44     983
   933.8  933.83  933.48  932.95     931  926.73  921.59  919.98  916.68  909.44
  896.26  889.05  887.21  886.57  886.95  886.41  886.68  886.86  887.69  892.06
  892.47  890.67  887.01  886.97   888.3  893.84  893.64   892.9   891.5   890.2
  889.68   889.4  887.74  887.65  886.72   887.6  887.46     884  885.25  886.17
  888.37  889.52  891.09  896.94  900.49  901.55  900.92   898.7   897.8   898.3
  898.07  898.47   898.3  899.36   901.5  906.14  917.52   926.8  927.79  928.91
                                                                                
                                                                                
          889.67  886.01
                                                                                
                                                                                
                                                                                
BR Coef=-1 ,-1 , 0 ,, 0 ,,,0.8,0,1.2,0,
WSPro=,,,, 1 ,,,, 0 ,,,, 0 ,,,,-1 ,-1 ,-1 , 0 , 0 , 0 , 0 , 0
BC Design=,, 0 ,, 0 ,,,,,,
BC Use User HTab Curves=0
BC User HTab FreeFlow(D)= 0

Type RM Length L Ch R = 1 ,18916.08,435.3299,431.5941,310.5046
BEGIN DESCRIPTION:
Unnamed Foot Bridge - DS
END DESCRIPTION:
XS GIS Cut Line= 4
   1476984.08038   1110269.96358   1476720.07054   1110506.78117
   1476655.09383    1110570.0794   1476149.00951   1111327.25755
#Sta/Elev= 30
 -373.84  936.48 -339.56  929.28 -320.74  921.63 -281.28  892.62  -270.9  887.18
 -195.29  885.92 -167.17     881 -153.62  887.21 -110.45  886.78  -82.54  886.01
  -20.05  888.96  -13.12  884.14   15.54  880.69   20.54  886.92   25.82   886.9
   37.25  892.33   73.33  889.47  246.13  887.79  716.64   886.7  749.21  888.45
  762.39  883.96  785.88   887.4  804.84   900.8   843.3  899.68  863.88  897.85
   950.6     899  956.17  900.62  965.77  907.41  978.51  928.36  982.27  930.01
#Mann= 8 ,-1,0
 -373.84     .14       0 -110.45      .1       0  -82.54     .14       0
-20.0499    .035       020.54001     .14       053.10001      .1       0
804.8401     .06       0   843.3      .1       0
#XS Ineff= 2 , 0
            -140  901.41      40             889
Permanent Ineff=
       F       F
Bank Sta=-20.05,20.54
XS Rating Curve= 0 ,0
Exp/Cntr=0.5,0.3

Type RM Length L Ch R = 1 ,18484.49,607.0316,609.0988,541.4633
XS GIS Cut Line= 3
   1476440.24705   1110100.82776    1476313.8668   1110422.89403
   1475932.68701   1111293.28806
#Sta/Elev= 30
 -357.15  936.14  -335.8  933.52 -275.14  918.85 -259.55  912.38 -249.22  911.39
 -231.42  904.34 -176.39  888.27  -76.87   888.4  -45.39  890.24  -37.49  888.91
  -25.71  880.21  -20.04  879.72   15.54  875.99   21.43  879.16    21.9   882.2
   37.94  889.84    50.5  890.69  133.56  890.77  161.54  887.29  223.28  886.42
  663.58  886.27  692.01  888.98  707.79  899.81  749.75  900.52  758.84  911.65
   779.3  917.57  857.64  919.06   890.2  933.77  914.23   934.5  939.03  939.54
#Mann= 6 ,-1,0
 -357.15    .145       0  -20.04    .035       021.89999     .14       0
54.23999      .1       0713.0499     .06       0  749.75      .1       0
Bank Sta=-20.04,21.9
XS Rating Curve= 0 ,0
Exp/Cntr=0.3,0.1

Type RM Length L Ch R = 1 ,17875.39,720.055,726.4004,760.6047
BEGIN DESCRIPTION:
TWE_09X
END DESCRIPTION:
XS GIS Cut Line= 3
   1475808.34547   1110090.63583   1475749.22572   1110284.14534
   1475506.66306   1111052.75755
#Sta/Elev= 30
 -202.25  943.28 -143.99  924.68 -132.87   917.9 -119.15  915.79  -79.82  898.68
   -60.3  888.11  -38.94  888.23  -28.29  886.77  -18.48   881.3  -13.12  878.34
   15.54  874.89    21.9  878.31   23.67   881.1   28.68  885.07   38.49  887.58
   39.15     891   53.69  891.23   62.74  886.35  528.52  884.38  576.26  882.57
  599.35  893.61  642.52  895.44  672.95  896.23  681.13  896.34  686.73  901.29
  699.46  917.28  744.93  930.44  762.82  931.68  771.87  935.22  806.07  942.18
#Mann= 6 ,-1,0
 -202.25    .145       0  -18.48     .04       0   23.67     .14       0
   53.69      .1       0  642.52     .06       0  672.95     .14       0
Bank Sta=-18.48,23.67
XS Rating Curve= 0 ,0
Exp/Cntr=0.3,0.1

Type RM Length L Ch R = 1 ,17148.99,722.3938,778.0375,748.7724
XS GIS Cut Line= 3
   1475301.60236   1109547.77986   1475117.57415   1109947.08629
   1474680.07349    1110877.6437
#Sta/Elev= 30
 -438.39  935.45  -375.5  931.38 -313.37  920.92 -286.45  912.33 -271.05  910.64
 -203.96  885.97  -54.67  888.09  -32.86  881.81  -21.34  883.04  -20.25  880.16
  -13.66   875.8    -4.3  875.12   15.38  875.78   23.72  879.42    39.6  887.24
  513.15  883.02  552.79  880.68  574.83  884.42  656.32  883.04  685.31   893.1
   730.1  894.43  752.88  894.17  757.88  897.49  773.13  917.57  797.27  915.99
  806.06  923.77  819.41  927.49  915.72  938.51  966.91  935.02 1029.56  937.75
#Mann= 6 ,-1,0
 -438.39    .145       0  -20.25     .04       0   23.72     .14       0
51.54001      .1       0   730.1     .06       0  757.88     .14       0
Bank Sta=-20.25,23.72
XS Rating Curve= 0 ,0
Exp/Cntr=0.3,0.1

Type RM Length L Ch R = 1 ,16370.95,393.6167,419.8099,538.7955
BEGIN DESCRIPTION:
TWE_08X
END DESCRIPTION:
XS GIS Cut Line= 3
   1474600.21227   1109401.94619    1474445.3937   1109676.64633
    1473905.7664   1110690.14337
#Sta/Elev= 30
 -315.66  941.05 -246.65  933.06 -151.79  913.18  -112.4   899.8  -81.16  884.37
   -22.2   885.8  -20.25  880.26  -13.66   875.9    -4.3  875.22   15.38  875.88
   23.72  879.52   50.83  880.94   70.58   888.5   93.89  885.17  129.28  884.09
  182.44   881.5  441.01  882.32  467.03  879.93  485.68   881.6  495.86  888.32
  504.98  890.89   678.9  891.89   745.9  896.07  794.37  896.98  853.12  902.11
  890.76  908.96  914.26  908.76  936.88  914.26  1061.5  923.58 1147.87  934.85
#Mann= 7 ,-1,0
 -315.66    .145       0  -20.25     .04       0   23.72     .14       0
  129.28      .1       0714.9199     .06       0   745.9      .1       0
  794.37     .13       0
Bank Sta=-20.25,23.72
XS Rating Curve= 0 ,0
Exp/Cntr=0.3,0.1

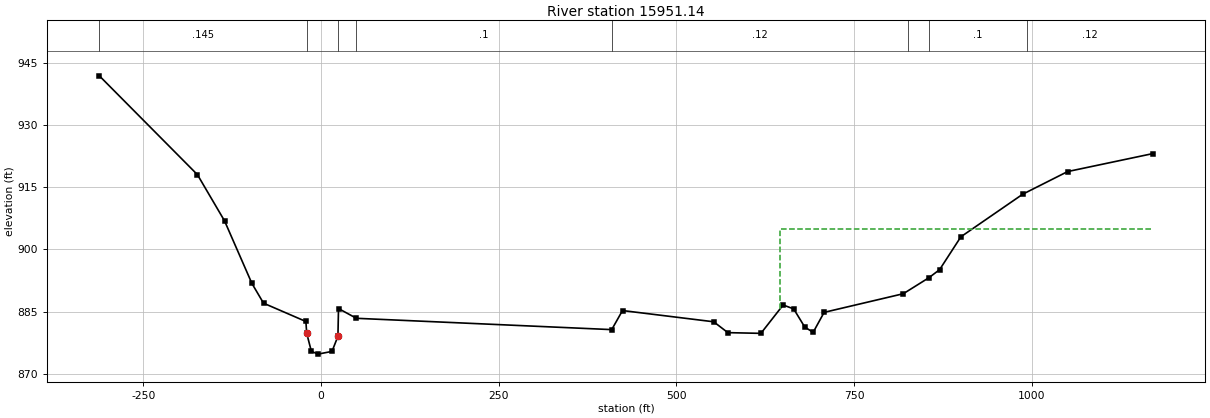
Type RM Length L Ch R = 1 ,15951.14,634.259,671.2197,597.0951
XS GIS Cut Line= 3
   1474433.54528   1109179.72375   1474183.54495   1109363.75197
   1473232.15387   1110047.78084
#Sta/Elev= 30
 -311.99  941.84 -173.96     918 -135.85  906.87  -97.35  891.78  -80.98  887.01
  -21.34  882.59  -20.25  879.76  -13.66   875.4    -4.3  874.72   15.38  875.38
   23.72  879.02   24.53  885.71   49.76  883.36  408.95  880.63  424.13  885.23
  552.48  882.52  572.39   879.9  618.87  879.73  650.14  886.57  664.98  885.63
  680.57  881.25  692.38  879.97  707.81  884.79  819.26  889.29  855.46  893.17
  870.33   895.1  900.27  903.02  987.27  913.29 1050.45  918.75 1170.21  923.08
#Mann= 8 ,-1,0
 -311.99    .145       0  -20.25     .04       0   23.72     .14       0
49.76001      .1       0  408.95     .12       0825.8301     .06       0
  855.46      .1       0992.8301     .12       0
#XS Ineff= 2 , 0
                          645.63          904.95
Permanent Ineff=
       F       F
Bank Sta=-20.25,23.72
XS Rating Curve= 0 ,0
Exp/Cntr=0.3,0.1