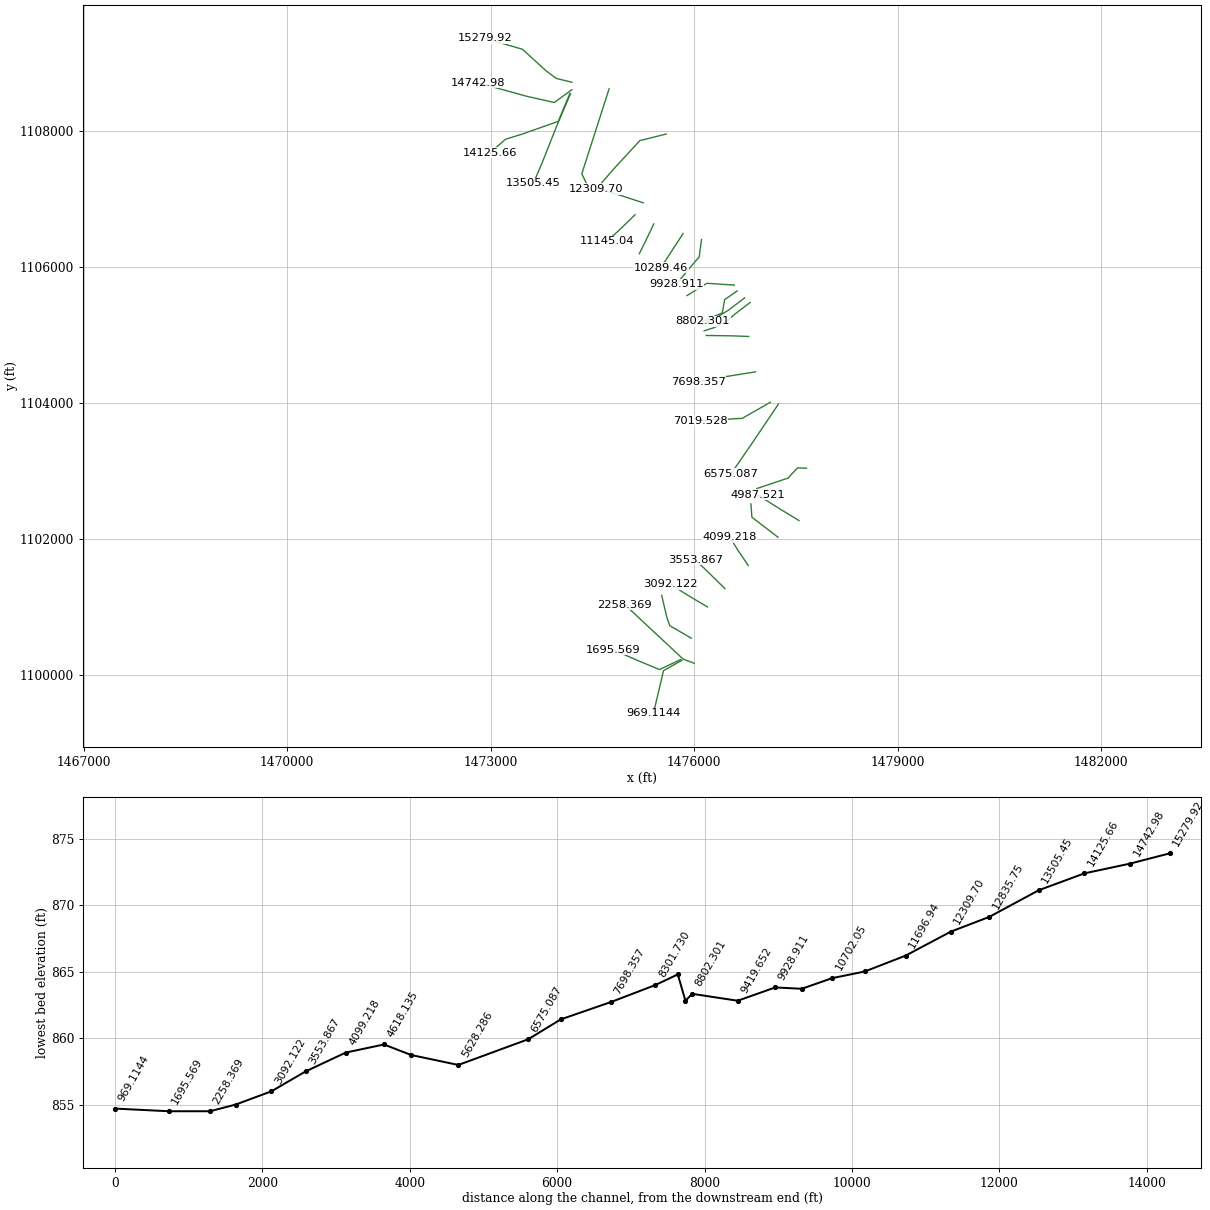
HEC-RAS study 12mile_Combined.prj: 12mile Creek Combined Model

--- 12mile_Combined.g07 (geometry) --- (continued)

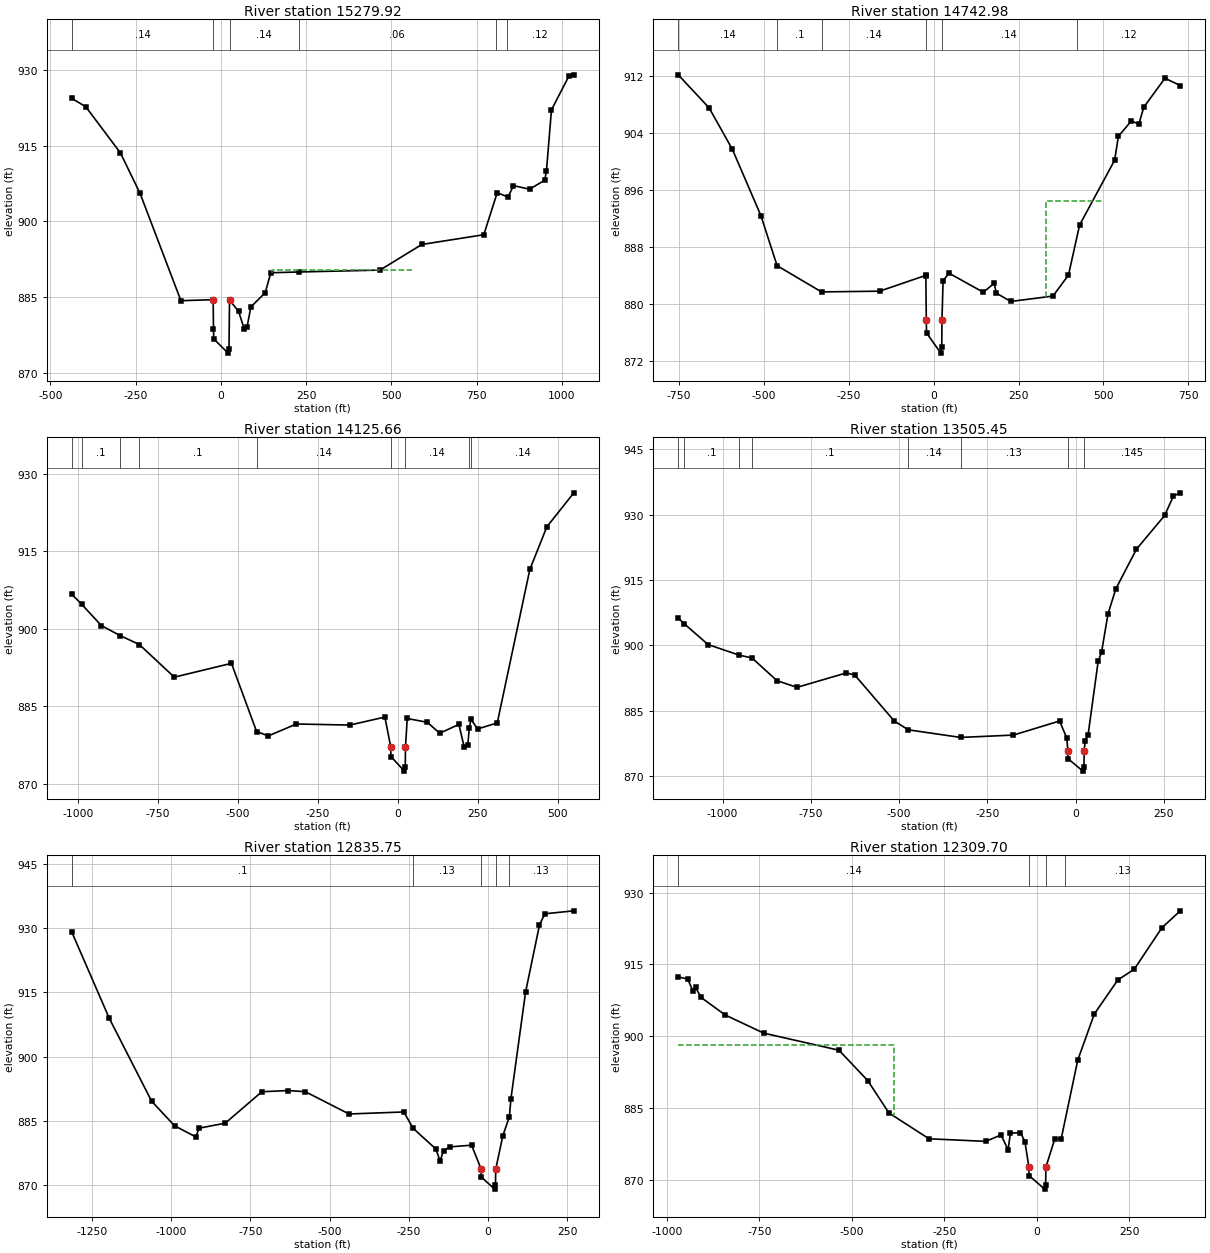
Type RM Length L Ch R = 1 ,15279.92,420.462,536.9451,576.9656
XS GIS Cut Line= 5
   1474198.43045   1108709.60466   1473967.45801   1108766.40125
   1473812.21424   1108881.88747   1473469.54199   1109194.26804
   1472914.82972    1109355.1916
#Sta/Elev= 30
 -437.52  924.32 -396.52  922.68 -294.79  913.53 -237.25  905.53 -117.42  884.28
   -22.8  884.48  -21.86  878.61  -21.21  876.73   20.95   873.9   23.65  874.78
   25.18  884.41   51.85  882.15   67.87  878.77   76.61  879.06   87.67  883.03
  130.12  885.89  146.08  889.81  227.78  889.96   466.7  890.34  589.28  895.41
  770.98  897.34  810.33  905.66  842.05  904.79  858.09  907.06  905.13  906.35
  949.77  908.13  954.83  910.04  969.44  922.05 1020.32   928.7 1035.09  928.99
#Mann= 6 ,-1,0
 -437.52     .14       0-22.7999     .04       025.17999     .14       0
  227.78     .06       0805.4398     .06       0837.8198     .12       0
#XS Ineff= 1 ,-1
  149.42  560.36  890.38
Permanent Ineff=
       F
Bank Sta=-22.8,25.18
XS Rating Curve= 0 ,0
Exp/Cntr=0.3,0.1

Type RM Length L Ch R = 1 ,14742.98,439.5438,617.3231,671.8304
XS GIS Cut Line= 4
   1474197.43373   1108599.86122    1473937.0164   1108412.36089
   1473523.82119   1108506.11089   1472815.48622    1108700.5561
#Sta/Elev= 30
 -752.65  912.13 -661.71   907.5 -593.17  901.69 -509.03  892.39 -461.38  885.38
 -330.57  881.71 -159.52  881.81  -23.77  884.02  -23.14   883.9  -21.86  877.84
  -21.21  875.96   20.95  873.13   23.65  874.01   24.31  877.73   27.61  883.26
   44.79  884.34  146.11  881.66  177.92  882.91  184.68  881.52  227.26  880.37
  351.37  881.13  397.03  884.07  429.71  891.08  533.09  900.17  544.08  903.52
  582.27  905.66  604.36  905.23  619.06  907.61  681.23  911.65  726.48  910.63
#Mann= 6 ,-1,0
 -752.65     .14       0 -461.38      .1       0 -330.57     .14       0
-21.8599     .04       0   24.31     .14       0420.7001     .12       0
#XS Ineff= 1 ,-1
  331.03499.7999894.4954
Permanent Ineff=
       F
Bank Sta=-21.86,24.31
XS Rating Curve= 0 ,0
Exp/Cntr=0.3,0.1

Type RM Length L Ch R = 1 ,14125.66,290.9466,620.2021,640.5469
BEGIN DESCRIPTION:
TWE_07X
END DESCRIPTION:
XS GIS Cut Line= 5
   1474168.05118   1108545.20472   1473996.54724   1108134.82119
   1473453.86155   1107944.94259   1473218.65682   1107872.66601
   1472989.09777   1107672.77592
#Sta/Elev= 30
-1019.34   906.7 -988.89  904.79 -926.67  900.61 -867.62  898.67 -808.13  896.95
 -698.68  890.62 -519.92   893.3 -441.33  880.08 -404.44  879.23 -317.04  881.54
 -150.11  881.33  -40.11  882.88  -21.86  877.11  -21.21  875.23   20.95   872.4
   23.65  873.28   24.31     877   29.74  882.61   92.94  881.86  131.07  879.75
  191.41  881.45  207.61  877.12  219.32  877.46  223.69   880.7  229.11  882.44
  249.96  880.58  311.32  881.75  413.26  911.52  466.42  919.77  550.83  926.36
#Mann= 9 ,-1,0
-1019.34     .14       0 -988.89      .1       0 -867.62     .14       0
 -808.13      .1       0 -441.33     .14       0-21.8599     .04       0
   24.31     .14       0  223.69      .1       0  229.11     .14       0
Bank Sta=-21.86,24.31
XS Rating Curve= 0 ,0
Exp/Cntr=0.3,0.1

Type RM Length L Ch R = 1 ,13505.45,593.0652,669.6997,674.7907
XS GIS Cut Line= 4
   1474176.62631   1108541.52953   1473978.17192   1108077.24508
   1473752.98819   1107513.05348    1473631.4603   1107228.33104
#Sta/Elev= 30
-1125.39  906.28-1108.38  904.98-1041.04   900.2 -952.89  897.77 -916.62  897.12
 -845.65   891.9 -789.02  890.37 -649.54  893.68 -625.53  893.21 -513.71  882.65
 -474.13  880.62 -325.87  878.87 -176.06  879.41  -45.41  882.64  -24.94  878.73
  -21.86  875.84  -21.21  873.96   20.95  871.13   23.65  872.01   24.31  875.73
   26.92  878.14   35.25  879.38   63.87  896.32   73.48  898.43   91.78  907.25
     114     913  172.46  922.11  252.23  929.84  277.18  934.31  296.57  935.04
#Mann= 8 ,-1,0
-1125.39     .14       0-1108.38      .1       0 -952.89     .14       0
 -916.62      .1       0 -474.13     .14       0 -325.87     .13       0
-21.8598     .04       024.31006    .145       0
Bank Sta=-21.86,24.31
XS Rating Curve= 0 ,0
Exp/Cntr=0.3,0.1

Type RM Length L Ch R = 1 ,12835.75,550.2411,526.0508,447.1309
XS GIS Cut Line= 3
   1474746.04593   1108613.75033   1474343.26739    1107363.7477
   1474464.79528    1107120.6916
#Sta/Elev= 30
-1314.03  929.05-1195.56  908.92-1061.89  889.61 -989.31  883.88 -922.62  881.31
 -911.92  883.34 -829.43   884.5 -714.09  891.82 -631.73   892.1 -576.79  891.84
 -438.68  886.64 -265.82  887.11 -235.95  883.27 -164.48  878.47 -151.31  875.68
 -140.45   878.1 -119.24  878.98  -51.87  879.37  -21.86  873.84  -21.21  871.96
   20.95  869.13   23.65  870.01   24.31  873.73   46.74  881.55   67.51  886.01
   72.31  890.16  118.53  915.01  162.49  930.67  179.15  933.29  271.01  933.98
#Mann= 5 ,-1,0
-1314.03      .1       0 -235.95     .13       0-21.8598     .04       0
24.31006     .13       064.90002     .13       0
#XS Ineff= 1 ,-1
-1127.15 -703.94  889.96
Permanent Ineff=
       F
Bank Sta=-21.86,24.31
XS Rating Curve= 0 ,0
Exp/Cntr=0.3,0.1

Type RM Length L Ch R = 1 ,12309.70,680.5234,612.7648,355.1502
XS GIS Cut Line= 4
   1475587.19324    1107949.2523   1475199.17192   1107852.89797
   1474813.75427   1107436.23064    1474558.5456   1107141.95899
#Sta/Elev= 30
  -969.3  912.36 -943.64  911.92 -929.06  909.32 -922.59  910.17 -907.54  908.07
 -842.62  904.41 -738.26  900.61 -534.83  897.04 -457.14  890.69 -399.72  883.92
 -291.47  878.53 -138.17  877.99  -97.03  879.33  -77.77  876.24  -71.65  879.68
   -44.3  879.84  -32.25  877.89  -21.86  872.72  -21.21  870.84   20.95  868.01
   23.65  868.89   24.31  872.61    48.2  878.48   65.78  878.56  110.41  894.97
  155.34  904.63  218.87  911.73  263.11  913.96  337.86  922.64  387.61  926.17
#Mann= 4 ,-1,0
  -969.3     .14       0-21.8599     .04       0   24.31     .14       0
77.28998     .13       0
#XS Ineff= 2 , 0
         -386.61  898.07
Permanent Ineff=
       F       F
Bank Sta=-21.86,24.31
XS Rating Curve= 0 ,0
Exp/Cntr=0.3,0.1

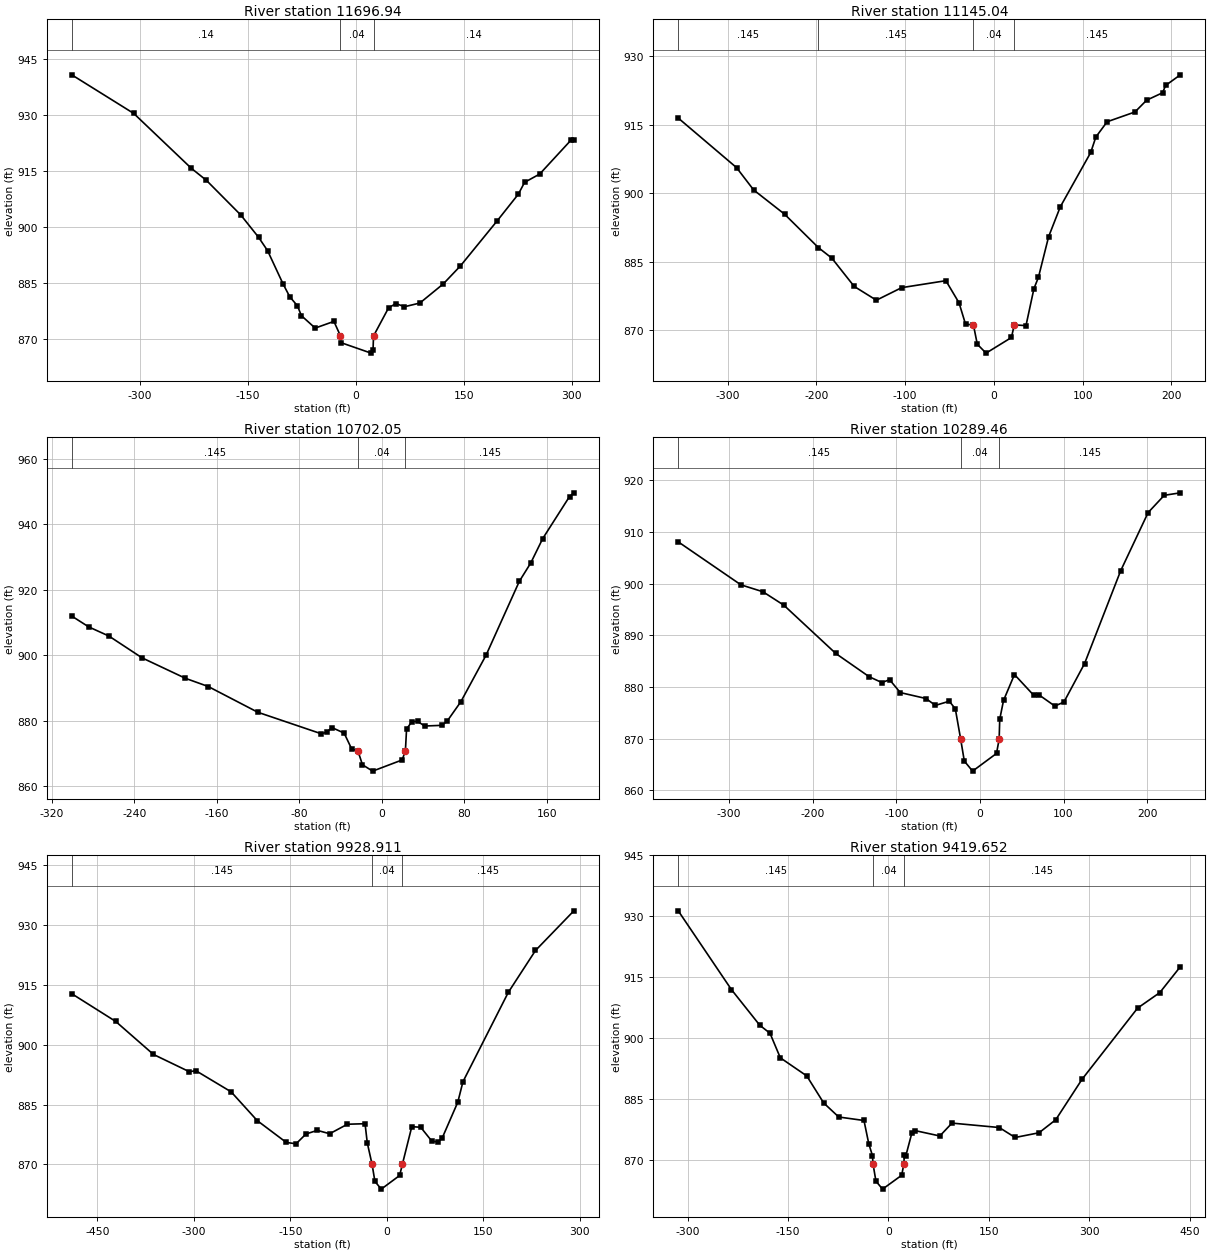
Type RM Length L Ch R = 1 ,11696.94,448.4701,551.9048,606.639
XS GIS Cut Line= 3
   1475248.65092   1106938.83366   1474876.25459   1107061.22999
   1474581.98294   1107144.56332
#Sta/Elev= 30
 -395.09  940.77 -308.91  930.42 -228.87  915.72 -207.97   912.5 -160.09   903.2
  -135.5  897.26 -122.93  893.66 -101.57  884.81  -92.14  881.32  -81.42  878.88
  -75.96  876.25  -56.78  872.92  -30.73  874.71  -21.86  870.92  -21.21  869.04
   20.95  866.21   23.65  867.09   24.31  870.81   45.16  878.31   55.26   879.5
   67.35  878.64   88.71  879.63  121.31  884.76  145.07  889.57  196.35  901.69
  225.55  908.79  234.29  911.97  255.29  914.19  299.04  923.33  302.74   923.4
#Mann= 3 ,-1,0
 -395.09     .14       0  -21.86     .04       0   24.31     .14       0
Bank Sta=-21.86,24.31
XS Rating Curve= 0 ,0
Exp/Cntr=0.3,0.1

Type RM Length L Ch R = 1 ,11145.04,420.047,442.9843,454.1935
XS GIS Cut Line= 3
   1475128.85892   1106764.35433    1474878.8586   1106522.16601
   1474717.39993   1106376.33235
#Sta/Elev= 30
 -355.56  916.46  -289.9  905.62 -270.61  900.73  -235.8  895.43  -197.6   888.1
 -182.58  885.82 -157.34  879.62 -132.33   876.6  -103.8  879.35  -54.03  880.87
  -39.23  876.03  -31.88  871.35     -23   871.2  -18.65  866.97   -8.75  865.02
   19.84  868.44      23   871.2   36.21  871.04   45.18  879.14   50.25  881.61
   61.71   890.5   74.88  897.04  109.16  908.93  114.92  912.31  127.64  915.65
  158.98  917.79  172.15  920.37  190.05  921.99  193.56   923.6  210.08  925.92
#Mann= 4 ,-1,0
 -355.56    .145       0  -197.6    .145       0     -23     .04       0
      23    .145       0
Bank Sta=-23,23
XS Rating Curve= 0 ,0
Exp/Cntr=0.3,0.1

Type RM Length L Ch R = 1 ,10702.05,418.395,412.593,395.6147
XS GIS Cut Line= 3
   1475404.90125   1106628.93734   1475274.69259   1106358.10335
   1475191.35925   1106191.43635
#Sta/Elev= 30
 -300.51  911.96 -284.14  908.66 -264.43  905.84 -232.31  899.17 -190.23  892.91
 -168.18  890.41 -120.17  882.54  -58.45  875.94  -53.16  876.46  -48.34  877.86
  -36.43  876.16  -28.98  871.23     -23   870.7  -18.65  866.47   -8.75  864.52
   19.84  867.94      23   870.7   24.14  877.42   29.43   879.7   34.89  879.74
   41.63  878.32   58.29  878.53   63.48  879.81   76.76  885.75  101.27  900.03
  133.52  922.62  144.56  928.21  156.17  935.68  182.14  948.53  186.34  949.67
#Mann= 3 ,-1,0
 -300.51    .145       0     -23     .04       0      23    .145       0
Bank Sta=-23,23
XS Rating Curve= 0 ,0
Exp/Cntr=0.3,0.1

Type RM Length L Ch R = 1 ,10289.46,372.7355,360.5543,348.1365
XS GIS Cut Line= 3
    1475837.1939   1106488.31201   1475636.67257   1106181.01969
   1475509.06824   1105985.70669
#Sta/Elev= 30
 -360.65  908.06 -285.76  899.75 -259.41  898.41  -234.4  895.81 -172.29  886.47
 -132.42  881.98 -117.23  880.85 -107.98   881.4  -95.18  878.91  -64.44  877.76
  -53.23  876.43  -36.62  877.24   -29.4  875.77     -23   869.9  -18.65  865.67
   -8.75  863.72   19.84  867.14      23   869.9    23.7  873.75   28.24  877.39
    41.3   882.4   64.25   878.4   70.43  878.49   89.54  876.31  100.41  877.07
  125.08  884.51  168.17  902.43  201.09  913.72  220.38  917.06  239.58  917.54
#Mann= 3 ,-1,0
 -360.65    .145       0     -23     .04       0      23    .145       0
Bank Sta=-23,23
XS Rating Curve= 0 ,0
Exp/Cntr=0.3,0.1

Type RM Length L Ch R = 1 ,9928.911,521.736,509.2589,310.9061
BEGIN DESCRIPTION:
TWE_06X
END DESCRIPTION:
XS GIS Cut Line= 4
   1476108.02756   1106399.77034   1476074.17356   1106144.56135
   1475921.69652   1105968.92454   1475738.23524   1105743.51903
#Sta/Elev= 30
 -489.97  912.78  -421.6  905.83 -363.01  897.57 -307.21  893.24 -296.98  893.49
  -242.2   888.2 -201.61  880.99 -156.44  875.52 -141.23  875.18 -125.75  877.64
 -108.24  878.54  -88.95   877.7  -61.41  880.08  -33.95  880.21   -30.5  875.41
     -23     870  -18.65  865.77   -8.75  863.82   19.84  867.24      24     870
   38.72  879.47   52.57  879.32   69.85  875.85   79.73  875.62   85.96  876.61
  110.23   885.6  118.29  890.74  188.77  913.12  231.04  923.61  290.69  933.55
#Mann= 3 ,-1,0
 -489.97    .145       0     -23     .04       023.99997    .145       0
Bank Sta=-23,24
XS Rating Curve= 0 ,0
Exp/Cntr=0.3,0.1

Type RM Length L Ch R = 1 ,9419.652,334.9754,617.3513,531.2918
XS GIS Cut Line= 4
   1476592.40354   1105730.49803   1476274.69455   1105751.33136
   1476186.15289    1105756.5397   1475894.48556   1105576.85203
#Sta/Elev= 30
 -313.85  931.31 -234.44  911.93 -192.14  903.16 -176.84  901.18 -161.43  895.14
 -121.94  890.68  -96.69  884.03   -74.2  880.57  -36.52  879.71  -29.34  873.98
  -23.89  871.08     -23     869  -18.65  864.77   -8.75  862.82   19.84  866.24
      23     869   23.72  871.13   25.88  870.96   35.08   876.7   39.65  877.23
   76.74   875.9    94.9  879.07  165.48  877.98  189.19  875.53  224.84  876.69
   249.8  879.89  289.16  889.87  372.04  907.37  405.22  911.19  435.81  917.55
#Mann= 3 ,-1,0
 -313.85    .145       0     -23     .04       0      23    .145       0
Bank Sta=-23,23
XS Rating Curve= 0 ,0
Exp/Cntr=0.3,0.1

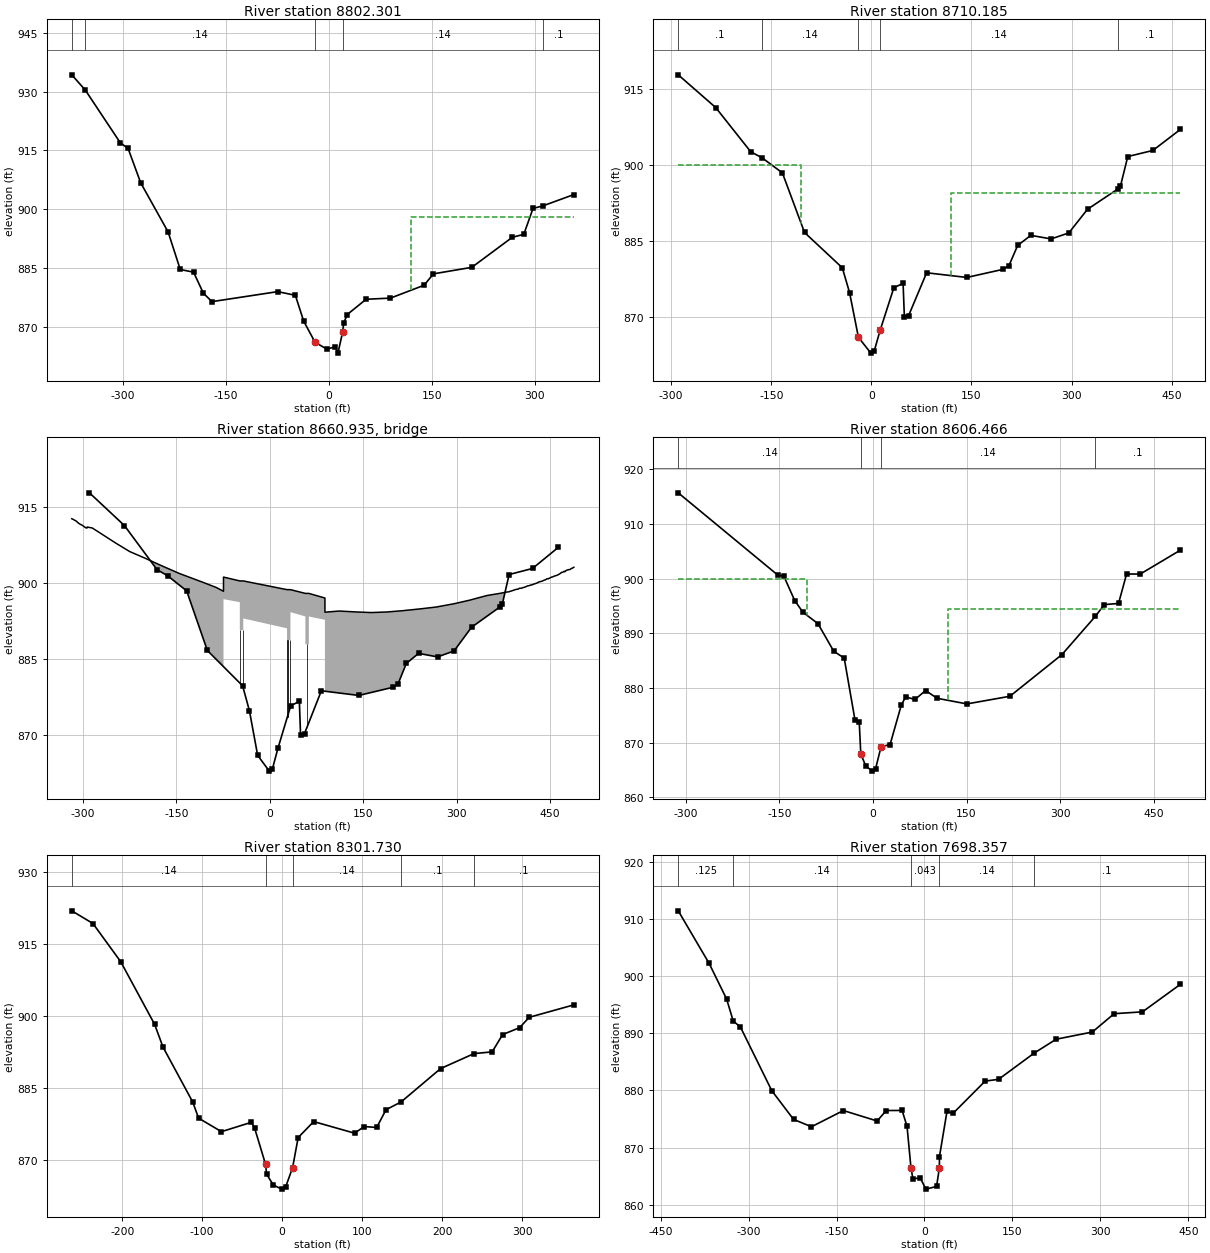
Type RM Length L Ch R = 1 ,8802.301,132.8714,92.11585,37.6268
BEGIN DESCRIPTION:
TWE_05USX
END DESCRIPTION:
XS GIS Cut Line= 5
   1476634.07054   1105644.56037   1476450.24344    1105517.7185
   1476422.40682   1105368.48458   1476413.12828   1105321.31759
   1476129.35171   1105199.14665
#Sta/Elev= 30
 -374.95  934.25 -355.29  930.38 -303.99  916.88 -292.87  915.53 -274.47  906.74
 -234.48  894.23 -216.76  884.65 -197.34  883.97 -182.99  878.59 -170.49  876.46
  -74.54  879.01  -48.88  878.07  -36.72  871.48   -20.2  866.11   -3.21  864.38
    9.21  864.93   13.22  863.34   19.92  868.61   21.69  871.04   26.82  873.18
   54.25  877.06   89.85  877.36  138.87  880.64  152.42  883.54  208.43   885.2
  267.47  892.85  284.23  893.61  297.72  900.21  311.91  900.85  357.23  903.74
#Mann= 5 ,-1,0
 -374.95      .1       0 -355.29     .14       0   -20.2     .04       0
19.92001     .14       0  311.91      .1       0
#XS Ineff= 2 , 0
                          119.99          897.95
Permanent Ineff=
       F       F
Bank Sta=-20.2,19.92
XS Rating Curve= 0 ,0
Exp/Cntr=0.5,0.3

Type RM Length L Ch R = 1 ,8710.185,103.9837,103.7191,140.4866
BEGIN DESCRIPTION:
Allgoud Bridge Dr (TWE_05) - US
END DESCRIPTION:
XS GIS Cut Line= 5
   1476744.19521   1105543.17126   1476503.45604   1105360.07382
   1476427.71129   1105314.85466   1476313.57743   1105244.79035
   1476105.04954   1105153.24147
#Sta/Elev= 30
 -289.38  917.72 -233.19  911.26 -180.86  902.56 -163.67  901.34 -133.34  898.38
 -100.14  886.62   -43.5  879.65  -32.56  874.71  -19.38  865.93    -.69  862.82
    4.23  863.21   13.07  867.29   33.71  875.72   47.55  876.58   49.46  869.97
   55.82  870.22   82.83  878.67  142.94  877.75  197.15  879.34  206.04  880.05
  219.26  884.07  238.97  886.05  269.33  885.35  295.87  886.53   323.9   891.2
  369.95  895.25  373.17  895.72  384.22   901.6  421.82   902.8  462.95  906.94
#Mann= 5 ,-1,0
 -289.38      .1       0 -163.67     .14       0  -19.38     .04       0
13.07001     .14       0  369.95      .1       0
#XS Ineff= 2 , 0
            -105     900     120           894.5
Permanent Ineff=
       F       F
Bank Sta=-19.38,13.07
XS Rating Curve= 0 ,0
Exp/Cntr=0.5,0.3

Type RM Length L Ch R = 3 ,8660.935,,,
BEGIN DESCRIPTION:
Allgoud Bridge Dr (TWE_05) - TOR
END DESCRIPTION:
Bridge Culvert--1,0,-1,-1, 0
Deck Dist Width WeirC Skew NumUp NumDn MinLoCord MaxHiCord MaxSubmerge Is_Ogee
32.5,33.5,2.6,0, 155, 155, 894.1, , 0.95, 0, 0,0,,
 -317.73 -317.01 -314.75 -314.45 -314.13 -313.49 -310.25 -310.06 -308.47 -307.35
 -305.96 -304.19 -301.57 -299.89  -298.9  -296.3 -295.59 -293.98 -293.33 -293.05
 -284.75 -247.07 -224.71 -200.78  -176.3 -145.47 -116.36 -107.51  -85.99  -74.22
  -74.22     -48     -48   -42.5   -42.5   27.75   27.75   33.25   33.25   57.25
   57.25   62.75   62.75    88.6    88.6  111.38  114.27  137.44  162.84  187.52
  212.58  236.64  240.99  267.09  295.79  320.67  348.52  370.95  380.18  383.46
  383.57  383.89  385.27  387.33  388.08  388.89  389.22  389.72  390.34  390.85
  392.17  392.42  392.94  395.15  396.26  396.94  398.64  399.29  400.57  400.88
  403.96  404.29  406.06   407.9  408.36  410.13  412.42  412.45  412.74  413.81
  415.36  416.45  418.57  419.09  420.05  421.33  423.04  424.63   424.9  425.86
   428.4  428.71  431.05  431.52  431.91  432.54  433.07  436.75  436.93  436.94
  440.25  440.69   440.7  442.63  444.48  444.62  444.68  445.22  446.86  448.07
   449.1  451.98  452.31  452.89  454.27   456.1  456.58  458.07  458.26  460.18
  460.44   463.6  464.28  465.04  467.87  468.27  468.58  469.53   470.8  472.52
  473.67   474.6   474.9  476.57  477.59   479.3  479.78   481.7   483.5  484.23
  485.32  485.68  487.41  487.81   488.1
  912.61  912.57  912.44  912.43  912.38  912.33  912.12  912.11  911.88  911.79
  911.65  911.52  911.37  911.23  911.16  910.91  910.84  910.78  910.77  910.97
  910.78   907.8  906.13  904.86  903.49  901.83   900.5  900.08  899.06   898.3
   901.1  900.34  900.34  900.34  900.34  898.62  898.62  898.62  898.62  897.88
  897.88  897.88  897.88  896.97  894.17   894.4  894.38  894.23   894.1  894.21
  894.46  894.76  894.82  895.19  895.84  896.54  897.46  897.92  898.14  898.19
  898.19   898.2  898.26  898.35  898.38  898.42  898.44  898.45  898.46  898.47
  898.54  898.53  898.58  898.65  898.67  898.71  898.72  898.74   898.9   898.9
  898.89  898.89  899.03  899.04  899.09  899.14  899.28  899.28   899.3  899.36
  899.39  899.41  899.54  899.55  899.53  899.58  899.69  899.74  899.76  899.79
  899.91  899.92  900.07   900.1   900.1  900.14  900.18  900.27  900.28  900.28
  900.48  900.51  900.51  900.56  900.74  900.74  900.75  900.76  900.74  900.85
  900.89  901.08  901.09  901.12  901.13  901.25  901.29  901.34  901.36  901.42
  901.42   901.6  901.67   901.7  901.97  902.01  902.04  902.03   902.1  902.23
  902.15  902.28  902.33  902.44  902.49  902.57  902.55  902.58  902.73  902.81
  902.83  902.86  903.01  903.02  903.04
                                                                                
                                                                                
                                                                          896.75
  896.75  896.14  890.64  890.64  892.94  890.99  888.69  888.69  894.19  893.33
  887.83  887.83  893.33  892.67  892.67
                                                                                
                                                                                
                                                                                
                                                                                
                                                                                
                                                                                
                                                                                
                                                                                
                                                                                
                                                                                
                                        
 -317.73 -317.01 -314.75 -314.45 -314.13 -313.49 -310.25 -310.06 -308.47 -307.35
 -305.96 -304.19 -301.57 -299.89  -298.9  -296.3 -295.59 -293.98 -293.33 -293.05
 -284.75 -247.07 -224.71 -200.78  -176.3 -145.47 -116.36 -107.51  -85.99  -74.22
  -74.22     -48     -48   -42.5   -42.5   27.75   27.75   33.25   33.25   57.25
   57.25   62.75   62.75    88.6    88.6  111.38  114.27  137.44  162.84  187.52
  212.58  236.64  240.99  267.09  295.79  320.67  348.52  370.95  380.18  383.46
  383.57  383.89  385.27  387.33  388.08  388.89  389.22  389.72  390.34  390.85
  392.17  392.42  392.94  395.15  396.26  396.94  398.64  399.29  400.57  400.88
  403.96  404.29  406.06   407.9  408.36  410.13  412.42  412.45  412.74  413.81
  415.36  416.45  418.57  419.09  420.05  421.33  423.04  424.63   424.9  425.86
   428.4  428.71  431.05  431.52  431.91  432.54  433.07  436.75  436.93  436.94
  440.25  440.69   440.7  442.63  444.48  444.62  444.68  445.22  446.86  448.07
   449.1  451.98  452.31  452.89  454.27   456.1  456.58  458.07  458.26  460.18
  460.44   463.6  464.28  465.04  467.87  468.27  468.58  469.53   470.8  472.52
  473.67   474.6   474.9  476.57  477.59   479.3  479.78   481.7   483.5  484.23
  485.32  485.68  487.41  487.81   488.1
  912.61  912.57  912.44  912.43  912.38  912.33  912.12  912.11  911.88  911.79
  911.65  911.52  911.37  911.23  911.16  910.91  910.84  910.78  910.77  910.97
  910.78   907.8  906.13  904.86  903.49  901.83   900.5  900.08  899.06   898.3
   901.1  900.34  900.34  900.34  900.34  898.62  898.62  898.62  898.62  897.88
  897.88  897.88  897.88  896.97  894.17   894.4  894.38  894.23   894.1  894.21
  894.46  894.76  894.82  895.19  895.84  896.54  897.46  897.92  898.14  898.19
  898.19   898.2  898.26  898.35  898.38  898.42  898.44  898.45  898.46  898.47
  898.54  898.53  898.58  898.65  898.67  898.71  898.72  898.74   898.9   898.9
  898.89  898.89  899.03  899.04  899.09  899.14  899.28  899.28   899.3  899.36
  899.39  899.41  899.54  899.55  899.53  899.58  899.69  899.74  899.76  899.79
  899.91  899.92  900.07   900.1   900.1  900.14  900.18  900.27  900.28  900.28
  900.48  900.51  900.51  900.56  900.74  900.74  900.75  900.76  900.74  900.85
  900.89  901.08  901.09  901.12  901.13  901.25  901.29  901.34  901.36  901.42
  901.42   901.6  901.67   901.7  901.97  902.01  902.04  902.03   902.1  902.23
  902.15  902.28  902.33  902.44  902.49  902.57  902.55  902.58  902.73  902.81
  902.83  902.86  903.01  903.02  903.04
                                                                                
                                                                                
                                                                          896.75
  896.75  896.14  890.64  890.64  892.94  890.99  888.69  888.69  894.19  893.33
  887.83  887.83  893.33  892.67  892.67
                                                                                
                                                                                
                                                                                
                                                                                
                                                                                
                                                                                
                                                                                
                                                                                
                                                                                
                                                                                
                                        
Pier Skew, UpSta & Num, DnSta & Num=  ,-47.5, 2 ,-47.5, 2 , 0 , 0 , 0 ,,
       1       1
     860     897
       1       1
     860     897
Pier Skew, UpSta & Num, DnSta & Num=  ,-43, 2 ,-43, 2 , 0 , 0 , 0 ,,
       1       1
     860     897
       1       1
     860     897
Pier Skew, UpSta & Num, DnSta & Num=  ,28.5, 2 ,28.5, 2 , 0 , 0 , 0 ,,
       1       1
     860     897
       1       1
     860     897
Pier Skew, UpSta & Num, DnSta & Num=  ,32.5, 2 ,32.5, 2 , 0 , 0 , 0 ,,
       1       1
     860     897
       1       1
     860     897
Pier Skew, UpSta & Num, DnSta & Num=  ,60, 2 ,60, 2 , 0 , 0 , 0 ,,
       1       1
     860     897
       1       1
     860     897
Abutment Skew #Up #Dn= , 2 , 2
  -74.22  -47.07
  896.75  880.04
  -74.22  -47.07
  896.75  880.04
Abutment Skew #Up #Dn= , 2 , 2
   60.54    88.6
  871.18  892.67
   60.54    88.6
  871.18  892.67
BR Coef=-1 ,-1 , 0 ,, 0 ,,,0.8,0,1.2,0,
WSPro=,,,, 1 ,,,, 0 ,,,, 0 ,,,,-1 ,-1 ,-1 , 0 , 0 , 0 , 0 , 0
BC Design=,, 0 ,, 0 ,,,,,,
BC Use User HTab Curves=0
BC User HTab FreeFlow(D)= 0

Type RM Length L Ch R = 1 ,8606.466,318.6339,304.7363,258.2462
BEGIN DESCRIPTION:
Allgoud Bridge Dr (TWE_05) - DS
END DESCRIPTION:
XS GIS Cut Line= 6
   1476824.72441   1105475.35728   1476573.81299   1105283.78314
   1476516.17126   1105228.68438   1476452.59547   1105184.60531
   1476302.65978   1105108.77625    1476147.4334   1105058.30184
#Sta/Elev= 30
 -311.75  915.69 -151.84   900.6 -142.69  900.46 -125.24     896 -112.15  893.86
  -88.01  891.77  -62.74  886.73  -45.93  885.46  -28.66  874.13  -21.89  873.77
  -19.38  867.91  -11.13  865.68    -.69   864.8    4.23  865.19   13.07  869.27
   27.49  869.65   45.46  876.87   52.48  878.38   67.32   877.9   84.41  879.54
  102.79  878.12  150.59  877.09  219.44  878.49  302.84  886.12  356.28  893.11
  370.56  895.25  393.39  895.46  406.25  900.84  428.21  900.84  492.32   905.2
#Mann= 4 ,-1,0
 -311.75     .14       0  -19.38     .04       013.07001     .14       0
  356.28      .1       0
#XS Ineff= 2 , 0
            -105     900     120           894.5
Permanent Ineff=
       F       F
Bank Sta=-19.38,13.07
XS Rating Curve= 0 ,0
Exp/Cntr=0.5,0.3

Type RM Length L Ch R = 1 ,8301.730,570.8895,603.3726,607.1384
XS GIS Cut Line= 3
   1476804.64403    1104975.9393   1476542.92454   1104985.05381
   1476177.03839   1104990.26214
#Sta/Elev= 30
 -263.05  921.97 -236.58  919.33 -201.83  911.37 -159.44  898.32 -148.97  893.59
 -111.79  882.14 -104.45  878.78  -75.86  875.97  -38.45  877.92   -34.4  876.71
  -20.72  869.16  -19.38  867.11  -11.13  864.88    -.69     864    4.23  864.39
   13.07  868.47   20.02  874.74   39.45  878.07   90.63  875.65  102.57  877.03
  118.23  876.85   129.9  880.54   148.8  882.17  198.14  889.11  239.92  892.23
  262.61  892.59  275.68  896.19  296.91  897.63  308.92  899.79  364.75  902.38
#Mann= 5 ,-1,0
 -263.05     .14       0  -20.72     .04       013.07001     .14       0
   148.8      .1       0  239.92      .1       0
Bank Sta=-20.72,13.07
XS Rating Curve= 0 ,0
Exp/Cntr=0.3,0.1

Type RM Length L Ch R = 1 ,7698.357,622.8832,678.829,623.3411
XS GIS Cut Line= 3
   1476904.47014   1104455.75591   1476487.80282   1104389.78346
    1476060.7185   1104311.65846
#Sta/Elev= 30
 -419.85  911.45 -367.32  902.27 -337.34     896 -326.06  892.14  -313.9  891.12
 -260.38  879.96 -223.22  874.93 -192.67  873.64 -138.27  876.48  -80.74  874.65
  -65.21  876.48  -38.17   876.5  -29.77  873.72  -23.02  866.42  -19.72  864.54
   -7.25  864.68    2.35  862.72   20.57  863.19    25.4  866.42   25.52  868.41
   38.37  876.34    48.6  875.98  103.52  881.64  126.23  881.94  187.03  886.54
  224.53  888.97  286.24  890.23  323.35  893.44  371.65  893.76  436.17  898.57
#Mann= 5 ,-1,0
 -419.85    .125       0 -326.06     .14       0-23.0199    .043       0
25.39999     .14       0  187.03      .1       0
Bank Sta=-23.02,25.4
XS Rating Curve= 0 ,0
Exp/Cntr=0.3,0.1

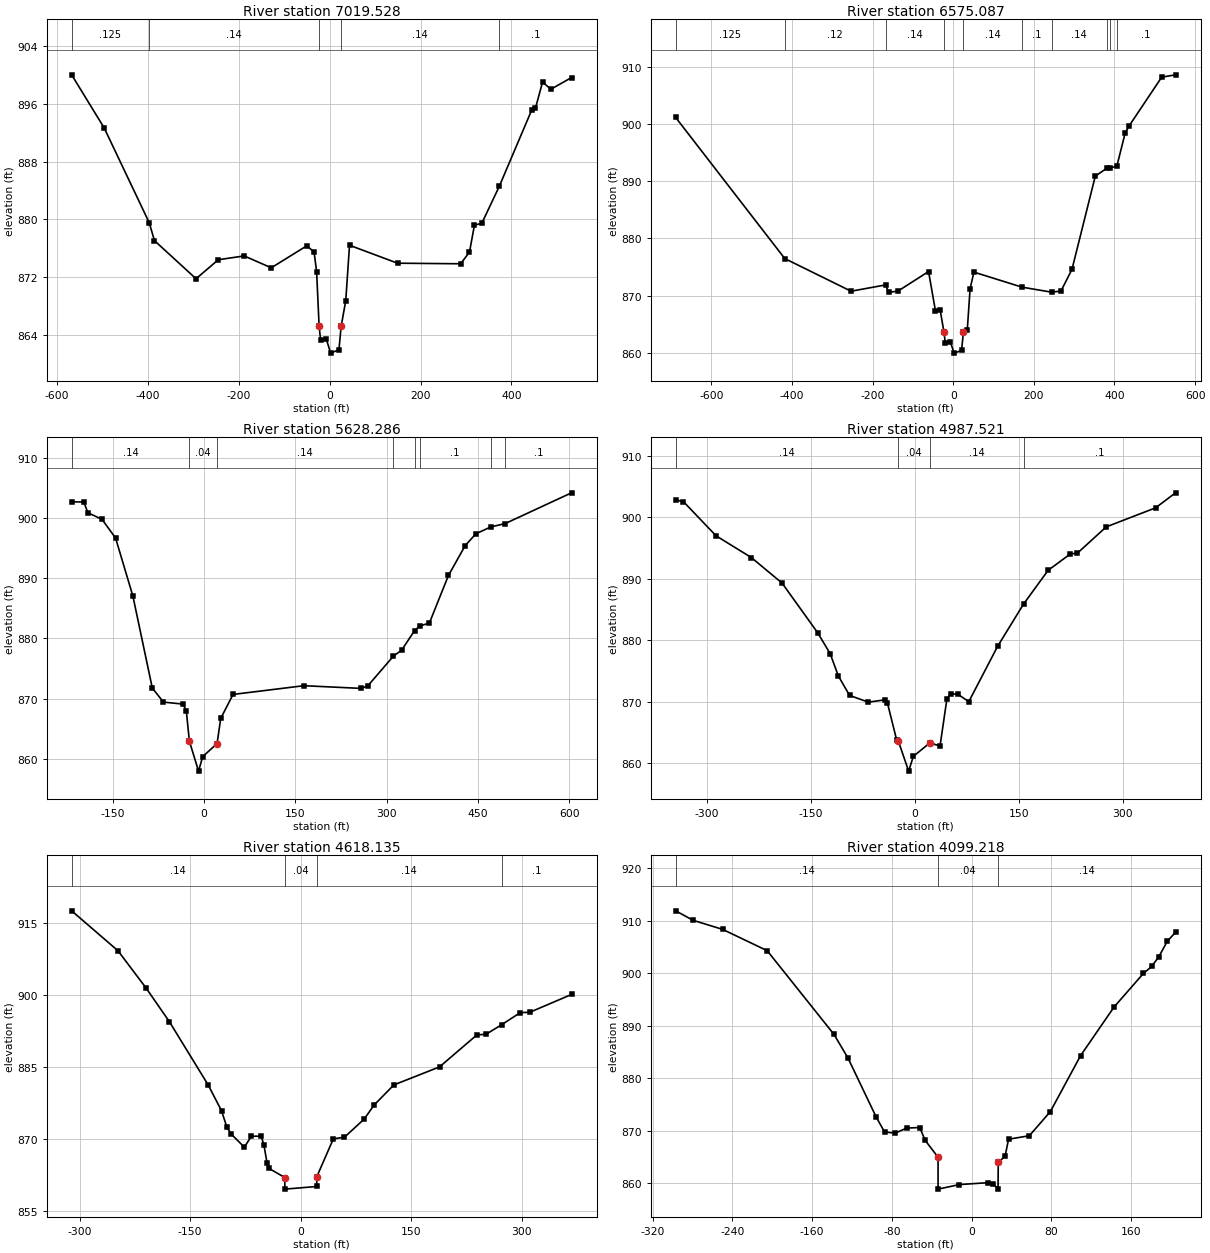
Type RM Length L Ch R = 1 ,7019.528,317.252,444.441,619.2998
BEGIN DESCRIPTION:
TWE_04X
END DESCRIPTION:
XS GIS Cut Line= 4
   1477122.70768   1104008.97047   1476708.67159   1103773.22769
    1476621.4836   1103768.25459   1476086.76017   1103738.74049
#Sta/Elev= 30
 -567.26  900.04 -495.72  892.67 -396.68  879.52 -385.15  877.03 -293.68  871.74
 -244.78  874.38 -187.78  874.91 -128.33  873.26  -49.96  876.32  -34.05  875.44
  -28.52  872.71  -23.02  865.12  -19.72  863.24   -7.25  863.38    2.35  861.42
   20.57  861.89    25.4  865.12   35.56  868.71   43.84  876.39  149.44   873.9
  288.29  873.82   307.7  875.45  318.61  879.19  334.72  879.43  373.29884.5801
  444.48  895.15  452.62  895.37  468.38  899.04  486.66  898.04  532.05  899.66
#Mann= 5 ,-1,0
 -567.26    .125       0 -396.68     .14       0  -23.02    .043       0
25.40002     .14       0  373.29      .1       0
Bank Sta=-23.02,25.4
XS Rating Curve= 0 ,0
Exp/Cntr=0.3,0.1

Type RM Length L Ch R = 1 ,6575.087,780.4042,946.8011,647.1896
XS GIS Cut Line= 3
   1477244.15781   1103985.77493   1476860.04265   1103417.19751
   1476545.37172   1102961.46752
#Sta/Elev= 30
 -688.52  901.14  -417.9  876.46 -253.42  870.75 -167.69  871.85 -160.47  870.56
 -137.36  870.76   -61.2  874.19  -44.23  867.36  -32.45  867.46  -23.02  863.62
  -19.72  861.74   -7.25  861.88    2.35  859.92   20.57  860.39    25.4  863.62
   34.91  864.03   41.81  871.17   51.27  874.09  170.66  871.46  244.17  870.58
   267.3  870.78  294.61  874.58  352.37  890.87  380.67  892.25  387.91  892.33
  405.79  892.59  426.64  898.46  435.83  899.61   517.1  908.19  551.46   908.6
#Mann= 10 ,-1,0
 -688.52    .125       0  -417.9     .12       0 -167.69     .14       0
  -23.02    .043       025.40002     .14       0  170.66      .1       0
  244.17     .14       0  380.67      .1       0  387.91     .06       0
  405.79      .1       0
Bank Sta=-23.02,25.4
XS Rating Curve= 0 ,0
Exp/Cntr=0.3,0.1

Type RM Length L Ch R = 1 ,5628.286,683.7456,640.7651,395.2486
BEGIN DESCRIPTION:
TWE_03X
END DESCRIPTION:
XS GIS Cut Line= 5
   1477654.59121   1103041.12664   1477525.12238   1103045.57448
   1477462.72375   1102980.51214   1477384.50591   1102895.63976
   1476923.56759   1102741.99377
#Sta/Elev= 30
 -217.16  902.66 -197.33  902.63 -190.45  900.85 -167.22  899.74 -145.02  896.65
 -116.64  887.04   -84.7  871.76  -66.34  869.44  -34.31  869.11  -28.87  868.01
  -23.82  862.96   -8.73  857.99   -1.91   860.4   21.68  862.56   27.62  866.72
   47.93  870.71  164.31  872.16  258.59  871.71  269.62  872.17  311.24  877.06
   324.9  878.06  346.05   881.3  354.66  882.06  370.37  882.55  401.66  890.44
  429.21   895.4  446.78  897.36  471.03  898.48  495.06  899.06  603.82  904.15
#Mann= 8 ,-1,0
 -217.16     .14       0  -23.82     .04       021.67999     .14       0
  311.24      .1       0  346.05     .06       0  354.66      .1       0
  471.03     .06       0  495.06      .1       0
Bank Sta=-23.82,21.68
XS Rating Curve= 0 ,0
Exp/Cntr=0.3,0.1

Type RM Length L Ch R = 1 ,4987.521,357.0032,369.3859,338.9796
XS GIS Cut Line= 3
    1477544.5794   1102271.62598   1477251.52822   1102449.89928
   1476931.61352   1102650.15092
#Sta/Elev= 30
  -344.5  902.81 -333.25  902.53 -286.33  896.99 -235.43  893.45 -191.15   889.3
 -140.02  881.26  -121.8  877.83 -110.15  874.23  -93.86  871.04  -66.71  869.95
  -42.56  870.33  -39.26   869.8  -26.17  863.87  -23.82  863.71   -8.73  858.74
   -1.91  861.15   21.68  863.31   36.53  862.84   46.46   870.5   51.65  871.32
   62.28  871.23   77.98  870.03  119.53  879.03  156.83  885.88  192.25  891.37
  224.35  894.04  234.45  894.16  275.99  898.43  347.19  901.53  375.94  903.97
#Mann= 4 ,-1,0
  -344.5     .14       0  -23.82     .04       021.67999     .14       0
  156.83      .1       0
Bank Sta=-23.82,21.68
XS Rating Curve= 0 ,0
Exp/Cntr=0.3,0.1

Type RM Length L Ch R = 1 ,4618.135,531.4022,518.9171,484.8809
XS GIS Cut Line= 4
    1477234.4334   1102027.41667    1476985.3399   1102217.90026
   1476851.02461   1102320.46818   1476836.37205   1102515.83563
#Sta/Elev= 30
 -310.89   917.5 -248.06  909.19 -209.96  901.44 -178.24  894.41 -125.52  881.21
 -107.47  875.86 -100.08  872.38  -94.25  870.99  -76.54  868.27  -66.95  870.54
   -53.6  870.56  -49.96  868.75  -45.59  864.92  -43.28  863.87  -21.65  861.95
  -21.45  859.53   21.83  860.08   21.85  862.11   44.31     870   59.45  870.35
   86.14  874.11    99.6  877.04  126.41  881.23  188.45  884.99  239.06  891.64
  251.72   891.8   272.6  893.76  298.14   896.3  311.03  896.37  367.61  900.08
#Mann= 4 ,-1,0
 -310.89     .14       0-21.6499     .04       021.85001     .14       0
   272.6      .1       0
Bank Sta=-21.65,21.85
XS Rating Curve= 0 ,0
Exp/Cntr=0.3,0.1

Type RM Length L Ch R = 1 ,4099.218,529.37,545.3509,563.7048
BEGIN DESCRIPTION:
TWE_02X
END DESCRIPTION:
XS GIS Cut Line= 3
   1476797.89042   1101610.62402   1476639.69259   1101842.92717
   1476523.97277   1102030.91634
#Sta/Elev= 30
 -297.03  911.91 -279.76  910.12 -249.81  908.37 -205.17  904.32 -138.05  888.37
 -124.05  883.88  -95.67  872.62  -87.38  869.82  -76.87  869.57  -64.96  870.55
     -52  870.65  -46.58  868.21  -33.64     865   -33.6  858.92  -12.14  859.79
   16.02  860.14   21.83  859.88   26.61  858.99   26.79     864   33.69  865.21
   37.14  868.42   58.04  869.09   79.09  873.68  109.49  884.35  143.04  893.59
  172.49  899.98  180.82  901.31  188.11  903.21  196.55  906.13  204.77  907.82
#Mann= 3 ,-1,0
 -297.03     .14       0-33.6398     .04       026.79001     .14       0
Bank Sta=-33.64,26.79
XS Rating Curve= 0 ,0
Exp/Cntr=0.3,0.1

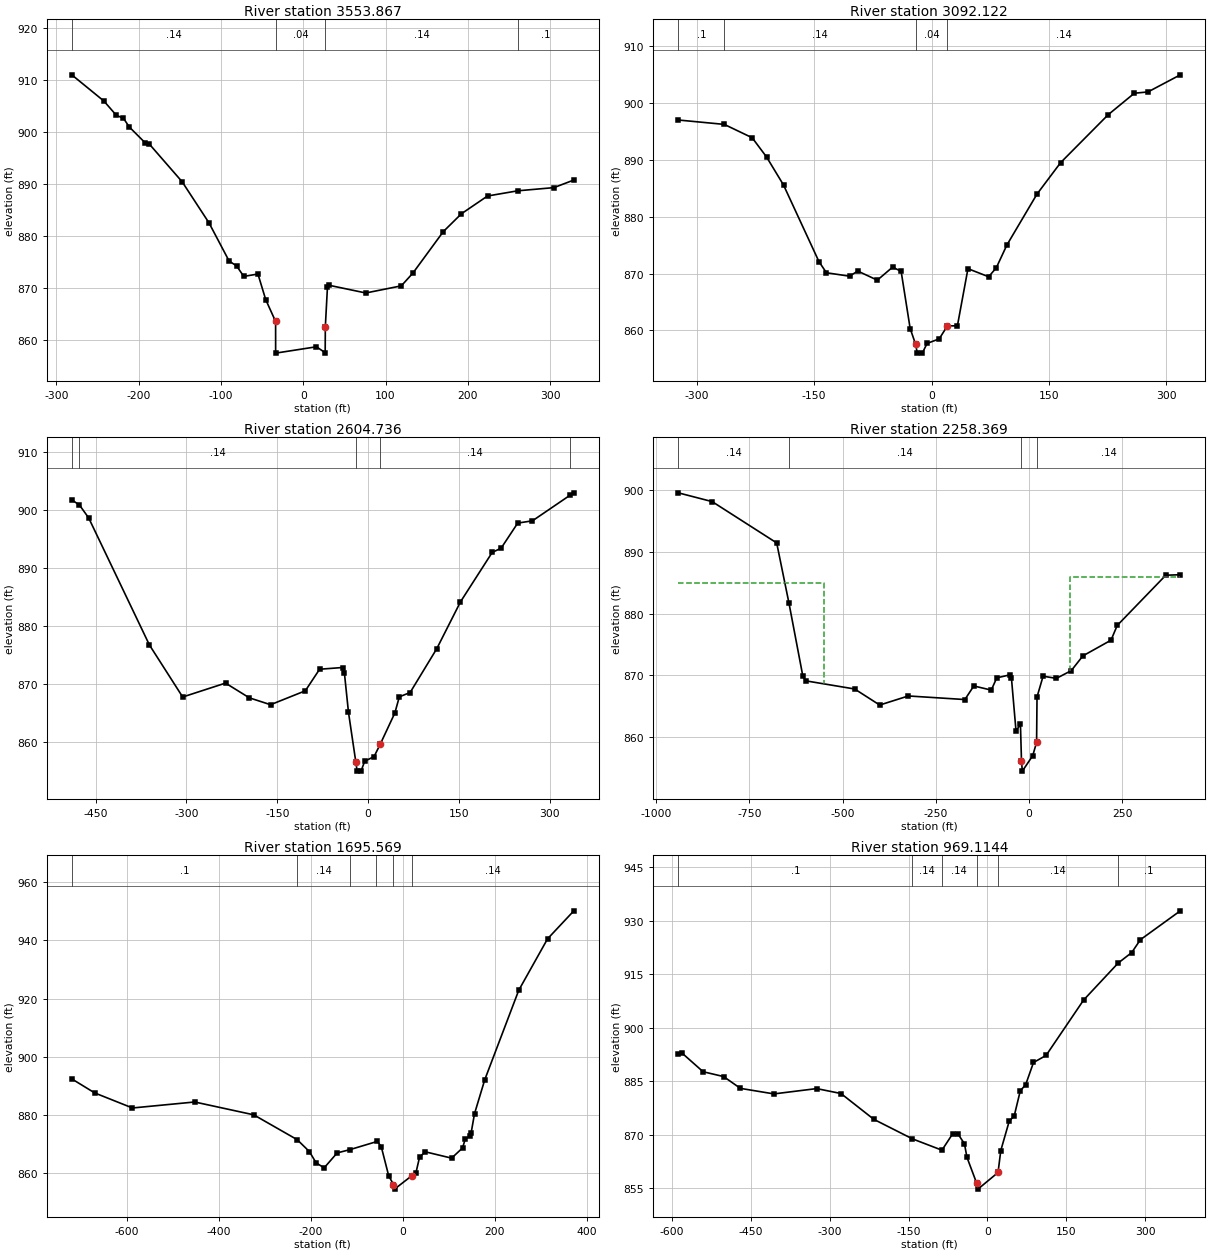
Type RM Length L Ch R = 1 ,3553.867,427.0496,461.7459,467.1004
XS GIS Cut Line= 3
   1476452.26115   1101272.59154   1476250.87172   1101470.50886
    1476014.7605   1101697.93996
#Sta/Elev= 30
 -281.37  910.99 -242.31  905.95  -227.1  903.19 -218.66  902.66 -211.42  900.96
 -192.22  897.93 -187.55  897.76 -147.25  890.44 -114.64  882.55  -90.14   875.2
  -81.05  874.26  -72.35  872.25   -55.1   872.7  -45.68  867.79  -33.64  863.58
   -33.6   857.5   16.02  858.72   26.61  857.57   26.79  862.58   29.41   870.3
   30.76  870.56   75.96  869.06  119.11  870.43   133.2  872.88  170.14  880.85
  192.21  884.29   223.9   887.7   260.7   888.7  304.55  889.31  328.82  890.77
#Mann= 4 ,-1,0
 -281.37     .14       0  -33.64     .04       026.79001     .14       0
   260.7      .1       0
Bank Sta=-33.64,26.79
XS Rating Curve= 0 ,0
Exp/Cntr=0.3,0.1

Type RM Length L Ch R = 1 ,3092.122,534.8873,487.3857,428.1481
XS GIS Cut Line= 3
   1476196.61844   1101002.40912   1475910.15945   1101171.68012
   1475649.74245   1101336.61122
#Sta/Elev= 30
 -323.34  897.03 -264.58  896.26 -228.96  893.91 -210.61  890.53 -188.95   885.6
 -143.74  872.13 -134.16  870.15 -104.59  869.55  -94.17  870.45  -69.17  868.85
  -49.67  871.14  -38.77   870.4  -27.25  860.34  -20.35  857.59  -18.12  856.01
  -11.69  856.03   -5.63  857.72    9.82  858.52   20.28   860.8   33.07  860.82
   46.53  870.87   72.92  869.45   82.69  871.02   96.18  875.02   134.6  883.98
  164.78  889.52  225.55  897.96  258.93  901.74  276.33  901.97  317.64  904.98
#Mann= 4 ,-1,0
 -323.34      .1       0 -264.58     .14       0  -20.35     .04       0
   20.28     .14       0
Bank Sta=-20.35,20.28
XS Rating Curve= 0 ,0
Exp/Cntr=0.3,0.1

Type RM Length L Ch R = 1 ,2604.736,291.1653,346.3675,411.856
BEGIN DESCRIPTION:
TWE_01X
END DESCRIPTION:
XS GIS Cut Line= 4
   1475956.78379   1100543.39239   1475640.49803   1100727.75164
   1475599.90486   1100839.38222   1475520.41076   1101174.27329
#Sta/Elev= 30
 -489.38  901.82 -476.65  900.92 -461.46   898.7 -361.11  876.77 -306.23   867.8
 -235.47   870.2 -196.22  867.66 -161.12  866.47 -103.73  868.87  -80.15  872.59
  -42.17  872.89  -39.13  871.89  -32.45  865.16  -20.35  856.59  -18.12  855.01
  -11.69  855.03   -5.63  856.72    9.82  857.52   20.09  859.68   44.15  865.05
   51.49  867.83   69.32  868.57  113.35  876.14  152.49  884.22  204.88  892.75
  219.61  893.48  247.02  897.81  271.34   898.2  333.19   902.6  339.69  903.03
#Mann= 5 ,-1,0
 -489.38      .1       0 -476.65     .14       0  -20.35    .046       0
   20.09     .14       0  333.19      .1       0
Bank Sta=-20.35,20.09
XS Rating Curve= 0 ,0
Exp/Cntr=0.3,0.1

Type RM Length L Ch R = 1 ,2258.369,511.7773,562.8007,577.5682
XS GIS Cut Line= 5
   1476001.42979   1100175.31496   1475837.36713    1100236.5128
   1475276.86581   1100757.43898   1475055.04167   1100963.62238
   1474978.96883   1101032.19423
#Sta/Elev= 30
 -940.29  899.57 -849.44  898.15 -676.45  891.46 -643.46  881.69 -606.41  869.91
  -598.6  869.13 -467.52  867.81 -400.32  865.21 -323.68  866.68 -172.11   866.1
 -148.18   868.3 -101.41  867.63  -86.64  869.61  -49.99  870.12  -47.38  869.63
  -35.09  861.04  -23.14  862.07  -20.35  856.09  -18.12  854.51    9.82  857.02
   20.09  859.18   21.26  866.52   37.53  869.88   73.24  869.53  112.98  870.78
  144.18  873.17  219.51  875.71  236.22   878.1  366.34  886.23  405.27  886.31
#Mann= 4 ,-1,0
 -940.29     .14       0 -643.46     .14       0-20.3499     .04       0
20.09003     .14       0
#XS Ineff= 2 ,-1
 -940.29 -549.72  884.97110.1299  405.27  885.94
Permanent Ineff=
       F       F
Bank Sta=-20.35,20.09
XS Rating Curve= 0 ,0
Exp/Cntr=0.3,0.1

Type RM Length L Ch R = 1 ,1695.569,436.1527,726.4543,810.4975
XS GIS Cut Line= 4
   1475801.82579   1100230.16043   1475487.84678   1100083.03904
   1475150.54364   1100222.98392   1474802.47539   1100375.48786
#Sta/Elev= 30
 -720.01   892.4 -669.98  887.56    -588   882.4 -452.69  884.46 -324.32  880.05
 -229.79  871.51 -203.23  867.42 -188.62  863.55 -171.11  861.82 -142.79  866.96
 -115.59  868.06  -55.35  870.92  -46.88  869.07  -30.74  859.08  -20.35  856.09
  -18.12  854.51   20.09  859.18   28.34  860.01   36.56  865.63   49.21  867.32
  106.02  865.16  129.79  868.65  136.06  871.86  145.44  872.69  148.35  873.66
  155.87  880.42   178.2  892.12   252.1  922.86  314.77  940.54  371.92  950.16
#Mann= 6 ,-1,0
 -720.01      .1       0 -229.79     .14       0 -115.59      .1       0
-58.1099     .14       0-20.3499     .04       020.09003     .14       0
Bank Sta=-20.35,20.09
XS Rating Curve= 0 ,0
Exp/Cntr=0.3,0.1

Type RM Length L Ch R = 1 ,969.1144,537.2684,525.7077,496.0154
XS GIS Cut Line= 4
    1475817.9731   1100217.60138   1475548.03018   1100066.70472
   1475482.92585   1099790.66306   1475399.59252   1099439.10072
#Sta/Elev= 30
  -587.7  892.68 -580.27  892.87 -540.42  887.66 -501.53  886.31 -469.51  882.99
 -405.88  881.44 -324.65  882.93 -278.45  881.55 -215.98   874.3 -142.62  868.82
  -86.54  865.64  -66.38  870.19  -55.87  870.15  -43.79  867.45  -38.96  863.63
  -20.35  856.29  -18.12  854.71   20.09  859.38   25.29  865.54   41.38  873.82
    50.8  875.25   62.35  882.32   72.56  884.02   87.45  890.26  111.37  892.24
   182.7  907.79  248.38  918.17  274.15  921.12  290.56  924.72  366.47  932.83
#Mann= 6 ,-1,0
  -587.7      .1       0 -142.62     .14       0  -86.54     .14       0
-20.3499     .04       020.09003     .14       0  248.38      .1       0
Bank Sta=-20.35,20.09
XS Rating Curve= 0 ,0
Exp/Cntr=0.3,0.1