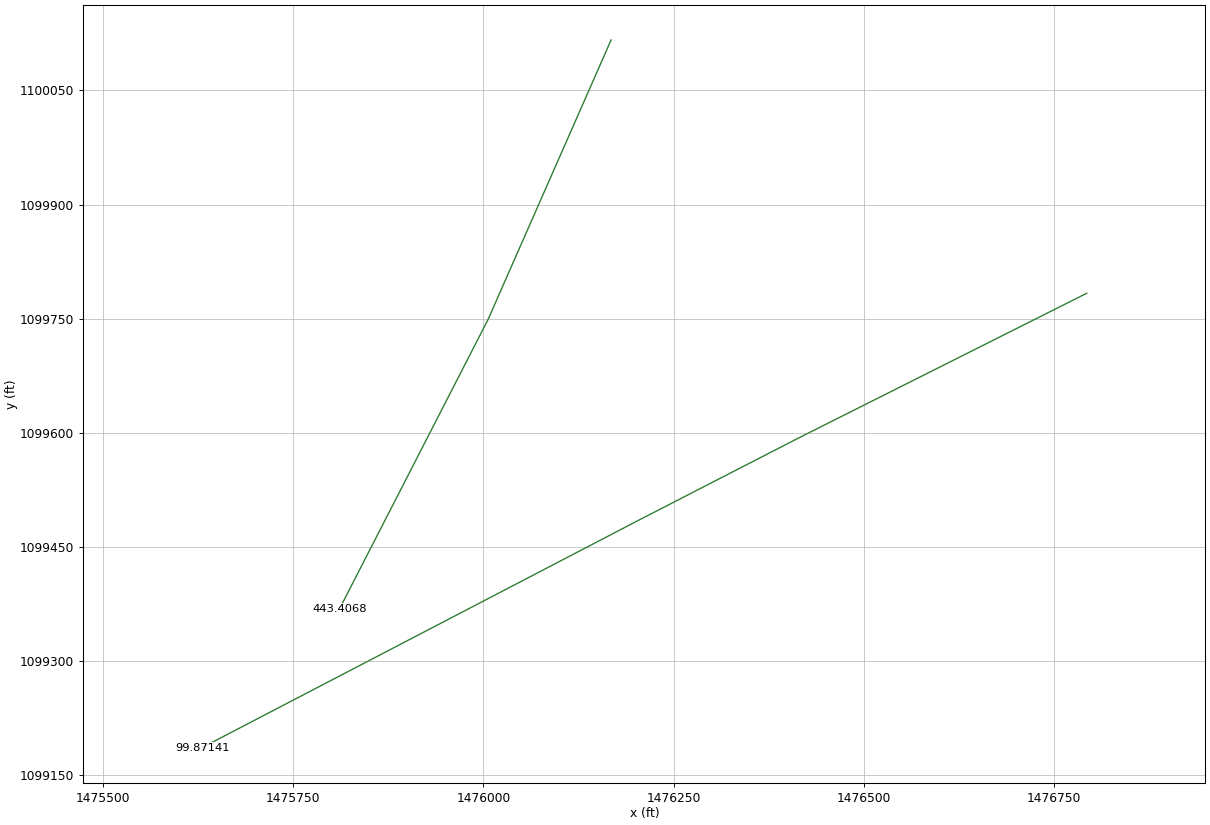
HEC-RAS study 12mile_Combined.prj: 12mile Creek Combined Model

--- 12mile_Combined.g07 (geometry) --- (continued)

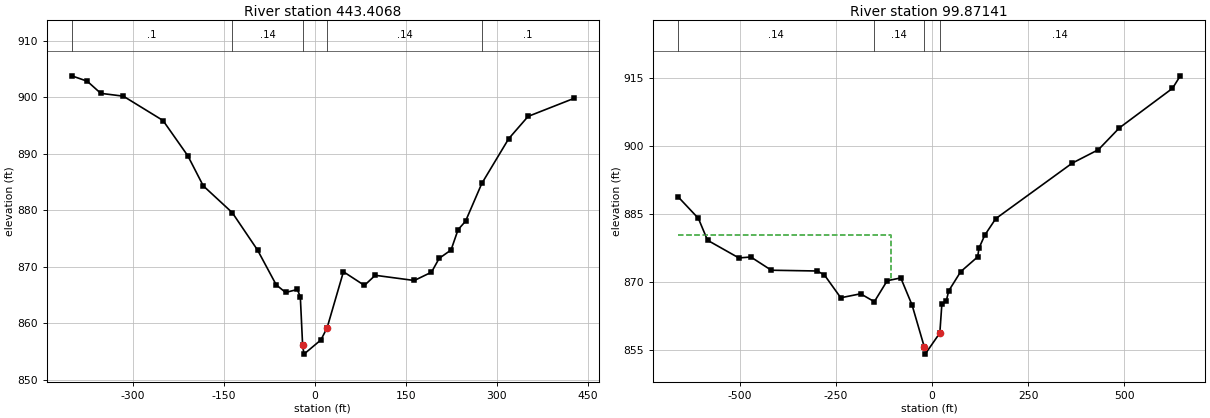
Type RM Length L Ch R = 1 ,443.4068,399.3098,343.5354,278.3133
XS GIS Cut Line= 3
   1476167.82185   1100116.18406   1476006.36056   1099749.32415
   1475811.05085   1099368.78806
#Sta/Elev= 30
 -401.31  903.76 -375.83  902.81 -353.44  900.66 -316.18  900.16 -250.72  895.85
 -209.75   889.6 -184.32  884.29 -136.47  879.55   -94.7  872.92   -63.9  866.77
  -48.42  865.42  -29.21  865.95  -24.16  864.69  -20.35  856.09  -18.12  854.51
    9.82  857.02   20.09  859.18   47.01  869.09   81.64  866.67   99.47  868.46
  163.94  867.54  192.32  869.01  204.99  871.46   224.6  872.94  236.19  876.54
  248.45  878.02  275.33  884.71  319.71  892.63  351.74  896.58  427.24  899.76
#Mann= 5 ,-1,0
 -401.31      .1       0 -136.47     .14       0  -20.35     .04       0
   20.09     .14       0  275.33      .1       0
Bank Sta=-20.35,20.09
XS Rating Curve= 0 ,0
Exp/Cntr=0.5,0.3

Type RM Length L Ch R = 1 ,99.87141,68.07822,99.87141,126.4536
BEGIN DESCRIPTION:
Limit of Detailed Study (Just US of SC Hwy 267)
END DESCRIPTION:
XS GIS Cut Line= 4
   1476792.64895   1099783.43012   1476415.20997   1099593.88091
   1476203.08858   1099484.80709    1475630.5397   1099186.64173
#Sta/Elev= 30
 -660.61  888.75 -608.23  884.02 -584.41  879.18 -502.89  875.27 -471.58  875.47
 -418.43  872.55 -299.16  872.38  -280.3  871.51 -237.71  866.46 -186.06  867.34
 -150.34865.5909  -116.9  870.23  -81.53  870.85  -52.07  864.83  -20.35  855.58
  -18.12     854   20.09  858.67    25.3  865.01   36.68  865.71    43.2  867.99
   74.37  872.23  118.48   875.5  121.99  877.44  137.07  880.31  165.54  883.95
   364.6  896.23  432.69   899.2  487.21  904.02  625.42  912.76  645.81  915.53
#Mann= 4 ,-1,0
 -660.61     .14       0 -150.34     .14       0-20.3499     .04       0
20.09003     .14       0
#XS Ineff= 2 , 0
            -108   880.3
Permanent Ineff=
       F       F
Bank Sta=-20.35,20.09
XS Rating Curve= 0 ,0
Exp/Cntr=0.5,0.3
LCMann Table=0

Chan Stop Cuts=-1
Use User Specified Reach Order=0
Composite Channel Slope=5

--- 12mile_Combined.g01 (geometry) ---

Geom Title=Generated by CreateGeometryFile written by the GeoFIRM tool.
Program Version=6.10

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
River Reach=Twelvemile Crk  ,Reach1

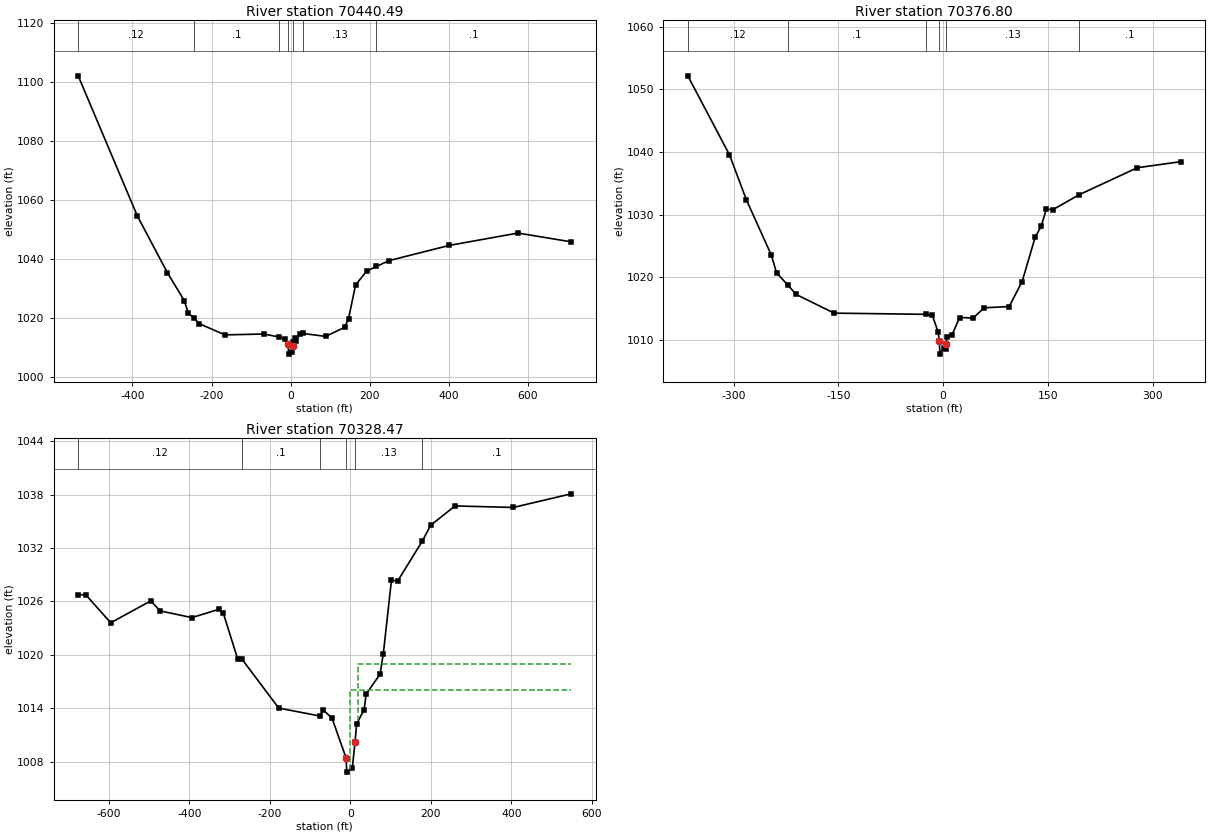
Type RM Length L Ch R = 1 ,70440.49,20.57367,63.69299,100.789
XS GIS Cut Line= 6
   1496196.42946   1144264.92651   1495864.62434   1144066.57251
   1495691.79396   1144089.90846   1495474.47999   1144232.11056
   1495397.90945   1144284.61614   1495119.33891   1144468.38517
#Sta/Elev= 30
 -537.38 1102.12    -388 1054.77  -311.9 1035.52 -268.63 1025.94 -258.82 1021.74
 -244.08 1020.11 -231.48 1018.22 -166.04 1014.42   -67.9 1014.71   -29.5 1013.72
  -15.35 1012.99   -6.87 1011.36   -4.45  1007.9    4.13  1008.7    5.33 1010.56
    6.38 1011.96   10.12 1013.23   14.75 1012.51   24.22 1014.84    30.2 1014.92
   88.48  1013.9  136.73 1016.96  146.67 1019.94  164.44 1031.32  192.33 1035.98
  217.22 1037.59  249.85 1039.59  401.23  1044.7  575.26 1048.89  709.88 1045.92
#Mann= 7 ,-1,0
 -537.38     .12       0 -244.08      .1       0   -29.5     .13       0
   -6.87    .045       0    5.33     .13       0    30.2     .13       0
  217.22      .1       0
Bank Sta=-6.87,5.33
XS Rating Curve= 0 ,0
Exp/Cntr=0.3,0.1

Type RM Length L Ch R = 1 ,70376.80,96.50882,48.3321,38.07024
BEGIN DESCRIPTION:
TWE_39USX
END DESCRIPTION:
XS GIS Cut Line= 5
   1496091.77723   1144119.63615   1495867.47835    1144060.1706
   1495738.18734   1144028.10171    1495665.0876   1144013.22441
   1495421.00984   1144118.80413
#Sta/Elev= 30
 -365.44 1052.18 -305.77 1039.55 -281.42 1032.32 -245.78 1023.51 -238.46 1020.71
  -221.9 1018.69  -210.4 1017.25 -155.93 1014.25  -24.15 1014.06  -15.27 1013.88
   -6.87 1011.16   -5.45  1009.8   -4.45  1007.7     .91 1008.71    4.13  1008.5
    4.71 1009.39    5.33 1010.36   12.52 1010.71   23.79 1013.55   43.11 1013.47
   58.95 1015.11   94.65  1015.3  113.17 1019.28  131.86 1026.38  140.43 1028.11
  147.92 1030.88  157.35  1030.8  195.09 1033.19  278.13 1037.49  340.35 1038.46
#Mann= 6 ,-1,0
 -365.44     .12       0  -221.9      .1       0  -24.15     .13       0
   -5.45    .045       0    4.71     .13       0  195.09      .1       0
Bank Sta=-5.45,4.71
XS Rating Curve= 0 ,0
Exp/Cntr=0.5,0.3

Type RM Length L Ch R = 1 ,70328.47,64.05273,59.09576,61.7731
BEGIN DESCRIPTION:
Log House Rd (TWE_39) - US
END DESCRIPTION:
XS GIS Cut Line= 3
   1496421.06857   1143843.50164   1495734.58333   1143980.87303
   1495183.18602   1144116.22277
#Sta/Elev= 30
-675.955 1026.76-656.733 1026.73-595.203  1023.6-495.472 1026.06-472.637 1024.94
 -393.74 1024.18-327.043  1025.1-315.568  1024.7-279.481  1019.5-269.223 1019.52
-177.711 1014.02 -76.163 1013.14 -66.572  1013.8 -45.157 1012.86 -10.335 1008.41
  -8.732 1006.83   5.023 1007.28  11.794 1010.19  15.841 1012.24  34.561 1013.86
  39.361 1015.59  74.038 1017.83  82.152 1020.15 102.253 1028.37 117.785 1028.29
 178.551 1032.74  199.57 1034.54 260.259 1036.72 404.974 1036.55 548.704 1038.08
#Mann= 6 ,-1,0
-675.955     .12       0-269.223      .1       0 -76.163     .13       0
 -10.335    .045       0  11.794     .13       0 178.551      .1       0
#XS Ineff= 2 , 0
       0     -20    1016      20       0    1019
Permanent Ineff=
       F       F
Bank Sta=-10.335,11.794
XS Rating Curve= 0 ,0
Skew Angle= 15
Exp/Cntr=0.5,0.3