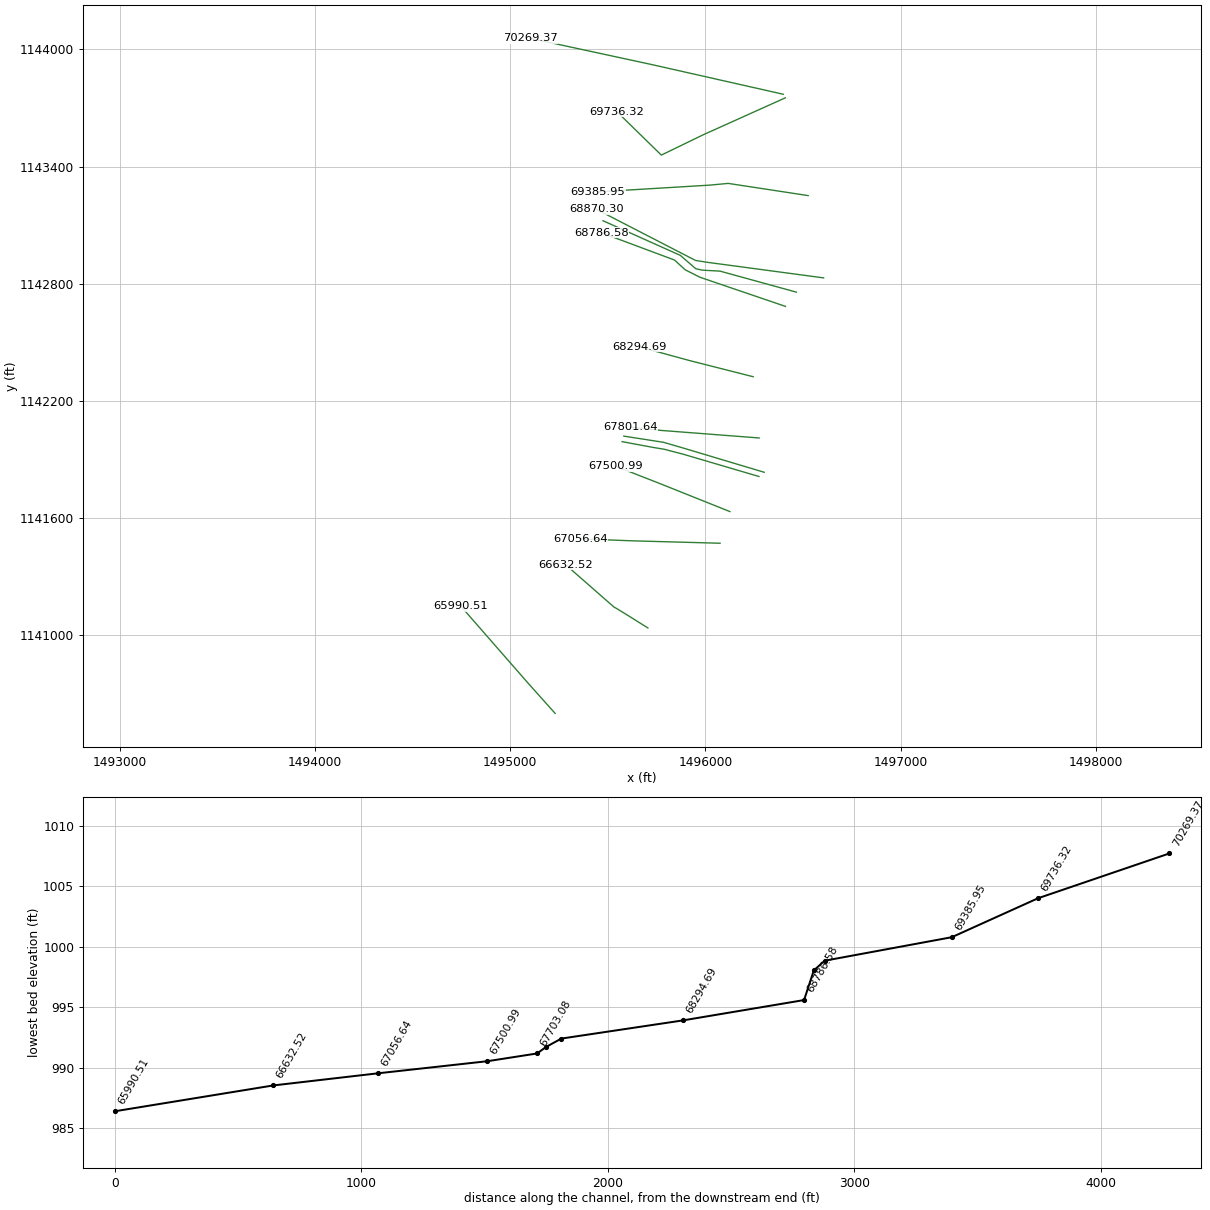
HEC-RAS study 12mile_Combined.prj: 12mile Creek Combined Model

--- 12mile_Combined.g01 (geometry) --- (continued)

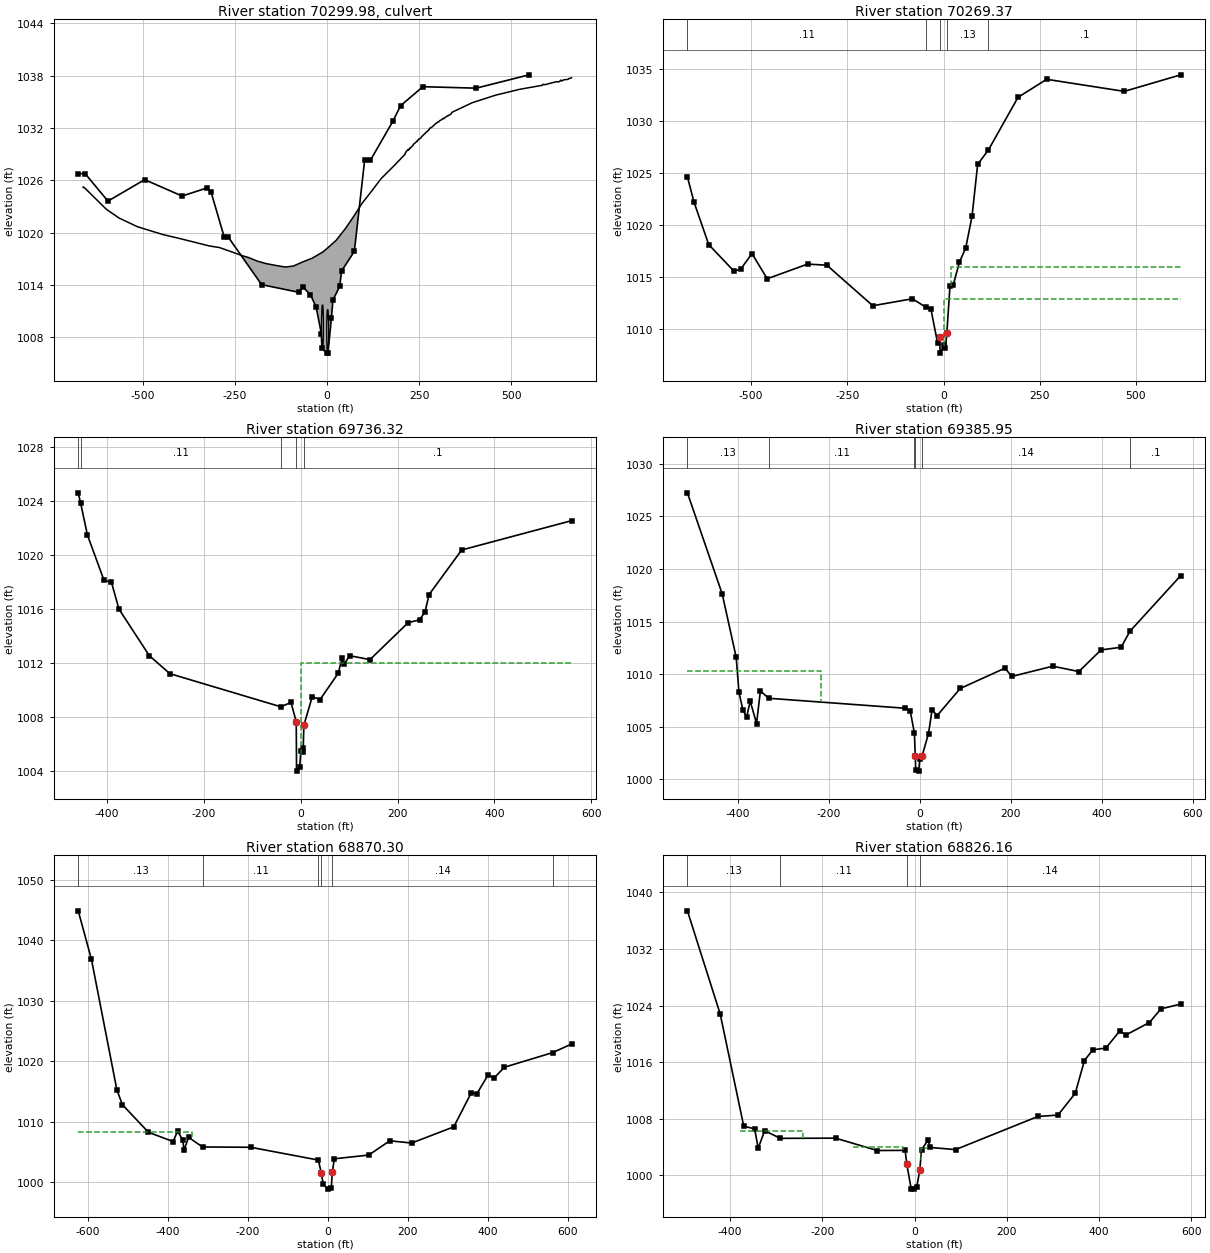
Type RM Length L Ch R = 2 ,70299.98,,,
BEGIN DESCRIPTION:
Log House Rd (TWE_39) - TOR
Skew = 15 degrees
END DESCRIPTION:
Bridge Culvert--1,0,-1,-1, 0
Deck Dist Width WeirC Skew NumUp NumDn MinLoCord MaxHiCord MaxSubmerge Is_Ogee
8,42.3,2.6,15, 151, 151, 1016.04, , 0.95, 0, 0,0,,
-662.867-662.673-659.254-599.975-565.405-514.993-446.364-405.003-367.081-319.799
-291.932-249.025-231.252-213.721-189.544-166.091-141.354-113.245 -91.087 -66.659
 -40.781 -26.582 -12.045  -3.738   1.545  24.805  50.788  73.121  94.574 119.997
 146.985 181.575 211.741 212.639 213.875 214.455  215.15 215.479 218.811 220.328
 222.202 222.907 224.925 225.379 227.765 228.731 231.813 233.184 234.469 235.947
 236.884 237.666   241.8 242.341 243.945 245.268 246.002 246.958 248.707 251.005
  252.59  254.29 255.681 256.589 258.105 258.289 260.858 262.529 264.635 265.591
  265.89  266.47 267.851 268.411 270.063 271.589 272.352 274.246 274.767 276.042
 277.114 278.283   279.5 279.838 283.605 284.156 286.242 287.392 289.227   289.7
 291.082 291.671 292.511 294.366 296.278  299.08 300.934 303.146 305.435 306.343
 309.676  312.69 313.636 315.462 316.592 317.867 319.635 322.165 323.952  325.16
 326.792   327.7 329.564  331.09 334.471 334.877 336.538 338.103  339.04 394.706
 457.994 523.242 584.704 586.269  590.76 592.364 594.595 615.073 618.888 621.728
 623.834  628.47 629.165 629.958 632.044 632.334 633.937 634.517 636.806  637.54
 640.148 642.003 644.205 644.813 646.948 651.903 653.372 655.342 656.675 661.756
 664.026
  1025.2 1025.17 1025.15 1022.68 1021.67 1020.66 1019.77 1019.36 1018.96 1018.46
 1018.27 1017.63 1017.35 1017.14 1016.72 1016.44 1016.24 1016.04 1016.16 1016.62
 1017.05 1017.39 1017.75 1018.04 1018.23 1019.11 1020.51  1021.9 1023.32 1024.69
 1026.19 1027.64 1028.97 1029.12 1029.17 1029.23 1029.29 1029.33 1029.42 1029.54
 1029.47 1029.51 1029.71 1029.69 1029.73  1029.8 1029.92 1029.98 1030.11 1030.16
 1030.18 1030.22 1030.36 1030.39 1030.46 1030.55 1030.52 1030.59 1030.71 1030.72
 1030.77 1030.83 1030.91 1030.97 1031.02 1031.06 1031.15  1031.2 1031.28 1031.33
 1031.34 1031.39 1031.44 1031.45 1031.54 1031.57  1031.6  1031.7 1031.72 1031.76
 1031.77 1031.89 1031.96 1031.99 1032.03 1032.06 1032.17 1032.18 1032.24 1032.26
 1032.34 1032.38  1032.4 1032.46 1032.51  1032.6 1032.67 1032.67 1032.81 1032.84
  1032.9 1032.99 1033.02  1033.1 1033.06 1033.06 1033.15 1033.24 1033.27 1033.32
  1033.4 1033.41 1033.39 1033.45 1033.52 1033.53 1033.61 1033.67 1033.78 1034.89
 1035.75 1036.42 1036.88 1036.99 1036.96 1036.95 1036.98 1037.21 1037.25 1037.27
 1037.29 1037.27 1037.27 1037.29 1037.35 1037.35 1037.44 1037.48 1037.37 1037.38
 1037.45 1037.49 1037.51 1037.52 1037.53 1037.54 1037.55 1037.58 1037.66 1037.69
 1037.74
                                                                                
                                                                                
                                                                                
                                                                                
                                                                                
                                                                                
                                                                                
                                                                                
                                                                                
                                                                                
                                                                                
                                                                                
                                                                                
                                                                                
                                                                                
        
-662.867-662.673-659.254-599.975-565.405-514.993-446.364-405.003-367.081-319.799
-291.932-249.025-231.252-213.721-189.544-166.091-141.354-113.245 -91.087 -66.659
 -40.781 -26.582 -12.045  -3.738   1.545  24.805  50.788  73.121  94.574 119.997
 146.985 181.575 211.741 212.639 213.875 214.455  215.15 215.479 218.811 220.328
 222.202 222.907 224.925 225.379 227.765 228.731 231.813 233.184 234.469 235.947
 236.884 237.666   241.8 242.341 243.945 245.268 246.002 246.958 248.707 251.005
  252.59  254.29 255.681 256.589 258.105 258.289 260.858 262.529 264.635 265.591
  265.89  266.47 267.851 268.411 270.063 271.589 272.352 274.246 274.767 276.042
 277.114 278.283   279.5 279.838 283.605 284.156 286.242 287.392 289.227   289.7
 291.082 291.671 292.511 294.366 296.278  299.08 300.934 303.146 305.435 306.343
 309.676  312.69 313.636 315.462 316.592 317.867 319.635 322.165 323.952  325.16
 326.792   327.7 329.564  331.09 334.471 334.877 336.538 338.103  339.04 394.706
 457.994 523.242 584.704 586.269  590.76 592.364 594.595 615.073 618.888 621.728
 623.834  628.47 629.165 629.958 632.044 632.334 633.937 634.517 636.806  637.54
 640.148 642.003 644.205 644.813 646.948 651.903 653.372 655.342 656.675 661.756
 664.026
  1025.2 1025.17 1025.15 1022.68 1021.67 1020.66 1019.77 1019.36 1018.96 1018.46
 1018.27 1017.63 1017.35 1017.14 1016.72 1016.44 1016.24 1016.04 1016.16 1016.62
 1017.05 1017.39 1017.75 1018.04 1018.23 1019.11 1020.51  1021.9 1023.32 1024.69
 1026.19 1027.64 1028.97 1029.12 1029.17 1029.23 1029.29 1029.33 1029.42 1029.54
 1029.47 1029.51 1029.71 1029.69 1029.73  1029.8 1029.92 1029.98 1030.11 1030.16
 1030.18 1030.22 1030.36 1030.39 1030.46 1030.55 1030.52 1030.59 1030.71 1030.72
 1030.77 1030.83 1030.91 1030.97 1031.02 1031.06 1031.15  1031.2 1031.28 1031.33
 1031.34 1031.39 1031.44 1031.45 1031.54 1031.57  1031.6  1031.7 1031.72 1031.76
 1031.77 1031.89 1031.96 1031.99 1032.03 1032.06 1032.17 1032.18 1032.24 1032.26
 1032.34 1032.38  1032.4 1032.46 1032.51  1032.6 1032.67 1032.67 1032.81 1032.84
  1032.9 1032.99 1033.02  1033.1 1033.06 1033.06 1033.15 1033.24 1033.27 1033.32
  1033.4 1033.41 1033.39 1033.45 1033.52 1033.53 1033.61 1033.67 1033.78 1034.89
 1035.75 1036.42 1036.88 1036.99 1036.96 1036.95 1036.98 1037.21 1037.25 1037.27
 1037.29 1037.27 1037.27 1037.29 1037.35 1037.35 1037.44 1037.48 1037.37 1037.38
 1037.45 1037.49 1037.51 1037.52 1037.53 1037.54 1037.55 1037.58 1037.66 1037.69
 1037.74
                                                                                
                                                                                
                                                                                
                                                                                
                                                                                
                                                                                
                                                                                
                                                                                
                                                                                
                                                                                
                                                                                
                                                                                
                                                                                
                                                                                
                                                                                
        
BR Coef=-1 , 1 , 0 ,, 0 ,,,0.8,0,,0,
WSPro=,,,, 1 ,,,, 0 ,,,, 0 ,,,,-1 ,-1 ,-1 , 0 , 0 , 0 , 0 , 0
Culvert=1,5,,42.3,0.013,0.2,1,1,3,1006.72,-12.47,1006.71,-12.47,Culvert #1  , 0 ,8
  -12.47  -12.47
BC Culvert Barrel=1,,0
Culvert Bottom n=0.013
Culvert=1,5,,42.3,0.013,0.2,1,1,3,1006.17,1.6,1006.8,1.6,Culvert #2  , 0 ,8
     1.6     1.6
BC Culvert Barrel=1,,0
Culvert Bottom n=0.013
BR U #Sta/Elev= 30
-675.955 1026.76-656.733 1026.73-595.203  1023.6-495.472 1026.06 -393.74 1024.18
-327.043  1025.1-315.568  1024.7-279.481  1019.5-269.223 1019.52-177.711 1014.02
 -76.163 1013.14 -66.572  1013.8 -45.157 1012.86 -29.693 1011.46 -15.585 1008.41
 -14.079 1006.71  -1.063 1006.17   2.338 1006.17  11.794 1010.19  15.841 1012.24
  34.561 1013.86  39.361 1015.59  74.038 1017.83 102.253 1028.37 117.785 1028.29
 178.551 1032.74  199.57 1034.54 260.259 1036.72 404.974 1036.55 548.704 1038.08
BR U #Mann= 6
-675.955     .12-269.223      .1 -76.163     .13 -15.585    .045  11.794     .13
 178.551      .1
BR U Banks=-15.585,
BR D #Sta/Elev= 30
-665.397 1024.63-648.368 1022.21-609.992 1018.12-544.647 1015.58-527.048 1015.75
-497.713 1017.26-458.081 1014.84-352.959 1016.25-303.059 1016.14 -183.68 1012.25
 -80.751 1012.92 -46.055 1012.11 -32.996 1011.98 -15.551  1008.7 -14.006 1006.71
 -10.335 1006.71   2.338 1006.71   6.307  1008.7  11.794 1011.06  16.778 1014.14
  26.051 1014.32  54.932 1017.43  65.799 1019.16  74.058 1020.82   88.73 1025.82
 116.732 1027.21  193.63 1032.26 267.977 1033.99 469.662 1032.83 616.406 1034.42
BR D #Mann= 5
-665.397     .11 -46.055     .13 -10.335    .045  11.794     .13 116.732      .1
BR D Banks=-15.551,6.307
BC Design=,, 0 ,, 0 ,,,,,,
BC Use User HTab Curves=0
BC User HTab FreeFlow(D)= 0

Type RM Length L Ch R = 1 ,70269.37,376.0072,533.0539,464.8225
BEGIN DESCRIPTION:
Log House Rd (TWE_39) - DS
END DESCRIPTION:
XS GIS Cut Line= 3
    1496398.9334   1143770.58465   1495727.60039   1143922.15157
   1495103.20636   1144057.00722
#Sta/Elev= 30
-665.397 1024.63-648.368 1022.21-609.992 1018.12-544.647 1015.58-527.048 1015.75
-497.713 1017.26-458.081 1014.84-352.959 1016.25-303.059 1016.14 -183.68 1012.25
 -80.751 1012.92 -46.055 1012.11 -32.996 1011.98 -15.551  1008.7 -10.335 1009.28
  -8.732  1007.7    .715 1008.47   5.023 1008.15    8.74 1009.67  16.778 1014.14
  25.616 1014.28  41.255 1016.43  57.579 1017.78  74.058 1020.82   88.73 1025.82
 116.732 1027.21  193.63 1032.26 267.977 1033.99 469.662 1032.83 616.406 1034.42
#Mann= 5 ,-1,0
-665.397     .11       0 -46.055     .13       0 -10.335    .045       0
    8.74     .13       0 116.732      .1       0
#XS Ineff= 2 , 0
       0     -20  1012.9      20       0    1016
Permanent Ineff=
       F       F
Bank Sta=-10.335,8.74
XS Rating Curve= 0 ,0
Skew Angle= 15
Exp/Cntr=0.5,0.3

Type RM Length L Ch R = 1 ,69736.32,289.2822,350.3647,257.4523
XS GIS Cut Line= 4
   1496409.72703   1143752.26673   1495989.57251   1143563.15518
   1495774.30906   1143458.86352   1495546.87828   1143681.08629
#Sta/Elev= 30
 -458.82 1024.59 -453.93 1023.84  -439.7 1021.46 -405.62 1018.12  -390.2 1017.97
 -374.79 1015.99 -312.05 1012.54 -269.64 1011.21  -40.71 1008.76  -19.77 1009.08
   -8.92 1007.65   -8.33    1004   -1.84 1004.28     .53 1005.48    4.65 1005.43
    5.51 1005.72    6.78 1007.39   24.07 1009.51   40.04 1009.29   77.52 1011.23
   85.48 1012.35   89.89 1011.91  101.33 1012.54  143.22 1012.25  222.13 1014.99
  245.42 1015.19  256.79 1015.78   265.1 1017.06  332.37 1020.36  559.11 1022.53
#Mann= 5 ,-1,0
 -458.82     .11       0 -453.93     .11       0  -40.71     .13       0
   -8.92    .045       0    6.78      .1       0
#XS Ineff= 2 , 0
       0    -150    1012               0
Permanent Ineff=
       F       F
Bank Sta=-8.92,6.78
XS Rating Curve= 0 ,0
Exp/Cntr=0.3,0.1

Type RM Length L Ch R = 1 ,69385.95,412.9951,515.6531,392.017
BEGIN DESCRIPTION:
TWE_38X
END DESCRIPTION:
XS GIS Cut Line= 4
   1496526.70341   1143251.30709   1496116.98031   1143313.80741
   1496022.39239   1143304.99541   1495448.57612    1143270.4042
#Sta/Elev= 30
 -510.22 1027.25 -433.72 1017.63 -402.95  1011.6 -396.95 1008.28 -388.16 1006.58
 -380.02 1005.94 -372.17 1007.44 -358.29 1005.31 -349.81 1008.41 -331.55 1007.71
  -31.27 1006.76  -20.52 1006.52  -11.27 1004.39   -9.41 1002.22   -8.33 1000.85
   -1.84 1000.78     .53 1001.98    5.51 1002.22   19.68 1004.35   27.51 1006.59
   38.86 1006.07   89.37 1008.64  187.55 1010.57  202.99 1009.79  292.88 1010.76
  350.16 1010.25  398.93 1012.31  442.92 1012.56  462.35 1014.08   574.1 1019.38
#Mann= 6 ,-1,0
 -510.22     .13       0 -331.55     .11       0  -11.27     .14       0
   -9.41     .04       0    5.51     .14       0  462.35      .1       0
#XS Ineff= 2 , 0
         -216.37 1010.34
Permanent Ineff=
       F       F
Bank Sta=-9.41,5.51
XS Rating Curve= 0 ,0
Exp/Cntr=0.3,0.1

Type RM Length L Ch R = 1 ,68870.30,37.21201,44.13676,38.35141
BEGIN DESCRIPTION:
TWE_37USX
END DESCRIPTION:
XS GIS Cut Line= 5
   1496605.63648   1142829.78609   1496012.44554   1142909.22507
   1495987.34022   1142913.22408   1495949.92782   1142918.97867
   1495441.45177   1143181.21161
#Sta/Elev= 30
 -624.06 1044.91 -590.99 1036.89 -527.33 1015.27 -513.55 1012.82 -448.43 1008.25
 -386.77 1006.72 -375.61 1008.41 -362.87 1007.03 -359.26 1005.31 -348.07 1007.41
 -313.08 1005.82 -192.92 1005.77  -23.39 1003.65  -16.28 1001.56  -11.32  999.65
     .04  998.84     8.9  998.99   11.39 1001.64   16.56 1003.86  102.57 1004.48
  155.13 1006.84  209.94 1006.47  315.27 1009.15  359.21 1014.81  372.38 1014.56
  400.66 1017.69  416.89 1017.28  441.87 1019.02  562.18 1021.43  609.81 1022.86
#Mann= 6 ,-1,0
 -624.06     .13       0 -313.08     .11       0  -23.39     .14       0
  -16.28     .05       0   11.39     .14       0  562.18      .1       0
#XS Ineff= 2 , 0
         -339.96 1008.28
Permanent Ineff=
       F       F
Bank Sta=-16.28,11.39
XS Rating Curve= 0 ,0
Exp/Cntr=0.5,0.3

Type RM Length L Ch R = 1 ,68826.16,65.08826,39.57481,37.44172
BEGIN DESCRIPTION:
E. of Midway Rd (US) (TWE_37) - US
END DESCRIPTION:
XS GIS Cut Line= 6
   1496466.19357   1142756.73163   1496075.21063   1142864.33202
   1495983.78248   1142869.49934   1495950.60564   1142876.84711
   1495871.80282   1142945.02034    1495475.3061   1143122.61745
#Sta/Elev= 30
 -492.72 1037.39 -421.55 1022.78 -370.57 1006.94 -346.93 1006.56 -339.29 1003.82
 -325.11  1006.3 -291.34 1005.22 -171.61 1005.25  -81.23  1003.5  -20.62 1003.52
  -16.98 1001.55   -7.64  998.12   -1.79  998.04    4.37   998.3    11.1  1000.7
   14.93 1003.61   28.78 1004.94   34.08 1003.93   88.73 1003.63   267.1 1008.31
  310.74 1008.51  348.14 1011.58  368.21 1016.22  386.01 1017.73  414.64 1017.99
  444.54 1020.38   458.2 1019.84   509.2  1021.6  533.78 1023.52     577 1024.21
#Mann= 4 ,-1,0
 -492.72     .13       0 -291.34     .11       0  -16.98     .05       0
    11.1     .14       0
#XS Ineff= 3 ,-1
  -378.3    -243  1006.3 -133.92  -24.65 1004.01   13.11   27.72  1003.9
Permanent Ineff=
       F       F       F
Bank Sta=-16.98,11.1
XS Rating Curve= 0 ,0
Exp/Cntr=0.5,0.3

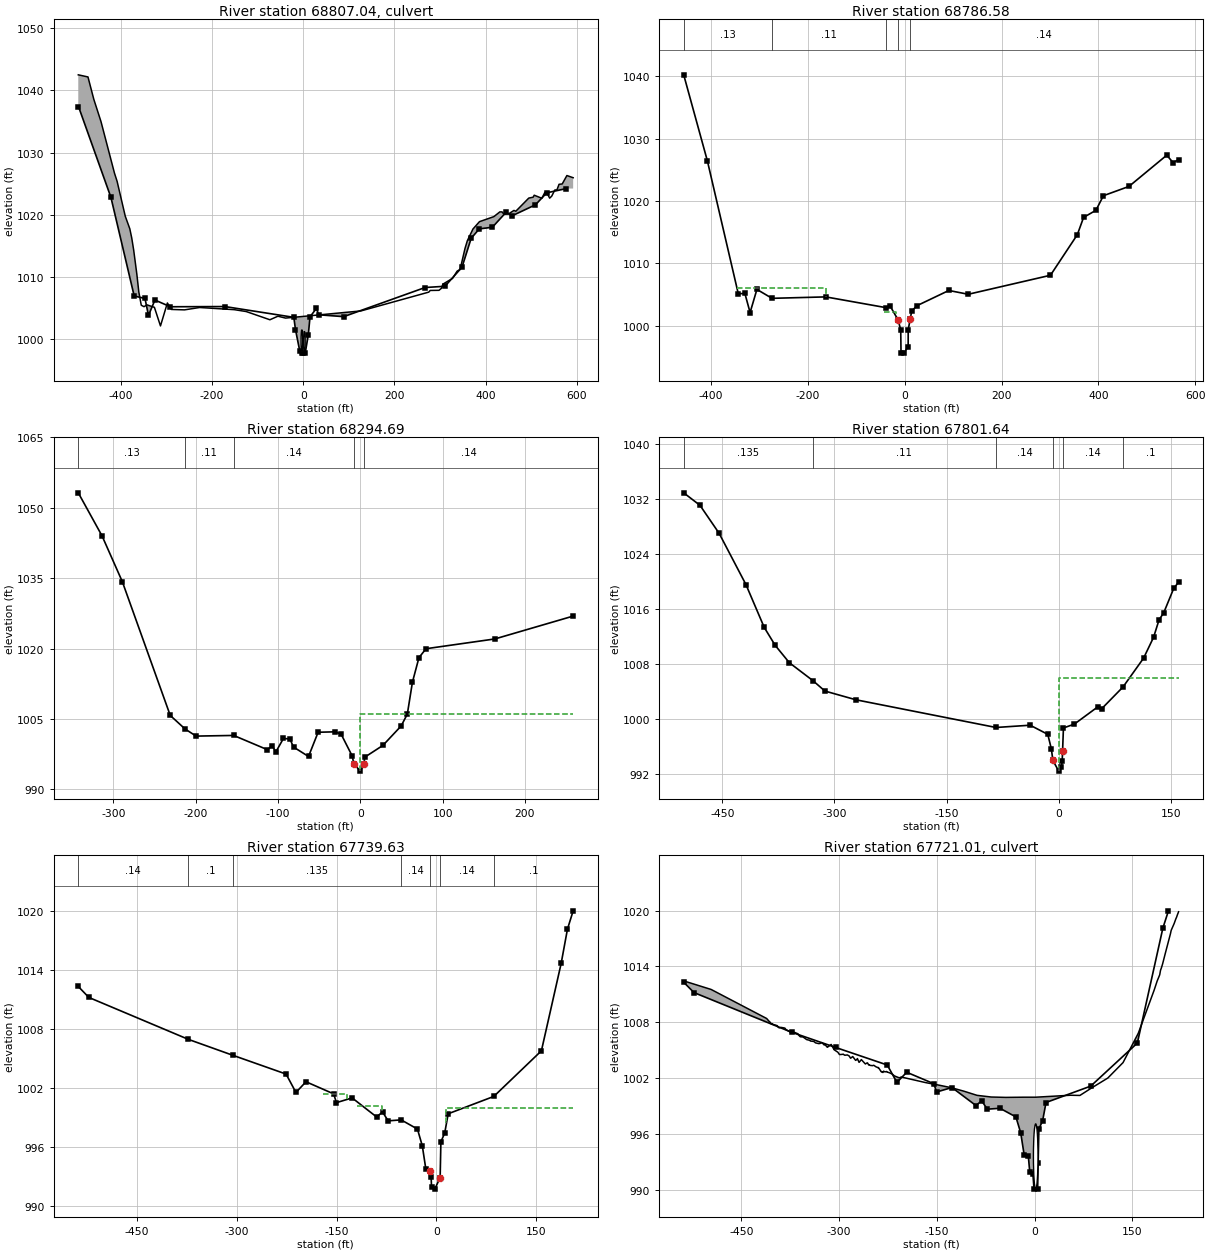
Type RM Length L Ch R = 2 ,68807.04,,,
BEGIN DESCRIPTION:
E. of Midway Rd (US) (TWE_37) - TOR
END DESCRIPTION:
Bridge Culvert--1,0,-1,-1, 0
Deck Dist Width WeirC Skew NumUp NumDn MinLoCord MaxHiCord MaxSubmerge Is_Ogee
4,30.3,2.6,0, 60, 60, 1003.13, , 0.95, 0, 0,0,,
 -493.15 -471.91 -459.16 -443.33 -413.85 -408.05 -390.08 -380.16 -375.93 -371.67
 -364.68 -360.43 -355.05 -348.99 -342.81 -326.28 -312.96 -297.81 -289.21 -260.31
  -227.1 -150.83 -124.96  -73.06  -55.46  -38.79  126.52  275.22  278.44  297.64
  303.05  306.18   327.4  337.42  343.94  354.74  359.74  372.12  386.36  417.91
  431.02  435.91  440.15  451.02  462.03  465.99  494.49  503.97  506.41  523.17
  529.79  534.59  540.27  544.79  551.62   556.2  560.82  567.79  578.05  591.79
 1042.48 1042.14 1038.56 1034.96  1026.7 1025.37 1019.75 1017.74 1016.26 1014.31
  1010.4 1007.59 1005.46 1005.23 1005.53 1005.13 1002.14 1005.83 1004.79 1004.72
  1005.1 1004.75 1004.45 1003.13  1003.7  1003.4 1004.55 1007.57 1007.84 1007.86
 1008.19 1008.85 1009.78 1010.94 1011.22 1014.61 1015.82 1017.71 1018.89  1019.7
 1020.46 1020.46 1020.07 1020.18  1020.7 1020.56 1022.68 1022.82 1023.14 1022.65
  1023.6 1023.46 1022.67 1022.99 1023.98 1023.99 1024.89 1024.95  1026.3 1025.95
                                                                                
                                                                                
                                                                                
                                                                                
                                                                                
                                                                                
 -473.15 -459.16 -443.33 -413.85 -408.05 -390.08 -380.16 -375.93 -371.67 -364.68
 -360.43 -355.05 -348.99 -342.81 -326.28 -312.96 -297.81 -289.21 -260.31  -227.1
 -150.83 -124.96  -73.06  -55.46  -38.79  126.52   270.4  275.22  278.44  297.64
  303.05  306.18   327.4  337.42  343.94  354.74  359.74  372.12  386.36  417.91
  431.02  435.91  440.15  451.02  462.03  465.99  494.49  503.97  506.41  523.17
  529.79  534.59  540.27  544.79  551.62   556.2  560.82  567.79  578.05  591.79
 1042.48 1038.56 1034.96  1026.7 1025.37 1019.75 1017.74 1016.26 1014.31  1010.4
 1007.59 1005.46 1005.23 1005.53 1005.13 1002.14 1005.83 1004.79 1004.72  1005.1
 1004.75 1004.45 1003.13  1003.7  1003.4 1004.55 1007.68 1007.57 1007.84 1007.86
 1008.19 1008.85 1009.78 1010.94 1011.22 1014.61 1015.82 1017.71 1018.89  1019.7
 1020.46 1020.46 1020.07 1020.18  1020.7 1020.56 1022.68 1022.82 1023.14 1022.65
  1023.6 1023.46 1022.67 1022.99 1023.98 1023.99 1024.89 1024.95  1026.3 1025.95
                                                                                
                                                                                
                                                                                
                                                                                
                                                                                
                                                                                
BR Coef=-1 , 1 , 0 ,, 0 ,,,0.8,0,,0,
WSPro=,,,, 1 ,,,, 0 ,,,, 0 ,,,,-1 ,-1 ,-1 , 0 , 0 , 0 , 0 , 0
Culvert=1,3.5,,30.3,0.024,0.9,1,2,3,998.03,-3,997.89,-3,Culvert #2  , 0 ,4
      -3      -3
BC Culvert Barrel=1,,0
Culvert Bottom n=0.024
Culvert=1,3.5,,30.3,0.024,0.9,1,2,3,997.78,2.5,997.75,2.5,Culvert #3  , 0 ,4
     2.5     2.5
BC Culvert Barrel=1,,0
Culvert Bottom n=0.024
BR U #Sta/Elev= 30
 -492.72 1037.39 -421.55 1022.78 -370.57 1006.94 -346.93 1006.56 -339.29 1003.82
 -325.11  1006.3 -291.34 1005.22 -171.61 1005.25  -20.62 1003.52  -16.98 1001.55
   -7.64  998.12   -1.79  997.77     .14  997.77    4.37  997.77    11.1  1000.7
   14.93 1003.61   28.78 1004.94   34.08 1003.93   88.73 1003.63   267.1 1008.31
  310.74 1008.51  348.14 1011.58  368.21 1016.22  386.01 1017.73  414.64 1017.99
  444.54 1020.38   458.2 1019.84   509.2  1021.6  533.78 1023.52     577 1024.21
BR U #Mann= 4
 -492.72     .13 -291.34     .11  -16.98    .045    11.1     .14
BC Design=,, 0 ,, 0 ,,,,,,
BC Use User HTab Curves=0
BC User HTab FreeFlow(D)= 0

Type RM Length L Ch R = 1 ,68786.58,419.7679,491.8906,444.9928
BEGIN DESCRIPTION:
E. of Midway Rd (US) (TWE_37) - DS
END DESCRIPTION:
XS GIS Cut Line= 5
   1496410.20374   1142683.81496   1495972.06332   1142833.04101
   1495896.19291   1142871.40584   1495842.32448   1142920.92126
    1495466.1916   1143061.41962
#Sta/Elev= 30
 -456.67 1040.23 -407.77 1026.43 -343.88 1005.11  -330.3 1005.17 -319.49  1002.1
 -305.43 1005.81 -274.16 1004.38 -163.11 1004.61  -38.25 1002.88  -29.71 1003.09
  -13.58  1000.9   -8.22   999.3   -7.64  995.67   -1.79  995.59    7.14  996.63
    7.21  999.34   11.26 1001.01   14.39 1002.34   25.58 1003.21   91.21 1005.64
  131.26 1005.03  301.16 1008.08  356.67 1014.59  369.59 1017.36  395.13  1018.5
  410.56 1020.84  463.38 1022.33  541.46 1027.34  554.53 1026.15  565.89 1026.63
#Mann= 5 ,-1,0
 -456.67     .13       0 -274.16     .11       0  -38.25     .14       0
  -13.58     .05       0   11.26     .14       0
#XS Ineff= 3 ,-1
 -347.53 -163.11    1006   -42.3  -18.11 1002.14   16.36   34.381002.115
Permanent Ineff=
       F       F       F
Bank Sta=-13.58,11.26
XS Rating Curve= 0 ,0
Exp/Cntr=0.5,0.3

Type RM Length L Ch R = 1 ,68294.69,365.8345,493.0584,410.2743
XS GIS Cut Line= 3
   1496244.79626   1142323.44455    1495916.6706   1142406.77789
   1495663.19783   1142476.22277
#Sta/Elev= 30
 -342.78 1053.18 -313.88    1044 -289.24 1034.25 -231.04 1005.77 -213.05 1002.89
 -199.63 1001.37 -153.92 1001.51 -113.07  998.48 -107.03   999.3  -102.7  997.99
  -93.47 1000.88  -85.58 1000.74  -81.25  999.04  -63.02  997.03  -51.34 1002.19
  -31.01 1002.28  -23.47 1001.81   -9.91  997.13   -7.92  995.48    -.15  993.91
    4.56  995.39    5.07  996.85    27.4  999.39   49.52 1003.52   57.07 1006.06
   63.27 1012.86    71.2 1018.09   79.82 1019.98  163.41 1022.06  258.58 1026.93
#Mann= 5 ,-1,0
 -342.78     .13       0 -213.05     .11       0 -153.92     .14       0
   -7.92     .05       0    4.56     .14       0
#XS Ineff= 2 , 0
       0  -89.04 1006.07               0
Permanent Ineff=
       F       F
Bank Sta=-7.92,4.56
XS Rating Curve= 0 ,0
Exp/Cntr=0.3,0.1

Type RM Length L Ch R = 1 ,67801.64,77.53092,62.01023,57.99741
BEGIN DESCRIPTION:
TWE_36USX
END DESCRIPTION:
XS GIS Cut Line= 3
    1496275.6122   1142009.64206   1495775.63156   1142048.13386
   1495616.32251   1142065.45801
#Sta/Elev= 30
 -501.53  1032.9 -479.75 1031.08 -454.17 1027.01 -418.34 1019.56 -393.86 1013.32
 -379.23 1010.71 -360.25 1008.18 -328.83 1005.58  -312.7 1004.06 -271.27 1002.79
  -83.96  998.76  -38.26  999.09  -14.71  997.76   -9.91  995.63   -7.92  993.98
    -.15  992.41    3.54  993.05    4.56  993.89    5.07  995.35    6.22  998.69
   20.81  999.25   52.26 1001.77   57.21 1001.47   85.93 1004.66   113.4 1008.85
  126.69 1011.87  134.07 1014.42  140.36 1015.46  153.65 1018.99  160.18 1019.91
#Mann= 6 ,-1,0
 -501.53    .135       0 -328.83     .11       0  -83.96     .14       0
   -7.92     .04       0    5.07     .14       0   85.93      .1       0
#XS Ineff= 2 , 0
       0 -163.31    1006               0
Permanent Ineff=
       F       F
Bank Sta=-7.92,5.07
XS Rating Curve= 0 ,0
Exp/Cntr=0.5,0.3

Type RM Length L Ch R = 1 ,67739.63,31.78791,36.5445,34.36387
BEGIN DESCRIPTION:
E. of Midway Rd (TWE_36) - US
END DESCRIPTION:
XS GIS Cut Line= 4
    1496301.3189   1141833.89272   1495892.33169    1141956.3353
   1495785.55807   1141987.40879   1495582.21621   1142019.05479
#Sta/Elev= 30
 -538.45 1012.29 -522.61 1011.18 -372.89 1006.92 -305.46 1005.29 -226.08  1003.4
 -211.26 1001.53 -196.19 1002.62 -154.62 1001.39 -150.36  1000.5 -126.79 1000.98
   -89.9  999.04  -81.14  999.56  -72.64  998.65  -53.14  998.75  -28.64  997.82
  -21.29  996.11  -16.03  993.77   -9.58  993.59   -8.08  992.98   -7.44  991.94
   -2.56  991.72    5.51   992.9    6.63  996.53   12.33   997.4   17.59  999.37
   86.17 1001.13  157.73 1005.76  187.41 1014.63  196.88 1018.11  205.46 1019.97
#Mann= 7 ,-1,0
 -538.45     .14       0 -372.89      .1       0 -305.46    .135       0
  -53.14     .14       0   -9.58     .04       0    5.51     .14       0
   86.17      .1       0
#XS Ineff= 3 ,-1
 -170.37 -133.85 1001.37 -119.03  -82.13 1000.12      15  205.46    1000
Permanent Ineff=
       F       F       F
Bank Sta=-9.58,5.51
XS Rating Curve= 0 ,0
Exp/Cntr=0.5,0.3

Type RM Length L Ch R = 2 ,67721.01,,,
BEGIN DESCRIPTION:
E. of Midway Rd (TWE_36) - TOR
END DESCRIPTION:
Bridge Culvert--1,0,-1,-1, 0
Deck Dist Width WeirC Skew NumUp NumDn MinLoCord MaxHiCord MaxSubmerge Is_Ogee
6,25,2.6,0, 152, 152, 999.94, , 0.95, 0, 0,0,,
    -538 -496.37 -411.19 -407.24  -407.2 -406.95 -406.71 -405.54 -403.69 -402.78
 -402.41 -402.09 -398.69 -395.08 -394.95 -393.61    -393 -391.76 -388.86 -383.43
 -383.02 -381.47 -375.95 -373.95 -368.69  -368.6 -368.54 -364.64 -363.35 -363.33
 -363.31 -360.83 -359.57 -356.95 -355.72 -350.93 -349.88 -349.71 -344.81 -344.22
 -342.83 -339.67 -338.71 -336.79 -336.21 -332.37 -331.45 -329.21 -327.54 -327.08
  -326.2 -322.84  -321.5 -319.06 -317.89 -312.25 -312.12  -312.1 -310.22 -307.61
  -307.6 -307.57 -302.17 -301.84 -299.58 -299.17 -295.51 -293.59 -293.47 -293.16
 -291.17 -287.19 -284.21 -283.08 -282.28 -279.08 -276.01 -274.62 -272.81 -271.89
 -269.91 -269.38 -269.07 -265.87 -259.88 -259.74 -259.67  -256.9 -256.57 -256.04
  -254.6 -253.68 -252.38 -248.83  -246.8 -243.24 -241.32 -240.22 -239.63 -238.77
 -235.15 -234.89 -233.22 -232.72 -231.69 -229.64 -227.01 -226.19 -225.53 -222.57
 -220.95 -219.61 -218.53 -215.12  -207.7 -204.57 -167.31 -147.75 -127.58 -108.64
  -88.32  -77.24   -66.6  -44.16  -23.79  -16.34    1.28    1.74      55   69.58
   88.33  112.42  135.79  159.23  183.48  188.16  192.04   193.3  194.75  196.55
   200.3  208.58  209.62  210.14  213.13  213.56  214.26  216.71   218.2  218.82
  220.67  221.01
 1012.43 1011.52  1008.4 1008.07 1008.06 1008.06 1008.05 1007.98 1007.78 1007.85
 1007.83 1007.78 1007.71 1007.63 1007.63 1007.48 1007.43  1007.4 1007.44 1007.37
 1007.35  1007.2 1006.99 1006.88 1006.92 1006.92 1006.91  1006.8 1006.76 1006.76
 1006.76 1006.52 1006.44 1006.42 1006.43 1006.18 1006.14 1006.13 1006.05 1005.98
 1005.97 1005.94 1005.93 1005.82 1005.78 1005.71  1005.7 1005.71  1005.8 1005.79
  1005.8 1005.55 1005.63 1005.37 1005.31  1005.6 1005.61 1005.61 1005.37 1005.05
 1005.04 1005.04 1004.79 1004.77 1004.54 1004.52 1004.54 1004.57 1004.56 1004.53
 1004.45 1004.48 1004.35  1004.2 1004.13 1004.31 1004.04  1003.9 1003.98 1004.09
 1003.75 1003.69  1003.7 1003.98 1003.52 1003.52 1003.51 1003.63 1003.63 1003.59
  1003.4 1003.43 1003.36 1003.33 1003.37  1003.2 1003.15  1003.1 1003.13 1003.04
 1002.66 1002.69 1002.63 1002.59 1002.74 1002.66  1002.7 1002.62 1002.63 1002.56
  1002.5 1002.46 1002.43 1002.23 1002.02 1002.11 1001.51 1001.25 1000.96 1000.59
 1000.14 1000.05  999.96  999.92  999.94  999.94  999.94  999.94 1000.15 1000.13
 1000.97    1002 1003.66 1006.82 1011.44 1012.43 1013.09 1013.58 1013.86 1014.28
 1015.31 1017.52 1017.86 1017.95 1018.42  1018.5 1018.61 1019.09 1019.33 1019.47
  1019.8 1019.87
                                                                                
                                                                                
                                                                                
                                                                                
                                                                                
                                                                                
                                                                                
                                                                                
                                                                                
                                                                                
                                                                                
                                                                                
                                                                                
                                                                                
                                                                                
                
    -538 -496.37 -411.19 -407.24  -407.2 -406.95 -406.71 -405.54 -403.69 -402.78
 -402.41 -402.09 -398.69 -395.08 -394.95 -393.61    -393 -391.76 -388.86 -383.43
 -383.02 -381.47 -375.95 -373.95 -368.69  -368.6 -368.54 -364.64 -363.35 -363.33
 -363.31 -360.83 -359.57 -356.95 -355.72 -350.93 -349.88 -349.71 -344.81 -344.22
 -342.83 -339.67 -338.71 -336.79 -336.21 -332.37 -331.45 -329.21 -327.54 -327.08
  -326.2 -322.84  -321.5 -319.06 -317.89 -312.25 -312.12  -312.1 -310.22 -307.61
  -307.6 -307.57 -302.17 -301.84 -299.58 -299.17 -295.51 -293.59 -293.47 -293.16
 -291.17 -287.19 -284.21 -283.08 -282.28 -279.08 -276.01 -274.62 -272.81 -271.89
 -269.91 -269.38 -269.07 -265.87 -259.88 -259.74 -259.67  -256.9 -256.57 -256.04
  -254.6 -253.68 -252.38 -248.83  -246.8 -243.24 -241.32 -240.22 -239.63 -238.77
 -235.15 -234.89 -233.22 -232.72 -231.69 -229.64 -227.01 -226.19 -225.53 -222.57
 -220.95 -219.61 -218.53 -215.12  -207.7 -204.57 -167.31 -147.75 -127.58 -108.64
  -88.32  -77.24   -66.6  -44.16  -23.79  -16.34    1.28    1.74      55   69.58
   88.33  112.42  135.79  159.23  183.48  188.16  192.04   193.3  194.75  196.55
   200.3  208.58  209.62  210.14  213.13  213.56  214.26  216.71   218.2  218.82
  220.67  221.01
 1012.43 1011.52  1008.4 1008.07 1008.06 1008.06 1008.05 1007.98 1007.78 1007.85
 1007.83 1007.78 1007.71 1007.63 1007.63 1007.48 1007.43  1007.4 1007.44 1007.37
 1007.35  1007.2 1006.99 1006.88 1006.92 1006.92 1006.91  1006.8 1006.76 1006.76
 1006.76 1006.52 1006.44 1006.42 1006.43 1006.18 1006.14 1006.13 1006.05 1005.98
 1005.97 1005.94 1005.93 1005.82 1005.78 1005.71  1005.7 1005.71  1005.8 1005.79
  1005.8 1005.55 1005.63 1005.37 1005.31  1005.6 1005.61 1005.61 1005.37 1005.05
 1005.04 1005.04 1004.79 1004.77 1004.54 1004.52 1004.54 1004.57 1004.56 1004.53
 1004.45 1004.48 1004.35  1004.2 1004.13 1004.31 1004.04  1003.9 1003.98 1004.09
 1003.75 1003.69  1003.7 1003.98 1003.52 1003.52 1003.51 1003.63 1003.63 1003.59
  1003.4 1003.43 1003.36 1003.33 1003.37  1003.2 1003.15  1003.1 1003.13 1003.04
 1002.66 1002.69 1002.63 1002.59 1002.74 1002.66  1002.7 1002.62 1002.63 1002.56
  1002.5 1002.46 1002.43 1002.23 1002.02 1002.11 1001.51 1001.25 1000.96 1000.59
 1000.14 1000.05  999.96  999.92  999.94  999.94  999.94  999.94 1000.15 1000.13
 1000.97    1002 1003.66 1006.82 1011.44 1012.43 1013.09 1013.58 1013.86 1014.28
 1015.31 1017.52 1017.86 1017.95 1018.42  1018.5 1018.61 1019.09 1019.33 1019.47
  1019.8 1019.87
                                                                                
                                                                                
                                                                                
                                                                                
                                                                                
                                                                                
                                                                                
                                                                                
                                                                                
                                                                                
                                                                                
                                                                                
                                                                                
                                                                                
                                                                                
                
BR Coef=-1 , 1 , 0 ,, 0 ,,,0.8,0,,0,
WSPro=,,,, 1 ,,,, 0 ,,,, 0 ,,,,-1 ,-1 ,-1 , 0 , 0 , 0 , 0 , 0
Culvert=1,7,,25,0.024,0.9,1,2,3,990.07,1.74,989.75,1.74,Culvert #1  , 0 ,6
    1.74    1.74
BC Culvert Barrel=1,,0
Culvert Bottom n=0.024
BR U #Sta/Elev= 30
 -538.45 1012.29 -522.61 1011.18 -372.89 1006.92 -305.46 1005.29 -226.08  1003.4
 -211.26 1001.53 -196.19 1002.62 -154.62 1001.39 -150.36  1000.5 -126.79 1000.98
   -89.9  999.04  -81.14  999.56  -72.64  998.65  -53.14  998.75  -28.64  997.82
  -21.29  996.11  -16.03  993.77   -9.58  993.59   -7.44  991.94   -2.56  991.72
    -.83  990.06    4.71  990.06    5.51   992.9    6.63  996.53   12.33   997.4
   17.59  999.37   86.17 1001.13  157.73 1005.76  196.88 1018.11  205.46 1019.97
BR U #Mann= 7
 -538.45     .14 -372.89     .08 -305.46    .135  -53.14     .14   -9.58    .045
    5.51     .14   86.17     .08
BR D #Sta/Elev= 30
 -503.05 1013.52 -432.55 1009.48 -376.08 1007.83 -355.02 1006.49 -292.78 1005.04
 -208.27 1002.22 -135.18 1000.83  -97.39  999.45   -43.4  999.28  -30.37  998.76
  -18.43  998.92  -11.04  995.51  -10.05  995.51   -8.08  992.44   -7.44   991.4
   -2.56  991.18     .12  989.74    4.71   990.1    5.51  992.36    7.81  993.64
   16.69  995.61   20.69  997.21   22.65  996.87   29.01  998.73   69.27   999.8
  105.15 1000.71  150.42 1004.13   185.4 1009.21   205.3 1013.21  221.05  1017.4
BR D #Mann= 6
 -503.05     .14 -355.02     .08   -43.4     .14   -8.08    .045    5.51     .14
   69.27     .08
BC Design=,, 0 ,, 0 ,,,,,,
BC Use User HTab Curves=0
BC User HTab FreeFlow(D)= 0

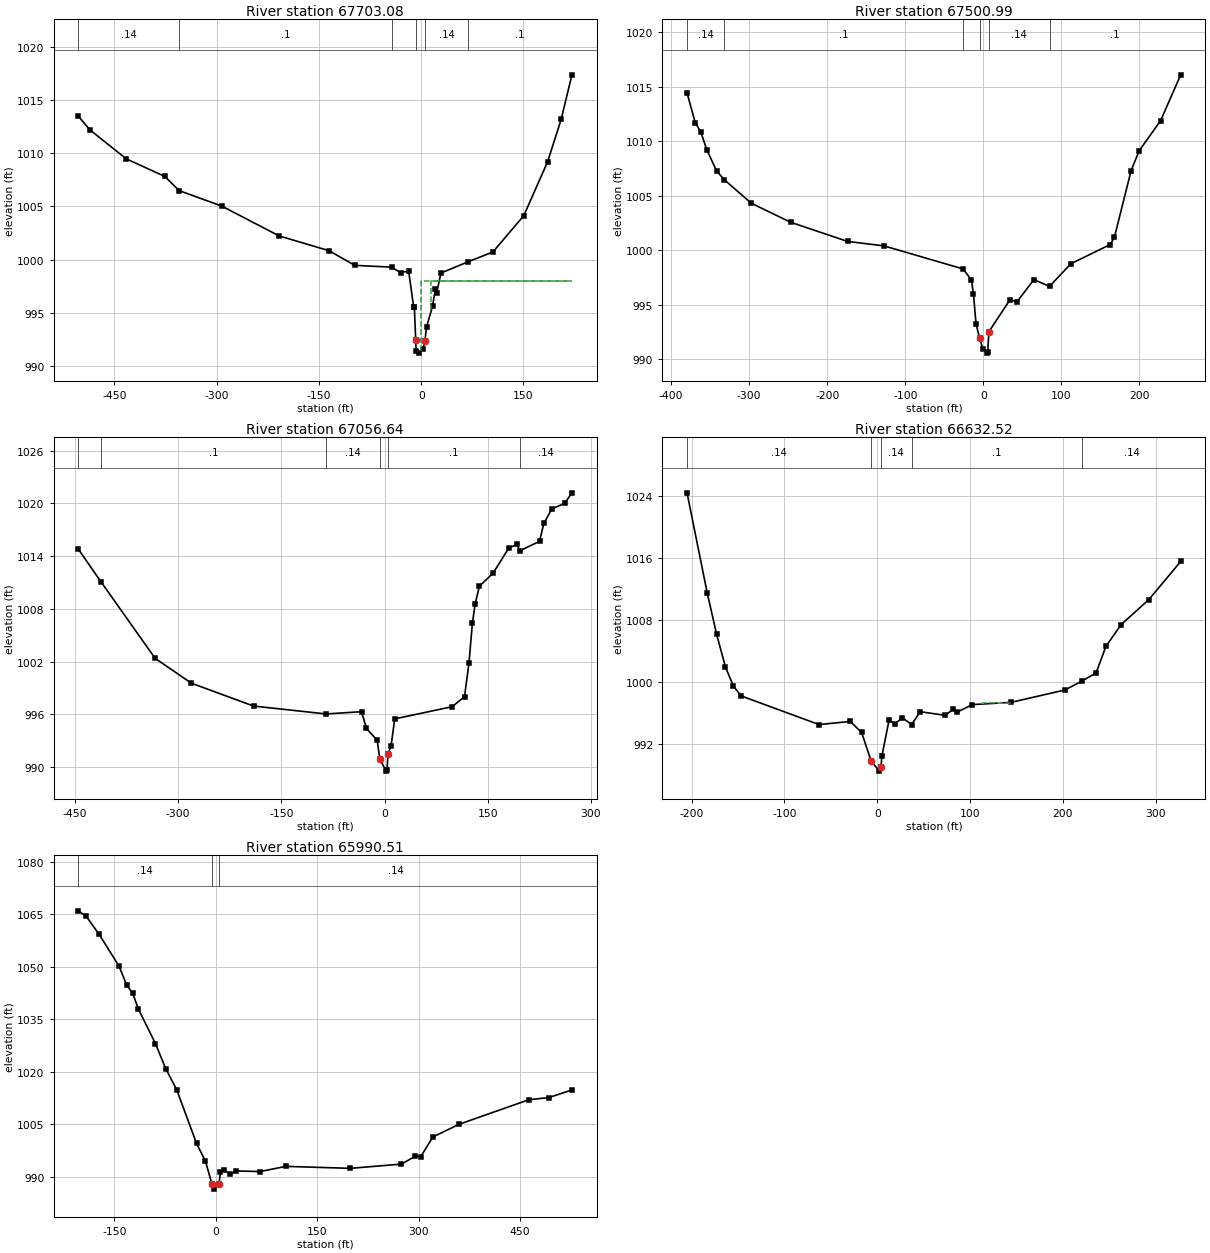
Type RM Length L Ch R = 1 ,67703.08,180.2184,202.094,165.4561
BEGIN DESCRIPTION:
E. of Midway Rd (TWE_36) - DS
END DESCRIPTION:
XS GIS Cut Line= 5
   1496274.38615   1141812.34613   1495885.20899   1141926.81004
   1495789.59777   1141951.72277   1495728.99934   1141961.82251
   1495573.46325   1141990.77559
#Sta/Elev= 30
 -503.05 1013.52 -486.03 1012.22 -432.55 1009.48 -376.08 1007.83 -355.02 1006.49
 -292.78 1005.04 -208.27 1002.22 -135.18 1000.83  -97.39  999.45   -43.4  999.28
  -30.37  998.76  -18.43  998.92  -11.04  995.51  -10.05  995.51   -8.08  992.44
   -7.44   991.4   -2.56  991.18    2.63  991.57    5.51  992.36    7.81  993.64
   16.69  995.61   20.69  997.21   22.65  996.87   29.01  998.73   69.27   999.8
  105.15 1000.71  150.42 1004.13   185.4 1009.21   205.3 1013.21  221.05  1017.4
#Mann= 6 ,-1,0
 -503.05     .14       0 -355.02      .1       0   -43.4     .14       0
   -8.08     .04       0    5.51     .14       0   69.27      .1       0
#XS Ineff= 2 , 0
       0     -20     998      15       0     998
Permanent Ineff=
       F       F
Bank Sta=-8.08,5.51
XS Rating Curve= 0 ,0
Exp/Cntr=0.5,0.3

Type RM Length L Ch R = 1 ,67500.99,292.445,444.347,343.7893
XS GIS Cut Line= 3
   1496125.65879   1141632.59547   1495774.25197   1141773.15814
   1495537.77592   1141865.76444
#Sta/Elev= 30
 -379.56 1014.44 -369.14 1011.72 -362.02 1010.87 -354.33 1009.23 -341.66 1007.27
 -331.89 1006.47 -297.33 1004.31 -246.84 1002.56 -173.95  1000.8 -127.27 1000.39
  -25.82  998.27   -15.2  997.24  -12.68     996   -9.34  993.23   -4.79  991.92
-.849999  990.96    4.19  990.54    5.65  990.64    7.07   992.5   34.15  995.44
    43.2  995.26   64.77  997.29   84.79  996.67  112.12  998.75  162.42 1000.51
  167.88 1001.17  189.29  1007.3   199.6 1009.12  227.13  1011.9  252.88  1016.1
#Mann= 6 ,-1,0
 -379.56     .14       0 -331.89      .1       0  -25.82     .14       0
   -4.79     .04       0    7.07     .14       0   84.79      .1       0
Bank Sta=-4.79,7.07
XS Rating Curve= 0 ,0
Exp/Cntr=0.3,0.1

Type RM Length L Ch R = 1 ,67056.64,396.0011,424.119,307.9694
XS GIS Cut Line= 3
   1496075.30807   1141470.36122   1495630.86253   1141482.51378
   1495358.29265   1141492.93077
#Sta/Elev= 30
 -445.06  1014.8 -411.89 1011.06 -333.23 1002.36 -280.59  999.54 -190.31  996.94
     -85996.0433  -33.28   996.3  -26.34   994.4  -10.67  993.05   -6.79  990.92
    2.19  989.54    3.65  989.64    5.07   991.5    9.61  992.45    14.8  995.48
   98.38  996.87  116.26  998.01  122.78 1001.87  127.69 1006.38  131.66 1008.52
   137.9 1010.58  157.66 1012.04  180.48  1014.9  192.41 1015.33  196.431014.597
  225.25 1015.67  231.48 1017.71  243.06 1019.35  261.82    1020  272.32 1021.19
#Mann= 6 ,-1,0
 -445.06     .14       0 -411.89      .1       0     -85     .14       0
   -6.79     .04       0    5.07      .1       0  196.43     .14       0
Bank Sta=-6.79,5.07
XS Rating Curve= 0 ,0
Exp/Cntr=0.3,0.1

Type RM Length L Ch R = 1 ,66632.52,607.0123,642.0161,582.5013
BEGIN DESCRIPTION:
TWE_35X
END DESCRIPTION:
XS GIS Cut Line= 5
   1495705.55545   1141036.35564    1495595.7372   1141105.04823
   1495544.21752   1141136.68307   1495531.21293   1141143.86713
   1495285.37566      1141359.25
#Sta/Elev= 30
 -204.82 1024.47 -183.14 1011.57 -172.98 1006.22 -163.42 1001.96 -154.94  999.55
 -146.76  998.26  -62.64  994.55  -29.07  994.96   -16.8  993.53   -6.67  989.89
    2.19  988.54    4.01  989.11    5.07   990.5   12.77  995.13   19.04  994.65
   27.19  995.43   36.97  994.55   46.38  996.21   73.38  995.74   81.94  996.56
   85.81  996.15   102.5  997.13  144.28  997.42   202.2  999.02  220.65 1000.18
   235.7 1001.21  246.27 1004.64  262.63 1007.45  292.45 1010.68  326.87 1015.61
#Mann= 5 ,-1,0
 -204.82     .14       0   -6.67     .04       0    4.01     .14       0
   36.97      .1       0  220.65     .14       0
#XS Ineff= 1 ,-1
  112.99  145.25  997.31
Permanent Ineff=
       F
Bank Sta=-6.67,4.01
XS Rating Curve= 0 ,0
Exp/Cntr=0.3,0.1

Type RM Length L Ch R = 1 ,65990.51,456.5038,544.0231,484.8703
XS GIS Cut Line= 3
   1495230.22933   1140598.73163   1495096.54823    1140748.0374
   1494747.58924    1141147.3435
#Sta/Elev= 30
 -203.64 1065.92 -191.97 1064.39 -173.22 1059.35 -143.25 1050.12  -132.1 1044.78
    -123 1042.34 -114.68 1037.88   -89.3 1027.98  -74.06 1020.79  -57.99 1014.85
  -28.56  999.48  -15.54   994.5   -5.62  987.84   -2.86  986.41    4.88   987.9
    6.82  991.28   11.83  991.91   21.62  990.61   30.11  991.61   65.59  991.43
  103.58  992.91  199.24  992.35  274.77  993.56  295.12  995.81  303.39   995.7
  321.18  1001.3  359.83 1004.92  463.44 1011.96  492.71 1012.56  527.07 1014.74
#Mann= 3 ,-1,0
 -203.64     .14       0   -5.62     .04       0    4.88     .14       0
Bank Sta=-5.62,4.88
XS Rating Curve= 0 ,0
Exp/Cntr=0.3,0.1