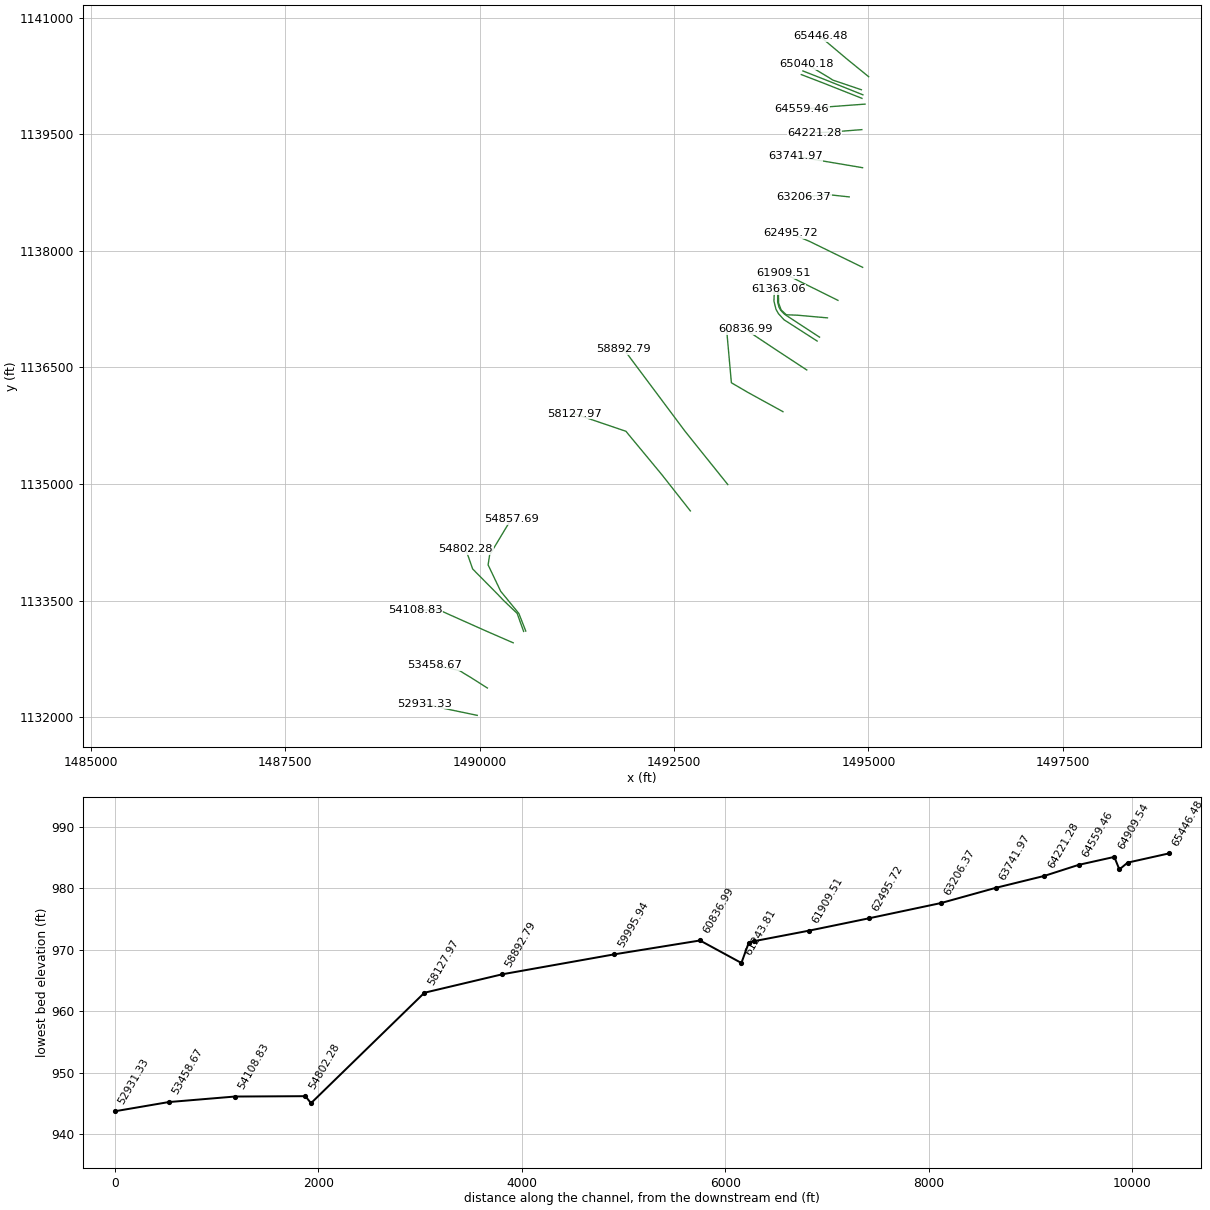
HEC-RAS study 12mile_Combined.prj: 12mile Creek Combined Model

--- 12mile_Combined.g01 (geometry) --- (continued)

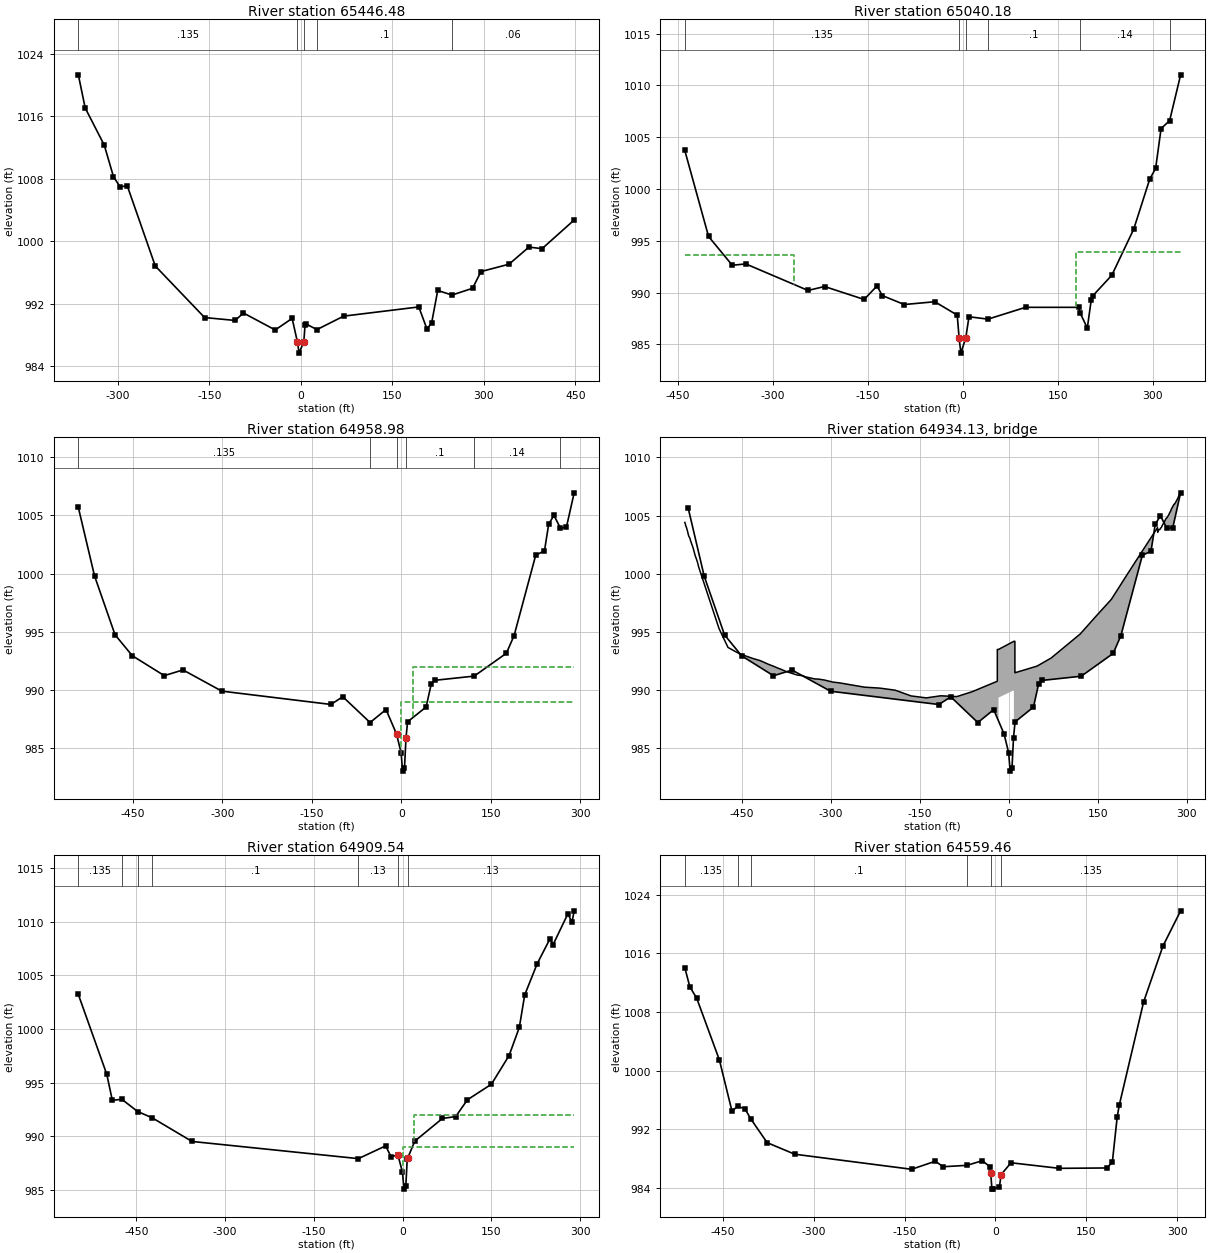
Type RM Length L Ch R = 1 ,65446.48,304.5831,406.3046,353.6302
XS GIS Cut Line= 3
   1495002.60171   1140238.58005   1494720.80873   1140467.92552
   1494376.79035   1140757.71916
#Sta/Elev= 30
 -364.93 1021.33 -353.67 1017.08 -322.36 1012.31 -307.28 1008.27 -296.23 1006.95
 -284.79 1007.13 -238.77  996.83 -157.87  990.22 -108.02  989.85  -94.08   990.8
  -42.05  988.63  -14.31  990.11   -5.62  987.09   -2.86  985.66    4.88  987.15
    6.89  989.28    8.27  989.41   26.38988.6756   70.12   990.4  193.44  991.58
  206.65  988.78  214.36  989.49  224.46  993.69  247.88993.1054  281.65  993.97
  295.35  996.11  341.46  997.06  373.99  999.25  395.62  999.05  448.21 1002.72
#Mann= 5 ,-1,0
 -364.93    .135       0   -5.62     .04       0    4.88     .13       0
   26.38      .1       0  247.88     .06       0
Bank Sta=-5.62,4.88
XS Rating Curve= 0 ,0
Exp/Cntr=0.3,0.1

Type RM Length L Ch R = 1 ,65040.18,35.51299,81.20195,61.46384
BEGIN DESCRIPTION:
TWE_34USX
END DESCRIPTION:
XS GIS Cut Line= 4
   1494908.63911   1140071.05282   1494541.28051    1140195.3481
   1494498.83563   1140223.13156   1494204.29757   1140400.56759
#Sta/Elev= 30
 -438.52 1003.72 -401.03  995.42 -363.64  992.64 -342.29  992.77 -244.04  990.21
    -218  990.59 -155.56  989.34 -135.13  990.65 -127.08  989.72  -92.17  988.85
  -44.01  989.12   -8.64  987.83   -5.62  985.59   -2.86  984.16    4.88  985.65
    9.92  987.67   39.94  987.44   99.12  988.58  182.89  988.58  185.38  988.03
  196.63  986.58  202.87  989.31  205.73  989.72  235.33  991.68  269.95  996.14
  295.21 1000.97  304.43 1001.98  313.04 1005.83  326.54  1006.6  343.89 1011.02
#Mann= 6 ,-1,0
 -438.52    .135       0   -5.62     .04       0    4.88     .13       0
   39.94      .1       0  185.38     .14       0  326.54      .1       0
#XS Ineff= 2 , 0
         -265.47  993.63   178.9          993.91
Permanent Ineff=
       F       F
Bank Sta=-5.62,4.88
XS Rating Curve= 0 ,0
Exp/Cntr=0.5,0.3

Type RM Length L Ch R = 1 ,64958.98,48.1625,49.4349,49.77205
BEGIN DESCRIPTION:
Tater Hill Mountain Rd (TWE_34) - US
END DESCRIPTION:
XS GIS Cut Line= 3
   1494928.16207   1140005.96654     1494427.646   1140206.32808
   1494156.11417   1140313.08399
#Sta/Elev= 30
 -541.18 1005.67 -514.07   999.8 -479.72  994.75 -450.79  992.95 -397.13  991.24
 -365.78  991.73 -300.71  989.91 -117.99  988.77  -97.96  989.43   -52.3  987.22
  -25.54  988.33   -7.99  986.24    -.26  984.62    2.21  983.05    5.39  983.32
    7.94  985.93   10.58  987.28   41.61  988.55   50.38  990.56    56.2  990.84
  122.18   991.2  176.14  993.16  189.09  994.68  225.34 1001.58  239.97 1001.94
  247.04 1004.24  255.82 1004.98  266.81 1003.89  276.66 1003.95  289.72 1006.92
#Mann= 6 ,-1,0
 -541.18    .135       0   -52.3      .1       0   -7.99     .04       0
    7.94      .1       0  122.18     .14       0  266.81      .1       0
#XS Ineff= 2 , 0
       0     -30     989      20       0     992
Permanent Ineff=
       F       F
Bank Sta=-7.99,7.94
XS Rating Curve= 0 ,0
Exp/Cntr=0.5,0.3

Type RM Length L Ch R = 3 ,64934.13,,,
BEGIN DESCRIPTION:
Tater Hill Mountain Rd (TWE_34) - TOR
END DESCRIPTION:
Bridge Culvert--1,0,-1,-1, 0
Deck Dist Width WeirC Skew NumUp NumDn MinLoCord MaxHiCord MaxSubmerge Is_Ogee
11.15,27.4,2.6,0, 96, 96, 989.34, , 0.95, 0, 0,0,,
 -546.76 -545.95  -545.1 -544.55 -544.05 -542.39  -540.6 -539.85 -538.13 -537.16
 -535.26 -532.87 -529.52 -529.28 -527.52 -525.34 -523.28    -489 -473.84 -454.19
 -430.41 -427.48 -419.64 -413.23 -406.36 -397.13 -389.85 -385.12 -375.47 -356.87
 -347.12 -343.48  -334.6 -327.55 -320.63 -310.81 -297.34 -285.71 -243.43  -217.8
 -191.58    -165 -139.38 -114.76  -87.68  -61.89  -19.41  -19.41  -17.41  -17.41
    8.57    8.57   10.27   10.27   10.55   47.67   71.34   89.86   120.5  146.19
  172.99  199.51  207.88  226.01  250.95  251.15  253.29  253.59  254.64  255.29
  256.14  257.54  259.25  261.16  262.55  264.78  265.26  266.61  269.54  271.23
   273.1  273.44  273.94  276.27  276.34   276.4  278.63  279.39  280.85  283.71
  284.18  286.24  287.66  288.87  289.67  289.92
 1004.41 1004.29 1004.11 1004.07 1003.99  1003.7 1003.32 1003.21 1003.05 1002.86
 1002.58 1002.24 1001.61 1001.56 1001.32 1000.99 1000.57  995.29  993.67  993.12
   992.7  992.66  992.54   992.4  992.24  992.06   991.9  991.81   991.6   991.3
  991.24  991.15  991.05  990.97  990.95  990.87   990.7  990.63  990.26  990.18
     990  989.51  989.34  989.52  989.45  989.87  990.77   993.5   993.5   993.5
   994.2   994.2   994.2   991.5   991.5  992.07  992.76  993.54  994.83   996.3
   997.8  999.92 1000.58 1002.01 1003.96 1003.56 1003.79 1003.81 1003.81 1003.82
 1003.91 1003.99 1004.18 1004.35 1004.46  1004.7 1004.74  1004.8 1005.03 1005.22
 1005.39 1005.42 1005.52 1005.74 1005.74 1005.75 1005.96 1005.97 1006.08 1006.34
 1006.39 1006.61  1006.8 1006.93 1006.94 1006.95
                                                                                
                                                                                
                                                                                
                                                                                
                                                                          989.36
     990
                                                                                
                                                                                
                                                                                
                                                
 -546.76 -545.95  -545.1 -544.55 -544.05 -542.39  -540.6 -539.85 -538.13 -537.16
 -535.26 -532.87 -529.52 -529.28 -527.52 -525.34 -523.28    -489 -473.84 -454.19
 -430.41 -427.48 -419.64 -413.23 -406.36 -397.13 -389.85 -385.12 -375.47 -356.87
 -347.12 -343.48  -334.6 -327.55 -320.63 -310.81 -297.34 -285.71 -243.43  -217.8
 -191.58    -165 -139.38 -114.76  -87.68  -61.89  -19.41  -19.41  -17.41  -17.41
    8.57    8.57   10.27   10.27   10.55   47.67   71.34   89.86   120.5  146.19
  172.99  199.51  207.88  226.01  250.95  251.15  253.29  253.59  254.64  255.29
  256.14  257.54  259.25  261.16  262.55  264.78  265.26  266.61  269.54  271.23
   273.1  273.44  273.94  276.27  276.34   276.4  278.63  279.39  280.85  283.71
  284.18  286.24  287.66  288.87  289.67  289.92
 1004.41 1004.29 1004.11 1004.07 1003.99  1003.7 1003.32 1003.21 1003.05 1002.86
 1002.58 1002.24 1001.61 1001.56 1001.32 1000.99 1000.57  995.29  993.67  993.12
   992.7  992.66  992.54   992.4  992.24  992.06   991.9  991.81   991.6   991.3
  991.24  991.15  991.05  990.97  990.95  990.87   990.7  990.63  990.26  990.18
     990  989.51  989.34  989.52  989.45  989.87  990.77   993.5   993.5   993.5
   994.2   994.2   994.2   991.5   991.5  992.07  992.76  993.54  994.83   996.3
   997.8  999.92 1000.58 1002.01 1003.96 1003.56 1003.79 1003.81 1003.81 1003.82
 1003.91 1003.99 1004.18 1004.35 1004.46  1004.7 1004.74  1004.8 1005.03 1005.22
 1005.39 1005.42 1005.52 1005.74 1005.74 1005.75 1005.96 1005.97 1006.08 1006.34
 1006.39 1006.61  1006.8 1006.93 1006.94 1006.95
                                                                                
                                                                                
                                                                                
                                                                                
                                                                          989.36
     990
                                                                                
                                                                                
                                                                                
                                                
BR Coef=-1 , 1 , 0 ,, 0 ,,,0.8,0,1.2,0,
WSPro=,,,, 1 ,,,, 0 ,,,, 0 ,,,,-1 ,-1 ,-1 , 0 , 0 , 0 , 0 , 0
BC Design=,, 0 ,, 0 ,,,,,,
BC Use User HTab Curves=0
BC User HTab FreeFlow(D)= 0

Type RM Length L Ch R = 1 ,64909.54,244.0514,350.0783,339.4108
BEGIN DESCRIPTION:
Tater Hill Mountain Rd (TWE_34) - DS
END DESCRIPTION:
XS GIS Cut Line= 3
    1494916.5584   1139960.32448    1494408.3061   1140161.45932
   1494136.00066   1140265.89469
#Sta/Elev= 30
 -548.25 1003.22 -500.14  995.78 -490.78  993.36 -474.72  993.46 -448.03  992.32
 -423.28  991.73 -356.03  989.53  -74.77  987.93  -28.72  989.12   -19.5   988.1
   -7.99  988.28    -.26  986.66    2.21  985.09    5.39  985.36    7.83  987.94
    8.73     988   20.54  989.56   67.22  991.67   89.74  991.85  109.53  993.41
  150.11  994.86  179.98  997.53  197.28 1000.15  206.36 1003.17  227.54 1006.09
  249.09  1008.4  254.35 1007.86  279.38 1010.73   286.4 1009.95     290 1011.01
#Mann= 7 ,-1,0
 -548.25    .135       0 -474.72     .06       0 -448.03     .06       0
 -423.28      .1       0  -74.77     .13       0   -7.99     .04       0
    8.73     .13       0
#XS Ineff= 2 , 0
       0     -30     989      20       0     992
Permanent Ineff=
       F       F
Bank Sta=-7.99,8.73
XS Rating Curve= 0 ,0
Exp/Cntr=0.5,0.3

Type RM Length L Ch R = 1 ,64559.46,326.2435,338.1874,332.4392
XS GIS Cut Line= 3
   1494955.51411   1139886.15682   1494446.39829   1139848.39633
   1494140.40814   1139821.05217
#Sta/Elev= 30
  -512.4 1014.05 -504.11 1011.43 -492.78 1009.88  -455.3 1001.43 -434.64  994.46
 -425.37995.0964  -413.2  994.78 -403.95993.4351 -376.61  990.15 -331.21  988.57
 -138.39  986.51  -99.19  987.61  -86.37  986.86   -47.1987.0467  -21.81  987.68
    -8.9  986.85   -7.92  986.02   -5.86  983.81   -3.59   983.8    6.57  984.13
    9.25  985.78   25.56   987.4  105.07  986.64   183.5  986.69  192.67  987.45
  200.68  993.63   204.1  995.26  244.33 1009.38  276.11 1016.99  305.33 1021.81
#Mann= 6 ,-1,0
  -512.4    .135       0 -425.37     .06       0 -403.95      .1       0
   -47.1    .135       0   -7.92     .04       0    9.25    .135       0
Bank Sta=-7.92,9.25
XS Rating Curve= 0 ,0
Exp/Cntr=0.3,0.1

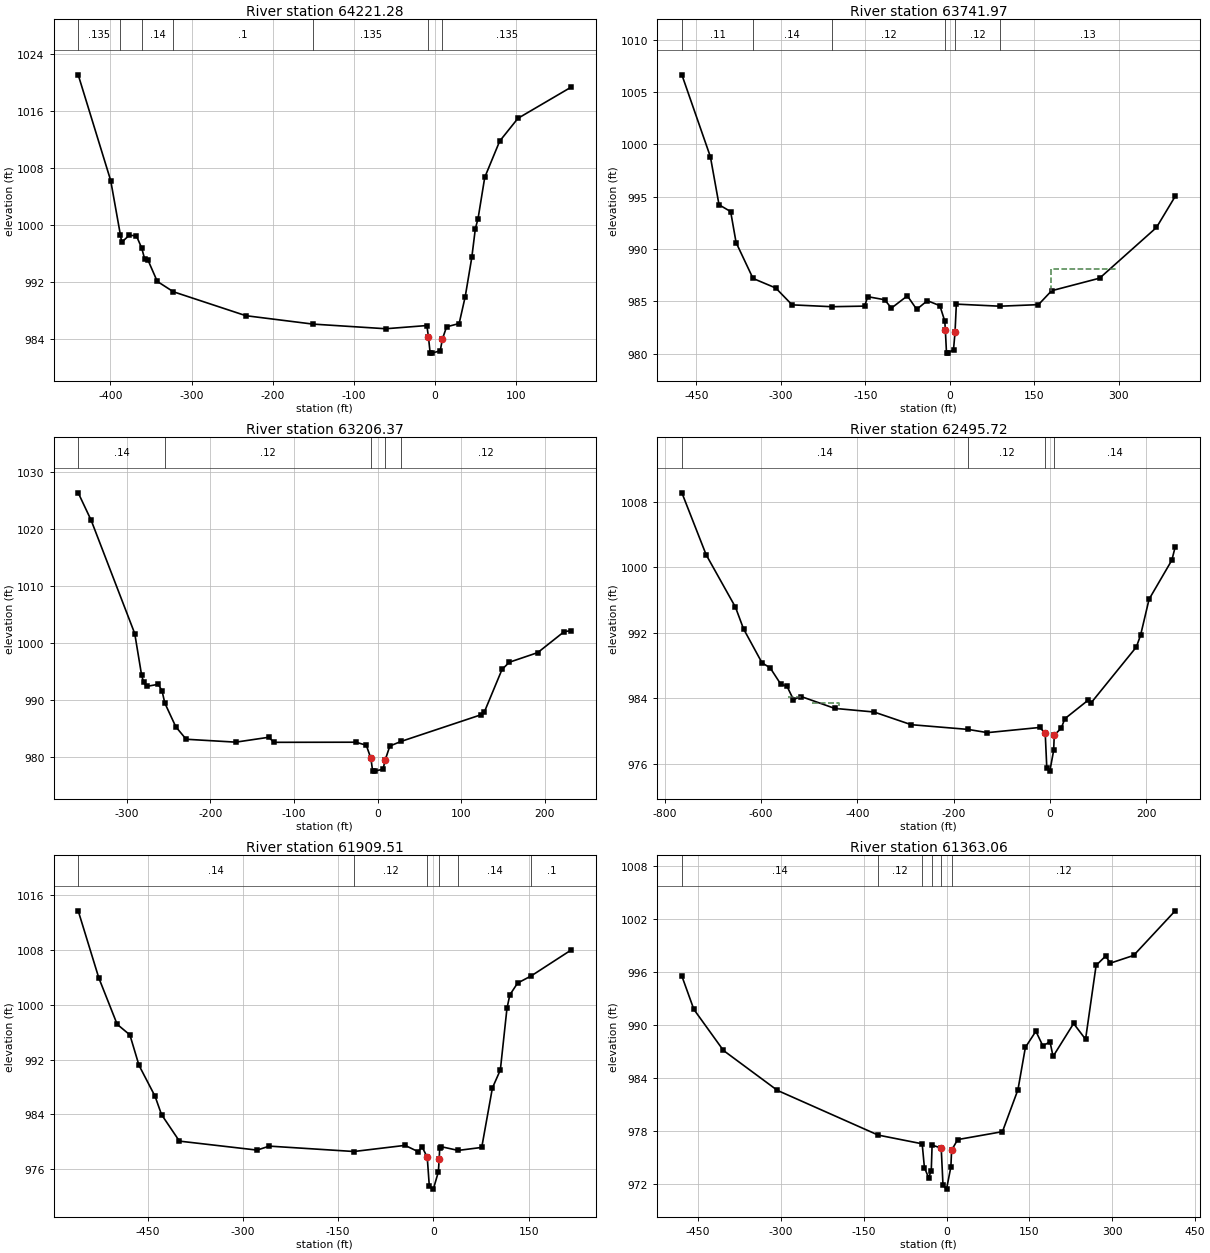
Type RM Length L Ch R = 1 ,64221.28,399.8014,479.3083,372.4897
XS GIS Cut Line= 3
   1494915.14928   1139558.03117   1494480.25262   1139524.17684
    1494308.3773    1139518.9685
#Sta/Elev= 30
 -439.77 1021.03 -399.69 1006.19  -387.7998.5498 -386.14  997.55 -376.76  998.54
    -368  998.44 -361.45996.7295  -357.7  995.15 -353.88  995.08  -342.3  992.06
 -322.42990.6046 -233.05  987.25 -150.52986.0724  -60.55  985.42    -9.9  985.87
   -7.92  984.22   -5.86982.0099   -3.59     982    6.57  982.33    9.25  983.98
   14.41  985.69   29.87  986.15   37.35  989.91    45.5  995.43   49.85  999.45
   53.19 1000.87   61.45 1006.65   79.86 1011.73  102.39 1014.93   168.4 1019.33
#Mann= 7 ,-1,0
 -439.77    .135       0  -387.7     .06       0 -361.45     .14       0
 -322.42      .1       0 -150.52    .135       0   -7.92     .04       0
    9.25    .135       0
Bank Sta=-7.92,9.25
XS Rating Curve= 0 ,0
Exp/Cntr=0.3,0.1

Type RM Length L Ch R = 1 ,63741.97,414.8988,535.5957,451.0252
XS GIS Cut Line= 3
   1494924.26411   1139068.44685   1494457.15322   1139147.25558
   1494060.98097   1139215.58268
#Sta/Elev= 30
 -475.64 1006.63 -425.01   998.8 -409.71  994.22 -389.08  993.57  -379.4  990.61
 -349.35987.1844 -309.01  986.27 -279.99  984.66 -209.88984.4842 -151.29  984.54
 -145.71  985.44 -115.67  985.15 -103.69  984.35  -75.35  985.52  -58.78  984.23
  -39.85  985.06   -17.6  984.58    -8.9   983.1   -7.92  982.27   -5.86  980.06
   -3.59  980.05    6.57  980.38    9.25  982.03   11.61  984.73   88.69984.5318
   157.4  984.68  180.78  986.01  266.03  987.21  366.89  992.05   400.1  995.02
#Mann= 6 ,-1,0
 -475.64     .11       0 -349.35     .14       0 -209.88     .12       0
   -7.92     .04       0    9.25     .12       0   88.69     .13       0
#XS Ineff= 1 ,-1
  179.65  295.77  988.05
Permanent Ineff=
       F
Bank Sta=-7.92,9.25
XS Rating Curve= 0 ,0
Exp/Cntr=0.3,0.1

Type RM Length L Ch R = 1 ,63206.37,683.8718,710.6496,611.7475
BEGIN DESCRIPTION:
TWE_33X
END DESCRIPTION:
XS GIS Cut Line= 5
   1494752.55512    1138692.6063   1494461.53675   1138724.07907
   1494396.40617   1138716.21424   1494327.71129   1138708.10335
    1494165.5315   1138691.52133
#Sta/Elev= 30
 -358.32 1026.38 -342.77 1021.55 -290.65 1001.71 -282.43  994.42 -279.93  993.14
 -276.56  992.44 -262.46  992.81 -257.93  991.64 -254.67  989.53 -241.47  985.36
 -229.09  983.18 -169.67  982.67    -130  983.53 -124.37  982.64  -25.97  982.66
  -13.47  982.13   -7.92  979.81   -5.86   977.6   -3.59  977.59    6.57  977.92
    9.25  979.57   14.72  981.99    28.2   982.8  123.71  987.46  128.01  988.01
  149.03  995.42  157.77  996.68  191.79  998.37  223.47 1002.05  232.19 1002.22
#Mann= 5 ,-1,0
 -358.32     .14       0 -254.67     .12       0   -7.92     .04       0
    9.25     .12       0    28.2     .12       0
Bank Sta=-7.92,9.25
XS Rating Curve= 0 ,0
Exp/Cntr=0.3,0.1

Type RM Length L Ch R = 1 ,62495.72,535.3537,586.2144,526.637
XS GIS Cut Line= 3
   1494925.29856   1137786.57152   1494243.00558   1138119.90551
   1493998.21325   1138224.07251
#Sta/Elev= 30
 -764.85 1009.08 -714.35 1001.51  -653.5  995.12 -636.71  992.47 -598.27  988.32
 -581.37  987.71  -559.1   985.7 -546.46  985.47 -532.98  983.84 -517.08  984.21
  -447.1  982.76 -365.55  982.32 -288.16  980.77 -170.05980.1938 -129.68   979.8
  -21.24  980.43   -9.61  979.76   -6.34  975.54     .01   975.1    7.93  977.63
    9.21  979.51    23.5  980.32   31.22   981.5   79.59  983.76   85.72  983.43
  179.89  990.26  188.63   991.7   206.3  996.09  253.64 1000.86  260.55 1002.47
#Mann= 4 ,-1,0
 -764.85     .14       0 -170.05     .12       0   -9.61     .04       0
    9.21     .14       0
#XS Ineff= 2 ,-1
 -543.98 -516.77  984.21 -494.19 -437.29  983.36
Permanent Ineff=
       F       F
Bank Sta=-9.61,9.21
XS Rating Curve= 0 ,0
Exp/Cntr=0.3,0.1

Type RM Length L Ch R = 1 ,61909.51,384.125,546.4482,467.8672
XS GIS Cut Line= 3
   1494607.58957   1137362.09154   1494103.69948   1137612.11844
   1493912.27592   1137708.44619
#Sta/Elev= 30
 -559.24 1013.74 -526.83 1003.95 -497.91  997.17 -477.85  995.62 -463.52  991.18
 -438.23  986.66 -428.06  983.99 -399.87  980.11 -277.65   978.8  -258.3  979.38
 -125.01978.5942  -44.54  979.49  -23.91  978.57  -17.78  979.28   -9.61  977.76
   -6.34  973.54     .01   973.1    7.93  975.63    9.21  977.51   10.07  979.17
   12.25   979.3   39.03978.7529    76.2  979.19   93.02  987.88  105.51   990.5
  115.93  999.49  120.42 1001.46   132.7 1003.19   154.21004.242  217.56 1008.05
#Mann= 6 ,-1,0
 -559.24     .14       0 -125.01     .12       0   -9.61     .04       0
    9.21     .12       0   39.03     .14       0   154.2      .1       0
Bank Sta=-9.61,9.21
XS Rating Curve= 0 ,0
Exp/Cntr=0.3,0.1

Type RM Length L Ch R = 1 ,61363.06,113.0541,47.42634,15.37912
BEGIN DESCRIPTION:
TWE_32USX
END DESCRIPTION:
XS GIS Cut Line= 6
   1494472.47474   1137136.85072   1494079.67881   1137171.57316
   1493944.05184   1137176.11975   1493876.87697   1137238.33924
   1493843.28904   1137330.29199   1493842.18799   1137503.73556
#Sta/Elev= 30
 -479.03  995.53 -457.36  991.76 -403.83   987.1  -306.1  982.57 -123.74   977.5
  -44.04  976.51     -40  973.81  -32.47  972.68  -27.62  973.43   -26.1  976.36
   -9.61  976.03   -6.34  971.81     .01  971.37    7.93   973.9    9.21  975.78
    20.2  976.99  101.28  977.89  129.32  982.65  142.79  987.45  161.77  989.28
  174.39  987.62  187.34  988.09  192.88  986.42  230.07  990.16  251.72  988.37
  270.79  996.75  287.91   997.8  296.84  997.01  338.71  997.88  413.94 1002.94
#Mann= 6 ,-1,0
 -479.03     .14       0 -123.74     .12       0  -44.04    .045       0
   -26.1     .12       0   -9.61     .04       0    9.21     .12       0
Bank Sta=-9.61,9.21
XS Rating Curve= 0 ,0
Exp/Cntr=0.5,0.3

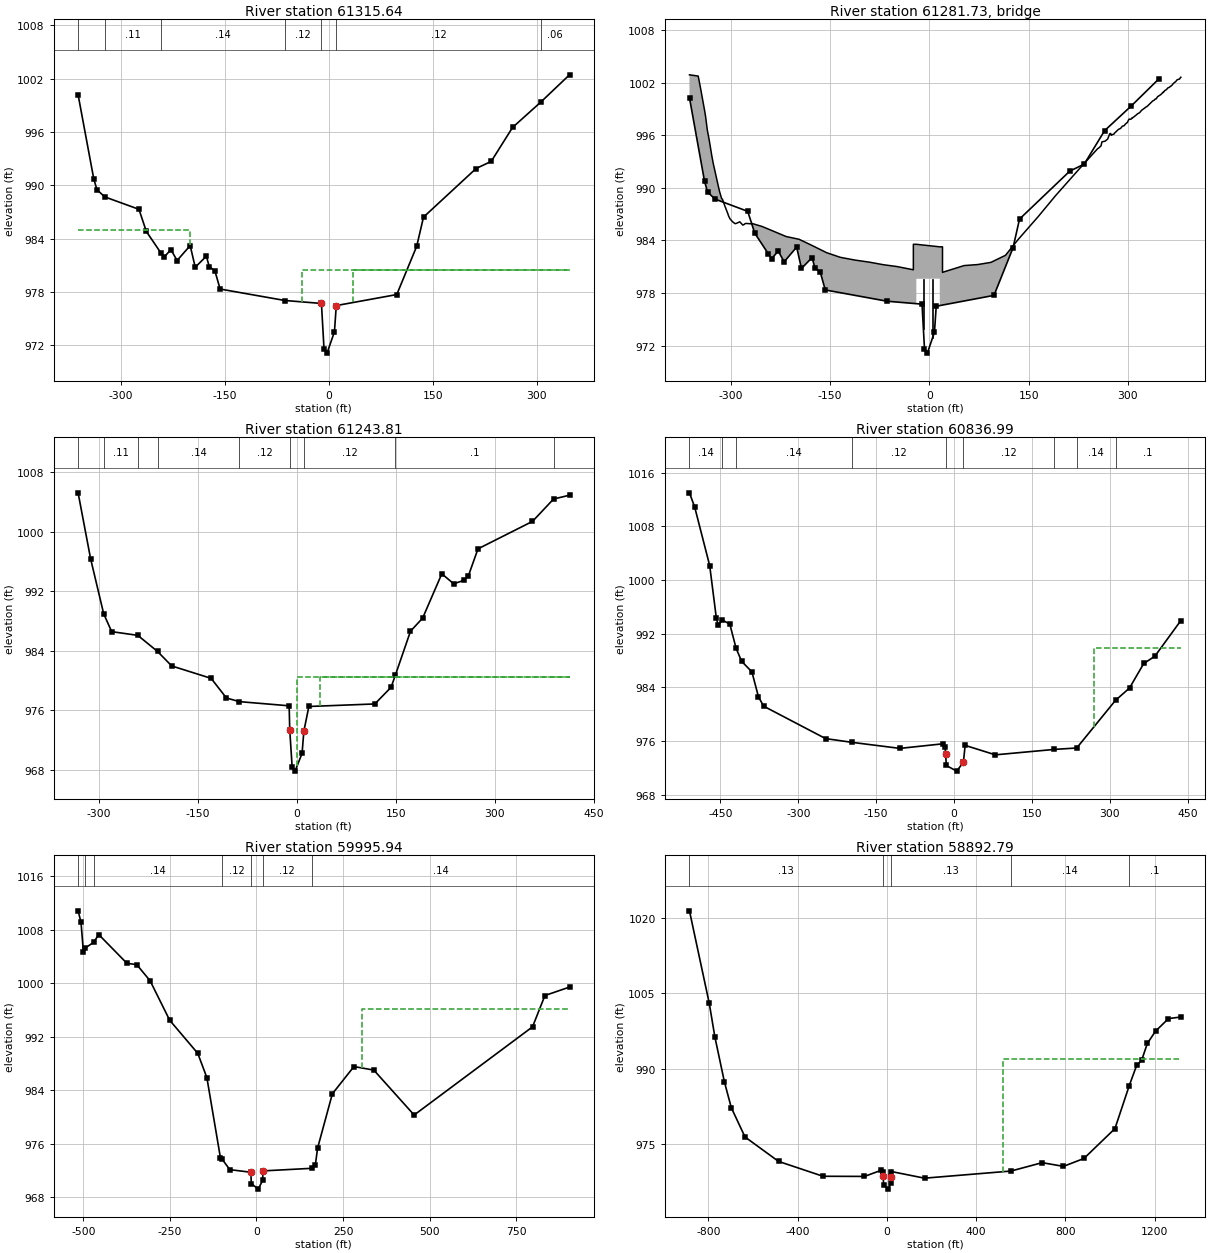
Type RM Length L Ch R = 1 ,61315.64,58.08566,71.82238,65.56407
BEGIN DESCRIPTION:
Ponderosa Rd (TWE_32) - US
END DESCRIPTION:
XS GIS Cut Line= 6
   1494370.79232   1136888.40617   1493919.27428   1137183.82841
   1493869.16831   1137236.13681   1493848.24475   1137276.33169
   1493831.72638   1137341.30413    1493831.7792   1137482.21719
#Sta/Elev= 30
 -361.86 1000.19-339.301  990.74-334.706  989.52-323.516  988.71 -274.08  987.31
-263.472  984.82-242.854  982.45-238.021   981.9 -228.06  982.78-219.082  981.55
-200.193  983.23-192.927  980.79-176.855  982.04-172.735  980.87-164.527  980.37
-157.023  978.34  -63.46  977.05 -10.887  976.72  -7.176  971.63  -2.818  971.13
   7.888  973.53  10.526  976.48   97.79  977.72 126.526  983.15  136.34  986.43
 212.185   991.9 234.015   992.7 264.807  996.52 305.208  999.35 346.935 1002.44
#Mann= 7 ,-1,0
 -361.86     .14       0-323.516     .11       0-242.854     .14       0
  -63.46     .12       0 -10.887     .04       0  10.526     .12       0
 305.208     .06       0
#XS Ineff= 3 ,-1
 -361.86 -200.19     985     -39    -200   980.5      35 346.935   980.5
Permanent Ineff=
       F       F       F
Bank Sta=-10.887,10.526
XS Rating Curve= 0 ,0
Skew Angle= 35
Exp/Cntr=0.5,0.3

Type RM Length L Ch R = 3 ,61281.73,,,
BEGIN DESCRIPTION:
Ponderosa Rd (TWE_32) - TOR
Skew = 35 Degrees
END DESCRIPTION:
Bridge Culvert--1,0,-1,-1, 0
Deck Dist Width WeirC Skew NumUp NumDn MinLoCord MaxHiCord MaxSubmerge Is_Ogee
20,27.5,2.6,35, 169, 169, 980.35, , 0.95, 0, 0,0,,
-362.065-348.852-348.344-344.912-338.875-337.474 -335.14-332.289-329.463-328.341
-326.104-317.307-316.946-313.702-312.015-308.517-304.028-303.234 -301.03-300.932
-300.817-297.909-295.992-293.011-289.832 -286.13-281.469-280.355-279.544-277.906
-276.308-268.641-268.125-267.797-252.217-215.863-213.135-196.441-175.987-154.869
-134.578-129.221-111.446  -90.23 -69.292 -48.649 -23.977 -23.977 -19.471 -19.471
  15.924  15.924   20.02   20.02  52.557  73.404   93.26  96.996 115.074 133.948
 140.992 164.289 190.608 200.143 226.274 254.232 255.715 255.928 256.051 259.425
 260.466 260.777 262.006  265.52 267.805 269.419 272.393  272.95 274.105 274.768
 277.594 278.888 279.699 282.689 285.089 286.113 288.358 288.997 291.594 294.272
  296.05   297.5 298.499 299.203 300.916 301.923 302.521 303.201 304.913 305.667
 306.076 310.721  311.36 312.662 314.161 314.497 315.447 317.643 318.675 320.837
  321.14 323.844 324.859 326.825 327.276 328.783 332.469 332.838 333.067 334.992
 336.082 337.302 339.948 341.029 342.651 342.848 342.897 343.077  344.74 345.764
 346.485 347.304 349.901  350.63 350.982 352.465 352.579 353.071 353.407 354.947
 355.717 356.241 356.405 358.101 359.796 360.271 360.558 361.877 362.655 363.982
 365.448 365.973 366.366 367.062 368.356 369.028 370.265 370.765  372.19 373.836
  374.23 374.271 374.787 377.547 377.785 379.153 379.472  379.53 379.915
 1002.89 1002.75 1002.55  1001.2  998.68  998.01  996.62  995.47  994.14  993.66
  992.76  989.78  989.67  988.82  988.65   987.9  987.03  986.83  986.48  986.47
  986.45   986.2  986.06   985.9  985.98  986.12  985.74  985.78  985.81  985.91
  985.93  985.89  985.88  985.93  985.58  984.43  984.39  984.12  983.38  982.59
  982.07  981.99  981.74  981.51  981.22  981.01  980.64  983.55  983.55  983.55
  983.26  983.26  983.26  980.35  981.12  981.24  981.49  981.63  982.29  984.07
  984.68  986.69  989.09   989.9  992.13  994.46  994.52  994.54  994.55  994.79
  995.16  995.24  995.26  995.32  995.47  995.56  996.14  996.19  996.19  995.99
   996.1  996.12  996.23  996.45  996.62  996.68  996.76  996.78  997.03  997.08
  997.26  997.35  997.42  997.46  997.73  997.84  997.82  997.81  997.84  997.95
  997.93  998.19  998.23  998.32  998.41  998.44  998.48  998.57  998.67  998.86
  998.87  999.01  999.07   999.2  999.22  999.27  999.54  999.57  999.58  999.74
  999.82   999.9 1000.01 1000.12 1000.16 1000.16 1000.16 1000.19 1000.39 1000.44
 1000.47 1000.51 1000.65 1000.71 1000.74 1000.86 1000.87  1000.9 1000.88 1001.03
 1001.09 1001.12 1001.13  1001.2 1001.35 1001.39 1001.41 1001.44 1001.47 1001.56
 1001.63 1001.66 1001.69 1001.75 1001.89 1001.92 1002.02 1002.04 1002.12 1002.28
 1002.32 1002.32 1002.34 1002.39  1002.4 1002.57  1002.6  1002.6 1002.62
                                                                                
                                                                                
                                                                                
                                                                                
                                                                          979.61
  979.63
                                                                                
                                                                                
                                                                                
                                                                                
                                                                                
                                                                                
                                                                                
                                                                                
                                                                                
                                                                                
                                                                        
 -349.18-348.852-348.344-344.912-338.875-337.474 -335.14-332.289-329.463-328.341
-326.104-317.307-316.946-313.702-312.015-308.517-304.028-303.234 -301.03-300.932
-300.817-297.909-295.992-293.011-289.832 -286.13-281.469-280.355-279.544-277.906
-276.308-268.641-268.125-267.797-252.217-215.863-213.135-196.441-175.987-154.869
-134.578-129.221-111.446  -90.23 -69.292 -48.649 -23.977 -23.977 -19.471 -19.471
  15.924  15.924   20.02   20.02  52.557  73.404   93.26  96.996 115.074 133.948
 140.992 164.289 190.608 200.143 226.274 254.232 255.715 255.928 256.051 259.425
 260.466 260.777 262.006  265.52 267.805 269.419 272.393  272.95 274.105 274.768
 277.594 278.888 279.699 282.689 285.089 286.113 288.358 288.997 291.594 294.272
  296.05   297.5 298.499 299.203 300.916 301.923 302.521 303.201 304.913 305.667
 306.076 310.721  311.36 312.662 314.161 314.497 315.447 317.643 318.675 320.837
  321.14 323.844 324.859 326.825 327.276 328.783 332.469 332.838 333.067 334.992
 336.082 337.302 339.948 341.029 342.651 342.848 342.897 343.077  344.74 345.764
 346.485 347.304 349.901  350.63 350.982 352.465 352.579 353.071 353.407 354.947
 355.717 356.241 356.405 358.101 359.796 360.271 360.558 361.877 362.655 363.982
 365.448 365.973 366.366 367.062 368.356 369.028 370.265 370.765  372.19 373.836
  374.23 374.271 374.787 377.547 377.785 379.153 379.472  379.53 379.915
 1002.89 1002.75 1002.55  1001.2  998.68  998.01  996.62  995.47  994.14  993.66
  992.76  989.78  989.67  988.82  988.65   987.9  987.03  986.83  986.48  986.47
  986.45   986.2  986.06   985.9  985.98  986.12  985.74  985.78  985.81  985.91
  985.93  985.89  985.88  985.93  985.58  984.43  984.39  984.12  983.38  982.59
  982.07  981.99  981.74  981.51  981.22  981.01  980.64  983.55  983.55  983.55
  983.26  983.26  983.26  980.35  981.12  981.24  981.49  981.63  982.29  984.07
  984.68  986.69  989.09   989.9  992.13  994.46  994.52  994.54  994.55  994.79
  995.16  995.24  995.26  995.32  995.47  995.56  996.14  996.19  996.19  995.99
   996.1  996.12  996.23  996.45  996.62  996.68  996.76  996.78  997.03  997.08
  997.26  997.35  997.42  997.46  997.73  997.84  997.82  997.81  997.84  997.95
  997.93  998.19  998.23  998.32  998.41  998.44  998.48  998.57  998.67  998.86
  998.87  999.01  999.07   999.2  999.22  999.27  999.54  999.57  999.58  999.74
  999.82   999.9 1000.01 1000.12 1000.16 1000.16 1000.16 1000.19 1000.39 1000.44
 1000.47 1000.51 1000.65 1000.71 1000.74 1000.86 1000.87  1000.9 1000.88 1001.03
 1001.09 1001.12 1001.13  1001.2 1001.35 1001.39 1001.41 1001.44 1001.47 1001.56
 1001.63 1001.66 1001.69 1001.75 1001.89 1001.92 1002.02 1002.04 1002.12 1002.28
 1002.32 1002.32 1002.34 1002.39  1002.4 1002.57  1002.6  1002.6 1002.62
                                                                                
                                                                                
                                                                                
                                                                                
                                                                          979.63
   979.6
                                                                                
                                                                                
                                                                                
                                                                                
                                                                                
                                                                                
                                                                                
                                                                                
                                                                                
                                                                                
                                                                        
Pier Skew, UpSta & Num, DnSta & Num=  ,-8.814, 4 ,-8.814, 4 , 3 , 3 , 0 ,,
       1       1     1.5     1.5
     970  978.61  978.61     980
       1       1     1.5     1.5
     970  978.61  978.61     980
Pier Skew, UpSta & Num, DnSta & Num=  ,4.751, 4 ,4.751, 4 , 3 , 3 , 0 ,,
       1       1     1.5     1.5
     970  978.61  978.61     980
       1       1     1.5     1.5
     970  978.61  978.61     980
BR Coef=-1 , 1 , 0 ,, 0 ,,,0.8,0,1.2,0,
WSPro=,,,, 1 ,,,, 0 ,,,, 0 ,,,,-1 ,-1 ,-1 , 0 , 0 , 0 , 0 , 0
BC Design=,, 0 ,, 0 ,,,,,,
BC Use User HTab Curves=0
BC User HTab FreeFlow(D)= 0

Type RM Length L Ch R = 1 ,61243.81,387.1822,406.8167,383.6989
BEGIN DESCRIPTION:
Ponderosa Rd (TWE_32) - DS
END DESCRIPTION:
XS GIS Cut Line= 6
   1494339.90584    1136838.5899   1493913.69751   1137112.57776
   1493841.74245    1137191.2897   1493809.85991   1137248.08038
   1493783.95538   1137353.69094   1493788.93701   1137476.23917
#Sta/Elev= 30
 -331.92 1005.25-313.023  996.41 -293.15     989-281.018  986.59-241.363  986.09
-211.472  983.93-189.929  981.98-130.114  980.31-106.908  977.67   -87.1  977.18
 -11.747  976.62 -10.887  973.43  -7.176  968.34  -2.818  967.84   7.888  970.24
  10.526  973.19  18.152  976.53 118.204  976.87 142.901  979.11 149.299  980.72
 172.341  986.65 190.756  988.41 219.844  994.37 237.906  993.02 253.052  993.48
 259.851  994.01 274.719  997.72 357.429 1001.41 389.441 1004.42 413.565 1004.93
#Mann= 9 ,-1,0
 -331.92     .14       0 -293.15     .11       0-241.363     .06       0
-211.472     .14       0   -87.1     .12       0 -10.887     .04       0
  10.526     .12       0 149.299      .1       0 389.441     .14       0
#XS Ineff= 2 , 0
       0     -40   980.5      35       0   980.5
Permanent Ineff=
       F       F
Bank Sta=-10.887,10.526
XS Rating Curve= 0 ,0
Skew Angle= 35
Exp/Cntr=0.5,0.3

Type RM Length L Ch R = 1 ,60836.99,650.8298,841.0577,674.1644
XS GIS Cut Line= 3
   1494205.80315   1136466.79462   1493779.22999   1136747.10105
   1493416.13419   1136988.72146
#Sta/Elev= 30
 -509.67    1013  -499.5 1010.85 -470.69 1002.15  -457.8  994.27 -454.15  993.24
 -446.55  994.02 -431.96  993.44 -419.85  989.82 -409.21  987.88 -389.36   986.3
 -376.77  982.59 -366.88  981.19 -247.38  976.35 -196.38  975.79 -104.25  974.89
  -22.06  975.57   -17.3  975.06  -16.12  974.02  -14.93  972.34    5.12   971.5
   18.08  972.83   21.34  975.34   79.56  973.93  193.47  974.74  236.31  974.95
   311.1  982.06     338  983.89  365.44  987.55  386.81  988.63   436.9  993.95
#Mann= 9 ,-1,0
 -509.67     .14       0 -446.55     .06       0 -419.85     .14       0
 -196.38     .12       0  -16.12     .04       0   18.08     .12       0
  193.47     .12       0  236.31     .14       0   311.1      .1       0
#XS Ineff= 2 , 0
                          269.36          989.92
Permanent Ineff=
       F       F
Bank Sta=-16.12,18.08
XS Rating Curve= 0 ,0
Exp/Cntr=0.3,0.1

Type RM Length L Ch R = 1 ,59995.94,1016.771,1103.151,955.7007
XS GIS Cut Line= 4
   1493900.16142   1135930.25492   1493450.41831   1136177.14272
   1493236.87631   1136302.14304    1493177.9393   1136958.03281
#Sta/Elev= 30
 -515.04 1010.82 -506.69 1009.11 -499.77  1004.7  -495.1 1005.24  -469.8 1006.13
 -455.61 1007.28 -374.03 1002.98 -345.81 1002.79 -307.22 1000.38 -250.48  994.47
 -169.46  989.53 -143.18   985.9 -104.14  973.96  -98.96  973.71  -77.03  972.16
  -16.12  971.77  -14.93  970.09    5.12  969.25   18.08  970.58   18.53  971.97
  159.77  972.36  170.16   972.9  176.45  975.36  219.16  983.49  281.51  987.56
  338.91  987.03  455.34  980.32  797.21  993.49  833.03  998.17  903.98  999.43
#Mann= 7 ,-1,0
 -515.04     .14       0  -495.1     .06       0  -469.8     .14       0
  -98.96     .12       0  -16.12     .04       0   18.53     .12       0
  159.77     .14       0
#XS Ineff= 2 , 0
                          303.33           996.1
Permanent Ineff=
       F       F
Bank Sta=-16.12,18.53
XS Rating Curve= 0 ,0
Exp/Cntr=0.3,0.1

Type RM Length L Ch R = 1 ,58892.79,585.639,764.8176,605.2095
XS GIS Cut Line= 3
   1493190.86877   1134992.24475   1492643.99278   1135673.66962
   1491849.72047   1136737.04003
#Sta/Elev= 30
 -884.33 1021.41 -795.52 1002.97  -770.5   996.3 -727.55  987.31 -696.76   982.2
 -635.48  976.38 -485.27  971.52 -286.17  968.56  -100.4  968.53  -26.73  969.73
   -16.8  969.48  -16.12  968.52  -14.93  966.84    5.12     966   17.82  967.28
   18.78  968.42   20.36   969.5  168.59  968.18  555.69   969.6   695.7  971.27
  790.66  970.53  882.52   972.1 1021.45  978.05  1085.6  986.61  1118.7  990.65
 1140.68  991.61 1166.86  995.03 1203.34  997.45 1261.21  999.95 1316.67 1000.27
#Mann= 5 ,-1,0
 -884.33     .13       0  -16.12     .04       0   18.78     .13       0
  555.69     .14       0  1085.6      .1       0
#XS Ineff= 2 , 0
                          520.13             992
Permanent Ineff=
       F       F
Bank Sta=-16.12,18.78
XS Rating Curve= 0 ,0
Exp/Cntr=0.3,0.1

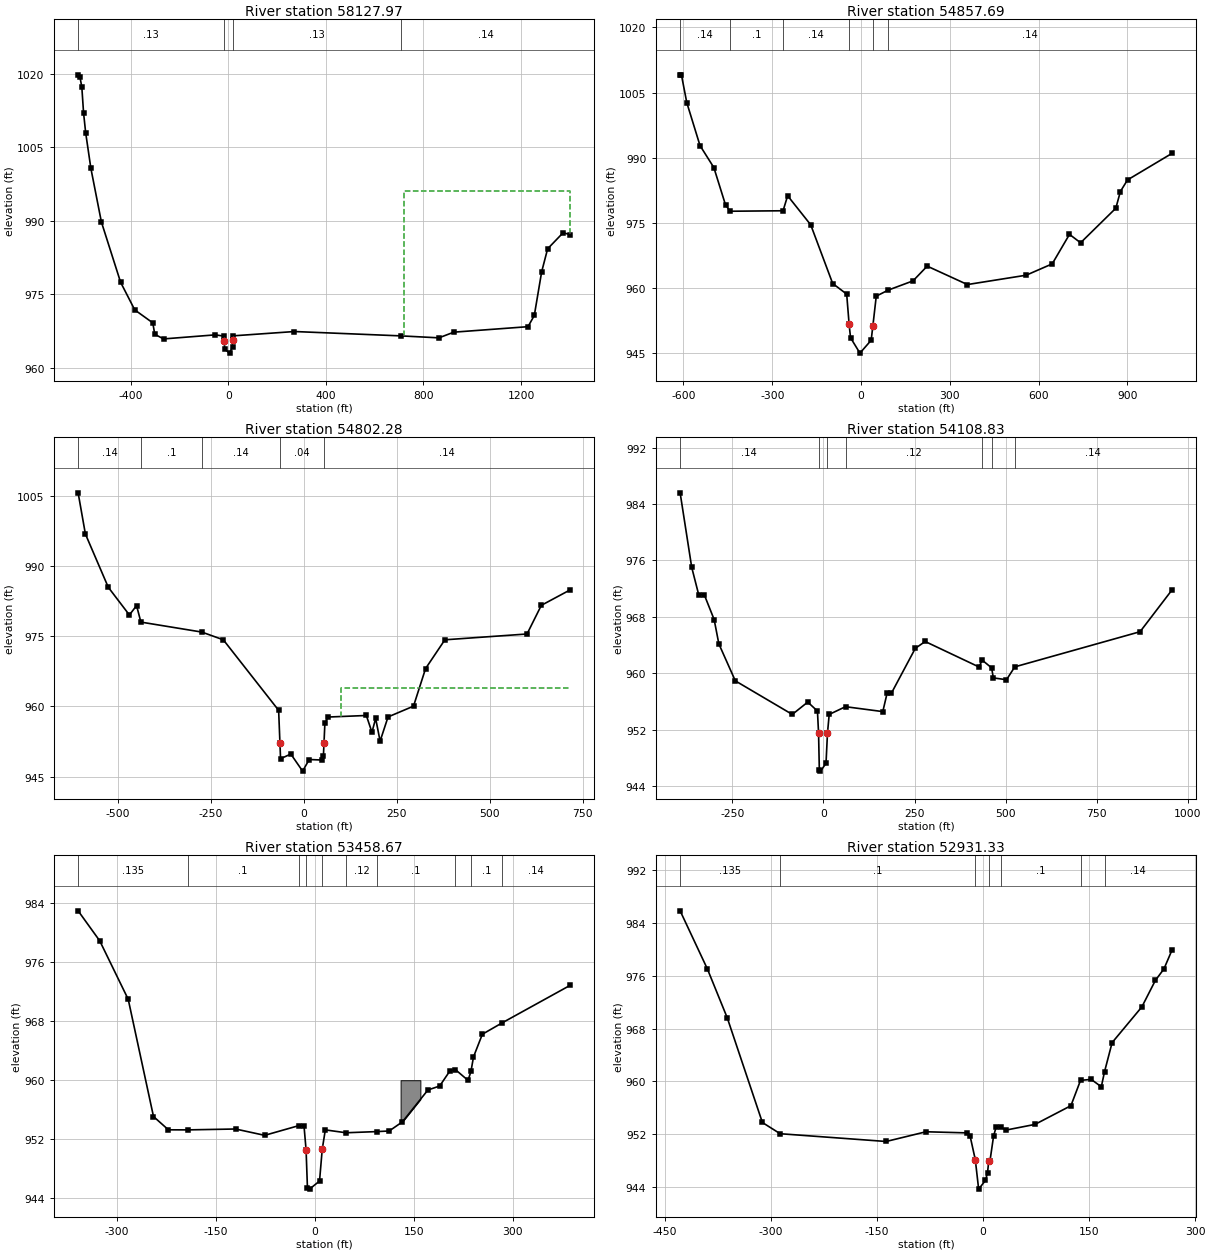
Type RM Length L Ch R = 1 ,58127.97,653.5295,1114.794,595.4461
XS GIS Cut Line= 4
   1492709.09744   1134653.70243    1492340.1729   1135122.45341
   1491880.10269   1135678.00984   1491219.16306   1135902.89304
#Sta/Elev= 30
  -615.5 1019.82 -607.64 1019.29 -600.34 1017.31  -593.2 1012.04 -584.65 1008.02
 -563.25 1000.73 -520.19  989.79 -441.42  977.47 -383.41  971.83 -309.46  969.18
 -301.33  966.85 -265.32   965.9  -53.13  966.73  -18.99  966.48  -16.12  965.52
  -14.93  963.84    5.12     963   17.82  964.28   19.09  965.58   20.34  966.53
  271.28  967.41  708.23  966.52  863.57  966.12  924.56  967.28 1228.79   968.4
 1254.58  970.69 1284.75  979.61 1309.18   984.3  1372.7  987.58 1400.49  987.21
#Mann= 4 ,-1,0
  -615.5     .13       0  -16.12     .04       0   19.09     .13       0
  708.23     .14       0
#XS Ineff= 2 , 0
                          721.94          996.12
Permanent Ineff=
       F       F
Bank Sta=-16.12,19.09
XS Rating Curve= 0 ,0
Exp/Cntr=0.3,0.1

Type RM Length L Ch R = 1 ,54857.69,50.84569,55.41602,71.15096
BEGIN DESCRIPTION:
Dam E. of Midway RD (TWE_30) - DS
END DESCRIPTION:
XS GIS Cut Line= 6
   1490592.03937   1133108.30348   1490503.49738   1133333.99869
   1490269.14436   1133620.46982   1490107.66339        1133959.
   1490126.76083   1134085.73589   1490404.53904   1134547.54265
#Sta/Elev= 30
 -611.27 1008.93  -606.9 1009.08 -588.71 1002.67 -544.08   992.8 -497.29  987.74
 -457.94  979.16 -442.33  977.69 -263.42   977.8 -247.92  981.25 -169.91  974.56
  -95.72  961.06   -48.4  958.62  -40.16  951.66  -35.39  948.58   -3.66  945.04
   34.33     948   40.07   951.3   51.54  958.15    91.9  959.54  175.84  961.67
  223.66  965.06  359.54  960.82  558.15  962.97  646.16  965.58  704.55  972.37
  742.04  970.43  861.17  978.39  876.49  982.23  900.66   984.9  1050.6  990.99
#Mann= 6 ,-1,0
 -611.27     .14       0 -442.33      .1       0 -263.42     .14       0
  -40.16    .045       0   40.07     .14       0    91.9     .14       0
Bank Sta=-40.16,40.07
XS Rating Curve= 0 ,0
Exp/Cntr=0.5,0.3

Type RM Length L Ch R = 1 ,54802.28,527.0717,693.4466,535.7596
BEGIN DESCRIPTION:
TWE_30DSX
END DESCRIPTION:
XS GIS Cut Line= 6
   1490564.26148   1133103.09514   1490480.92815   1133335.73458
   1490310.07087   1133498.24409   1490226.75427   1133585.52756
   1489909.04528   1133906.70899   1489820.50361   1134158.44554
#Sta/Elev= 30
 -607.24  1005.6 -587.76  996.82 -526.14  985.43 -469.43  979.52 -450.12  981.52
  -438.5     978 -274.69  975.87 -216.89  974.22  -68.13  959.16   -64.6  952.09
  -62.97  948.83  -35.39  949.83   -3.66  946.18   14.12  948.66   48.08  948.55
   52.26  949.45   53.83  952.18   56.22  956.43   65.11  957.73  167.68  958.06
  182.76  954.48   192.7  957.44  204.68  952.58  226.02  957.75  294.47  960.05
  326.94  968.08  378.82  974.22  599.72  975.46  638.16  981.58  714.96  984.85
#Mann= 5 ,-1,0
 -607.24     .14       0  -438.5      .1       0 -274.69     .14       0
   -64.6     .04       0   53.83     .14       0
#XS Ineff= 2 , 0
                          100.27          963.98
Permanent Ineff=
       F       F
Bank Sta=-64.6,53.83
XS Rating Curve= 0 ,0
Exp/Cntr=0.3,0.1

Type RM Length L Ch R = 1 ,54108.83,630.9732,650.1635,610.911
XS GIS Cut Line= 4
   1490429.87992   1132957.27165   1490076.14665   1133111.35138
   1489466.75131   1133383.54823   1489171.19685   1133373.93898
#Sta/Elev= 30
 -392.97  985.58 -361.18  975.01  -342.1  971.15  -326.9  971.15 -299.64  967.61
 -286.73  964.16 -241.56  958.92   -85.3  954.16  -42.91  955.91  -16.28  954.64
   -13.2  951.46  -11.14  946.33   -7.94  946.12    7.19  947.22   11.26  951.52
   15.95  954.16   60.71955.2551  162.96  954.56   174.7  957.15   186.4  957.15
  252.22  963.53  279.18   964.5   427.2  960.88  435.43961.8668  461.49960.7619
   466.2  959.34  502.29  959.08  525.06960.9039  868.76  965.89     956  971.79
#Mann= 7 ,-1,0
 -392.97     .14       0   -13.2     .04       0   11.26     .14       0
   60.71     .12       0  435.43     .06       0  461.49      .1       0
  525.06     .14       0
Bank Sta=-13.2,11.26
XS Rating Curve= 0 ,0
Exp/Cntr=0.3,0.1

Type RM Length L Ch R = 1 ,53458.67,464.3838,527.3426,535.4126
BEGIN DESCRIPTION:
TWE_29X
END DESCRIPTION:
XS GIS Cut Line= 5
    1490097.8481    1132375.6729   1489884.26542   1132511.71916
   1489794.05807   1132565.68701   1489741.91503    1132599.0584
   1489425.10367   1132670.81266
#Sta/Elev= 30
 -358.57  982.99 -325.85  978.92 -282.67  970.98 -244.38  955.07 -221.78  953.27
 -192.62  953.26 -120.13  953.38  -75.94  952.52  -24.52  953.83  -16.28  953.74
   -13.2  950.56  -11.14  945.43   -7.94  945.22    7.19  946.32   11.26  950.62
   15.95  953.26   47.39  952.87   94.28  953.03   112.7  953.11  132.78  954.35
  171.45  958.68  189.16  959.21  204.42  961.22  212.93  961.45   232.2  959.98
  236.63   961.2  240.46  963.16  253.86  966.24  283.97  967.79  386.52  972.86
#Mann= 10 ,-1,0
 -358.57    .135       0 -192.62      .1       0  -24.52     .12       0
   -13.2     .04       0   11.26      .1       0   47.39     .12       0
   94.28      .1       0  212.93     .06       0  236.63      .1       0
  283.97     .14       0
#Block Obstruct= 1 ,-1
     130     160     960
Bank Sta=-13.2,11.26
XS Rating Curve= 0 ,0
Exp/Cntr=0.3,0.1

Type RM Length L Ch R = 1 ,52931.33,302.7447,311.809,300.2909
XS GIS Cut Line= 3
   1489967.63944   1132024.10991   1489550.97178   1132110.91535
   1489288.38484   1132173.84974
#Sta/Elev= 30
 -428.46  985.79  -389.8  976.98 -361.73   969.6  -312.1   953.8 -286.96952.1042
 -137.06  950.93  -80.65   952.4  -22.76  952.23  -18.38   951.8  -10.93  948.18
   -6.18  943.73    3.41  945.04    6.37  946.18    8.04  947.95    9.87  948.02
   14.92  951.74   18.53  953.11   24.77 953.114   32.25  952.65   73.47  953.51
  124.34  956.34  137.95 960.172  153.09  960.31  167.34   959.2  171.89961.4764
  182.59  965.87  224.74  971.28  243.83  975.28  255.92  977.01  267.17  979.82
#Mann= 7 ,-1,0
 -428.46    .135       0 -286.96      .1       0  -10.93     .04       0
    8.04     .12       0   24.77      .1       0  137.95     .06       0
  171.89     .14       0
Bank Sta=-10.93,8.04
XS Rating Curve= 0 ,0
Exp/Cntr=0.3,0.1