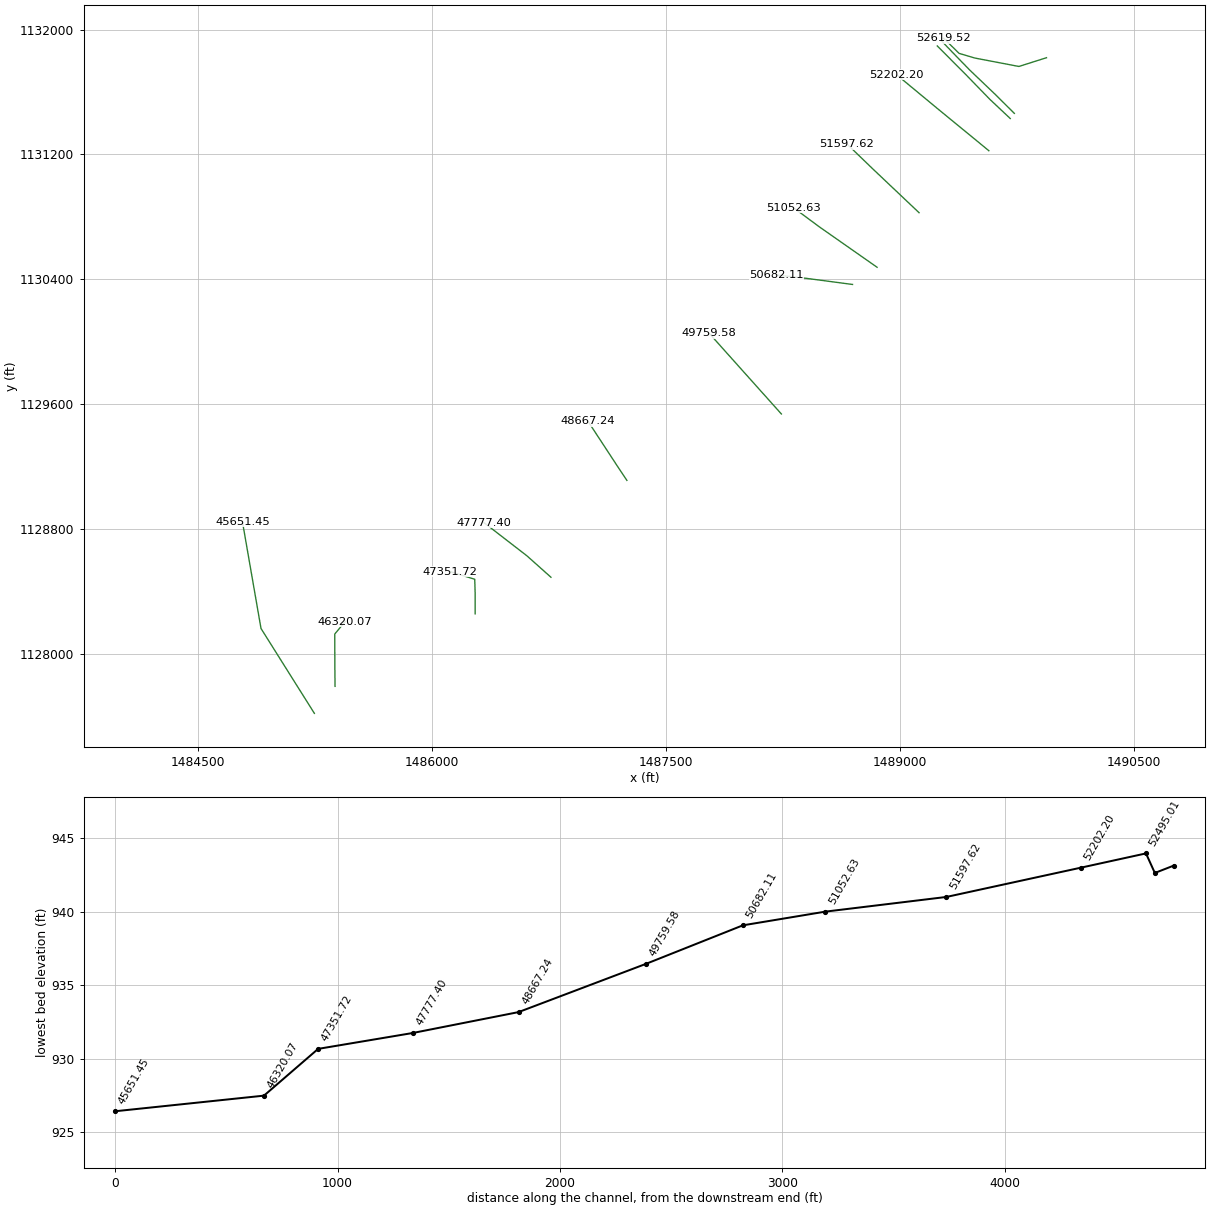
HEC-RAS study 12mile_Combined.prj: 12mile Creek Combined Model

--- 12mile_Combined.g01 (geometry) --- (continued)

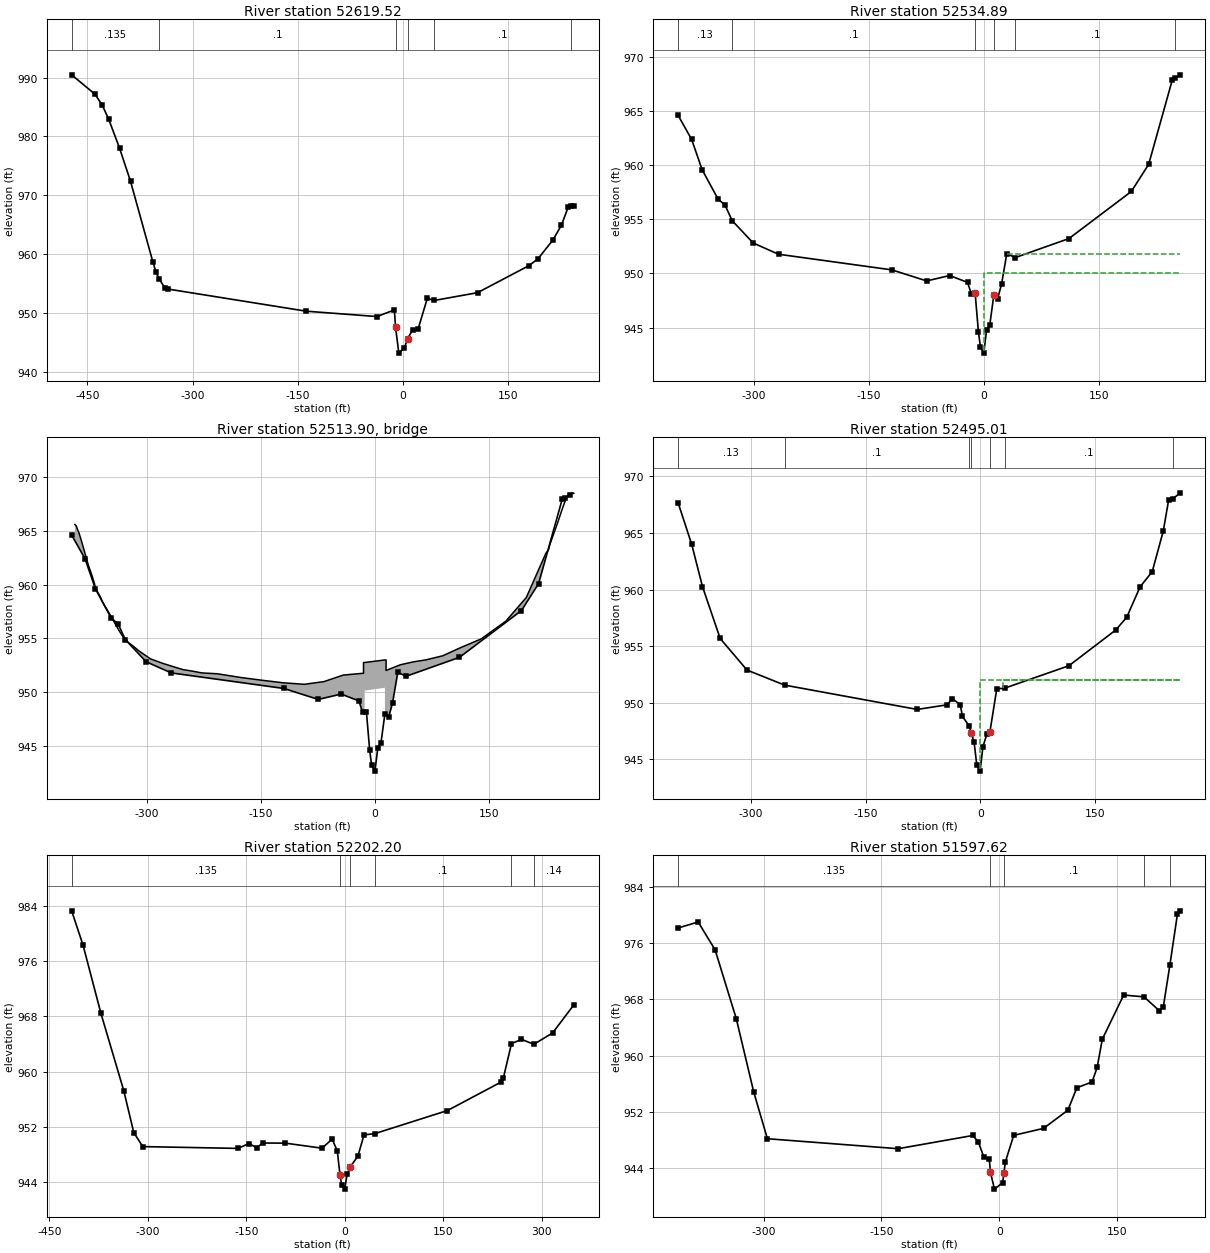
Type RM Length L Ch R = 1 ,52619.52,161.9004,84.63351,63.53086
BEGIN DESCRIPTION:
TWE_28USX
END DESCRIPTION:
XS GIS Cut Line= 5
   1489938.41207   1131819.97211   1489761.47966   1131763.87139
   1489479.48983   1131817.76739   1489378.52165   1131847.61122
   1489280.30938   1131944.04068
#Sta/Elev= 30
 -472.44  990.46 -438.87  987.13 -428.68  985.25 -419.86  982.98 -404.17  977.99
 -388.52  972.34 -356.74  958.66 -352.19  956.88 -347.82  955.78 -339.28  954.14
 -334.91  954.02 -138.03  950.26  -37.33  949.35  -12.53  950.48  -10.93  947.58
   -6.18  943.13    1.74  944.04    6.37  945.58   13.37  947.07   21.09  947.16
   34.36  952.44   44.39  952.09  105.95  953.41  179.19  958.01  192.01  959.16
  213.37  962.37  225.55   964.9  235.42  968.05  238.56  968.23  243.19  968.16
#Mann= 6 ,-1,0
 -472.44    .135       0 -347.82      .1       0  -10.93    .045       0
    6.37     .12       0   44.39      .1       0  238.56     .06       0
Bank Sta=-10.93,6.37
XS Rating Curve= 0 ,0
Exp/Cntr=0.5,0.3

Type RM Length L Ch R = 1 ,52534.89,49.06389,39.87159,41.53906
BEGIN DESCRIPTION:
SE. of Midway RD (TWE_28) - US
END DESCRIPTION:
XS GIS Cut Line= 5
   1489732.33202   1131463.35663   1489607.83694   1131586.93045
   1489447.63845   1131739.82251   1489351.36909   1131838.56037
    1489265.9603   1131927.27625
#Sta/Elev= 30
-399.155  964.63-381.483   962.4-367.805   959.6-347.244  956.91-337.999  956.33
-328.535  954.88-301.209  952.82-268.146  951.78-119.992  950.33 -74.854  949.31
 -44.639  949.81 -21.368  949.17 -16.617  948.14 -11.516  948.18  -7.242  944.61
  -4.573  943.17   -.269  942.63   3.447  944.78   7.661  945.27  12.841  947.98
  17.762  947.65  22.962  949.01  29.786  951.83  40.824  951.47 110.906  953.23
 192.395  957.59 214.969   960.1 245.931  967.94 249.686  968.06 256.251  968.38
#Mann= 6 ,-1,0
-399.155     .13       0-328.535      .1       0 -11.516    .045       0
  12.841     .12       0  40.824      .1       0 249.686     .06       0
#XS Ineff= 2 , 0
       0     -30     950      30       0  951.84
Permanent Ineff=
       F       F
Bank Sta=-11.516,12.841
XS Rating Curve= 0 ,0
Skew Angle= 5
Exp/Cntr=0.5,0.3

Type RM Length L Ch R = 3 ,52513.90,,,
BEGIN DESCRIPTION:
SE. of Midway RD (TWE_28) - TOR
Skew = 5 degrees
END DESCRIPTION:
Bridge Culvert--1,0,-1,-1, 0
Deck Dist Width WeirC Skew NumUp NumDn MinLoCord MaxHiCord MaxSubmerge Is_Ogee
15,12,2.6,5, 88, 88, 950.72, , 0.95, 0, 0,0,,
-394.842-393.078-391.694-391.584-389.482 -387.36-387.281-386.534-385.238-380.566
-380.088-379.889-377.139-372.398 -369.02-368.283-368.214 -366.61-360.702-359.357
-355.203-352.932-349.654-336.764-335.698-335.568-335.379 -332.42-331.803-331.155
-324.779-323.972-323.684-322.309-319.041-310.285-295.471-278.885-260.804-252.167
-244.008-238.369 -227.82-207.378 -178.04-177.293-150.336-120.908 -93.104 -67.393
  -41.93 -15.292 -15.292 -13.797 -13.797  12.851  12.851  14.345  14.345  33.183
  50.208  67.034   89.01 111.863 139.487 171.804 198.831 224.473 227.939 229.444
  230.36 236.068 236.357 236.536 236.676 240.163 245.064 245.821 247.843 249.696
 253.263 254.827 255.942 257.108 259.628 260.057 261.202 261.312
  965.61  965.48   965.2  965.17  964.82  964.33  964.31  964.15  963.82  962.67
  962.55   962.5  961.81  960.86  960.06  959.79  959.77  959.54  958.76  958.49
  957.97  957.72  957.32  955.72   955.6  955.58  955.56  955.24  955.18  955.13
  954.63  954.57  954.55  954.49  954.32  953.81  953.09  952.66  952.26  952.08
  951.99  951.92  951.78   951.7  951.37  951.36  951.11  950.86  950.72  950.97
  951.58  951.75  952.75  952.75  952.75  952.99  952.99  952.99  952.01  952.54
  952.81     953  953.38  954.12  954.95   956.6  958.81  962.92  963.24  963.65
  963.86  964.99  965.04  965.09  965.11   965.8  966.85     967   967.4  967.76
  968.26  968.46  968.49  968.53  968.52  968.56  968.53  968.52
                                                                                
                                                                                
                                                                                
                                                                                
                                                                                
                                  950.13   950.4
                                                                                
                                                                                
                                                                
-394.842-393.078-391.694-391.584-389.482 -387.36-387.281-386.534-385.238-380.566
-380.088-379.889-377.139-372.398 -369.02-368.283-368.214 -366.61-360.702-359.357
-355.203-352.932-349.654-336.764-335.698-335.568-335.379 -332.42-331.803-331.155
-324.779-323.972-323.684-322.309-319.041-310.285-295.471-278.885-260.804-252.167
-244.008-238.369 -227.82-207.378 -178.04-177.293-150.336-120.908 -93.104 -67.393
  -41.93 -15.292 -15.292 -13.797 -13.797  12.851  12.851  14.345  14.345  33.183
  50.208  67.034   89.01 111.863 139.487 171.804 198.831 224.473 227.939 229.444
  230.36 236.068 236.357 236.536 236.676 240.163 245.064 245.821 247.843 249.696
 253.263 254.827 255.942 257.108 259.628 260.057 261.202 261.312
  965.61  965.48   965.2  965.17  964.82  964.33  964.31  964.15  963.82  962.67
  962.55   962.5  961.81  960.86  960.06  959.79  959.77  959.54  958.76  958.49
  957.97  957.72  957.32  955.72   955.6  955.58  955.56  955.24  955.18  955.13
  954.63  954.57  954.55  954.49  954.32  953.81  953.09  952.66  952.26  952.08
  951.99  951.92  951.78   951.7  951.37  951.36  951.11  950.86  950.72  950.97
  951.58  951.75  952.75  952.75  952.75  952.99  952.99  952.99  952.01  952.54
  952.81     953  953.38  954.12  954.95   956.6  958.81  962.92  963.24  963.65
  963.86  964.99  965.04  965.09  965.11   965.8  966.85     967   967.4  967.76
  968.26  968.46  968.49  968.53  968.52  968.56  968.53  968.52
                                                                                
                                                                                
                                                                                
                                                                                
                                                                                
                                  950.12  950.48
                                                                                
                                                                                
                                                                
BR Coef=-1 , 1 , 0 ,, 0 ,,,0.8,0,1.2,0,
WSPro=,,,, 1 ,,,, 0 ,,,, 0 ,,,,-1 ,-1 ,-1 , 0 , 0 , 0 , 0 , 0
BC Design=,, 0 ,, 0 ,,,,,,
BC Use User HTab Curves=0
BC User HTab FreeFlow(D)= 0

Type RM Length L Ch R = 1 ,52495.01,266.9324,292.8095,286.3088
BEGIN DESCRIPTION:
SE. of Midway RD (TWE_28) - DS
END DESCRIPTION:
XS GIS Cut Line= 4
   1489706.00197    1131430.4439   1489576.04495    1131552.7021
    1489423.7769   1131709.37828   1489238.64304   1131895.33465
#Sta/Elev= 30
 -395.19  967.67-377.388  963.99-363.312  960.26-340.171  955.68-305.115  952.89
-255.903  951.56 -82.435  949.41 -43.414  949.82  -36.62  950.36  -26.21  949.84
 -23.311  948.79 -14.714  947.98 -11.665  947.31  -8.019  946.49  -4.573   944.5
   -.269  943.96   3.447  946.11   8.567  947.22  12.602  947.43  21.568  951.23
  31.799  951.29 115.887  953.27 177.363  956.44 191.558  957.56 209.051  960.25
 224.871  961.58 239.276  965.16 246.439  967.95 251.798  968.02 261.601  968.55
#Mann= 7 ,-1,0
 -395.19     .13       0-255.903      .1       0 -14.714     .12       0
 -11.665    .045       0  12.602     .12       0  31.799      .1       0
 251.798     .06       0
#XS Ineff= 2 , 0
       0     -30     952      30       0     952
Permanent Ineff=
       F       F
Bank Sta=-11.665,12.602
XS Rating Curve= 0 ,0
Skew Angle= 5
Exp/Cntr=0.5,0.3

Type RM Length L Ch R = 1 ,52202.20,580.3328,604.5864,567.6392
XS GIS Cut Line= 3
   1489569.14961    1131224.1063   1489243.62795   1131491.03412
   1488978.87073    1131710.2185
#Sta/Elev= 30
 -415.99  983.24 -398.56  978.25 -371.41  968.41  -336.7  957.25 -321.33  951.15
 -307.61  949.14 -162.64  948.88 -146.12  949.58 -134.36     949 -124.73  949.66
   -90.5  949.64  -34.79  948.91  -19.38  950.22  -11.56  948.54   -7.27  944.97
   -4.59  943.53    -.27  942.99    3.46  945.14    7.89  946.15   19.92  947.77
   29.17  950.83   45.66  951.02   156.3  954.36  237.03  958.43  241.47  959.11
  253.75  964.03  268.93  964.66   287.7  963.93  316.36  965.58  348.69  969.64
#Mann= 6 ,-1,0
 -415.99    .135       0   -7.27    .045       0    7.89     .13       0
   45.66      .1       0  253.75     .06       0   287.7     .14       0
Bank Sta=-7.27,7.89
XS Rating Curve= 0 ,0
Exp/Cntr=0.3,0.1

Type RM Length L Ch R = 1 ,51597.62,477.8195,544.9846,510.2537
XS GIS Cut Line= 3
   1489122.10039   1130826.97014   1488825.57119   1131107.73031
   1488659.85958   1131267.50919
#Sta/Elev= 30
 -408.59  978.15 -383.11     979 -361.59  975.05 -334.64  965.25 -312.43  954.81
 -295.09  948.17 -128.75  946.75  -33.94  948.63  -26.98  947.74  -19.68  945.51
   -12.9  945.27  -11.49   943.4   -6.33     941    4.04  941.92    5.72  943.36
    7.54  944.88   18.11  948.65   56.01  949.64      87  952.23   98.42  955.42
   117.8  956.25  124.21  958.31   130.8  962.33  157.96  968.61  183.86  968.35
   203.1   966.4  208.26  966.85  216.66  972.84  226.37  980.17  229.96  980.59
#Mann= 5 ,-1,0
 -408.59    .135       0  -11.49     .04       0    5.72      .1       0
  183.86     .06       0  216.66     .14       0
Bank Sta=-11.49,5.72
XS Rating Curve= 0 ,0
Exp/Cntr=0.3,0.1

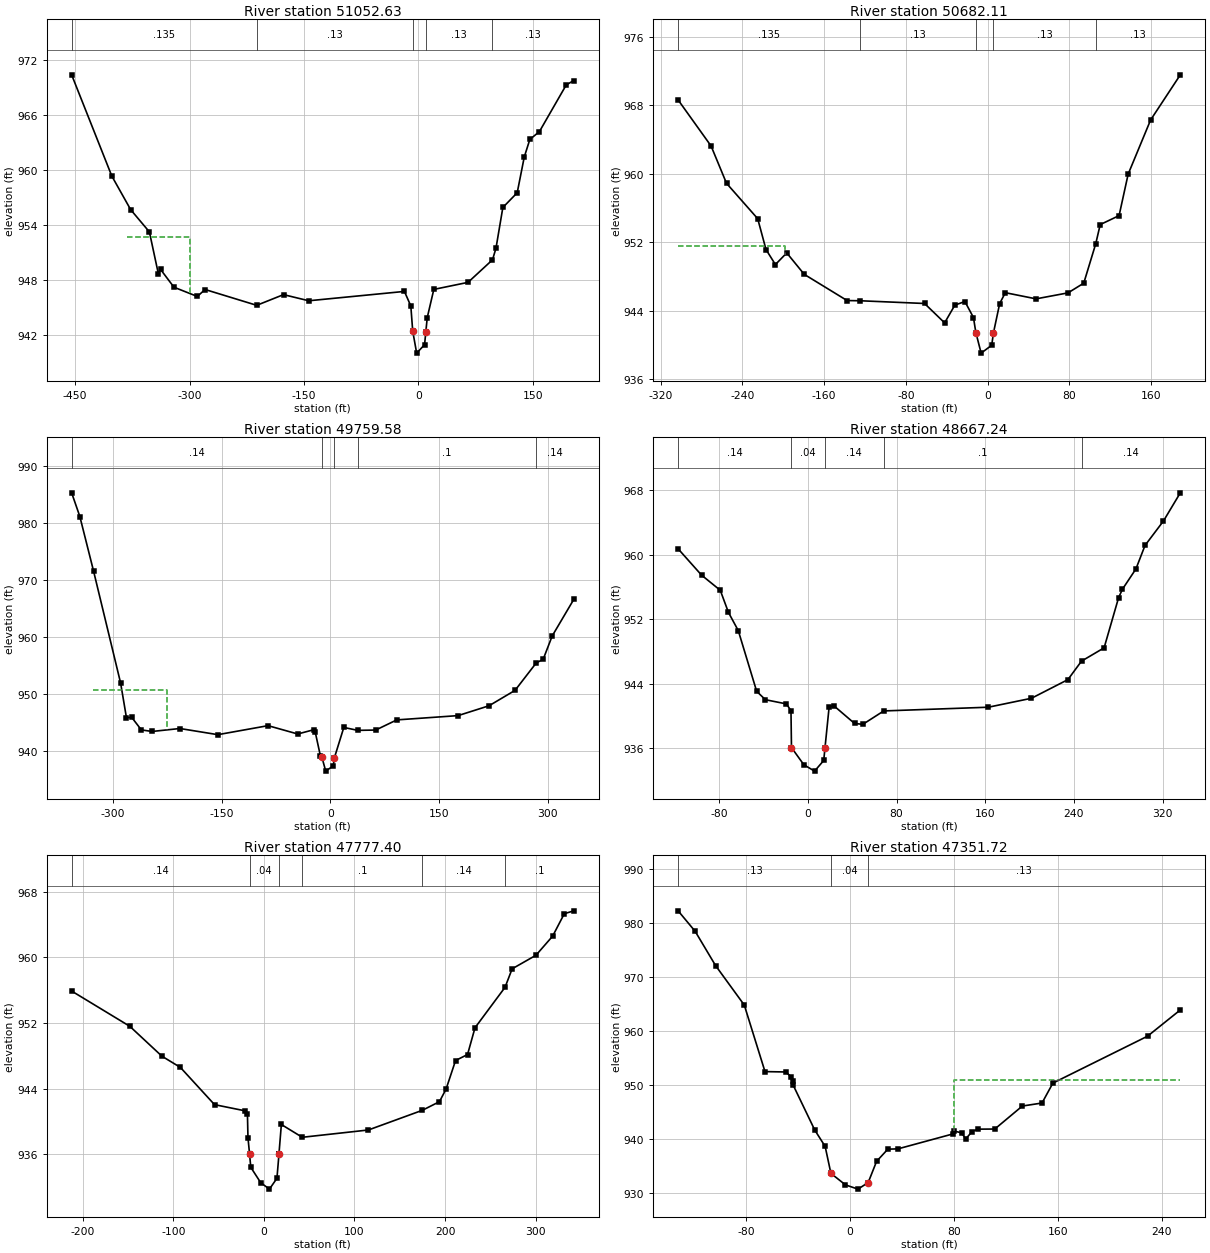
Type RM Length L Ch R = 1 ,51052.63,267.2786,370.5237,365.7625
XS GIS Cut Line= 3
    1488853.0023   1130477.57677   1488484.07808   1130735.82415
   1488316.97703   1130859.52231
#Sta/Elev= 30
 -454.55   970.4  -401.9  959.34 -377.18  955.67 -352.64  953.24 -340.88  948.66
 -338.07  949.15 -320.45   947.2 -289.82  946.19 -279.69  946.95 -211.96945.2222
 -176.86  946.39 -143.77  945.72  -18.37  946.74   -9.99  945.15   -7.49   942.4
   -2.33     940    8.04  940.929.719999  942.36   11.54  943.88   20.15  946.96
      65  947.73   97.07950.1932  101.64  951.46  110.64  955.91  129.46  957.52
   138.7  961.42     146  963.34  158.57   964.2  193.76   969.3  203.69  969.78
#Mann= 5 ,-1,0
 -454.55    .135       0 -211.96     .13       0   -7.49     .04       0
9.719999     .13       0   97.07     .13       0
#XS Ineff= 1 ,-1
 -382.35 -298.78  952.67
Permanent Ineff=
       F
Bank Sta=-7.49,9.719999
XS Rating Curve= 0 ,0
Exp/Cntr=0.3,0.1

Type RM Length L Ch R = 1 ,50682.11,326.1364,434.0806,224.7923
BEGIN DESCRIPTION:
TWE_27X
END DESCRIPTION:
XS GIS Cut Line= 3
   1488695.59252   1130367.49869   1488395.77428    1130407.1332
   1488208.02362   1130428.22802
#Sta/Elev= 30
 -302.81   968.6 -270.56  963.23 -255.47  958.88 -224.94  954.75 -216.81  951.15
 -207.62   949.4 -196.52  950.76 -179.41  948.26 -137.45   945.2    -125  945.18
  -61.69  944.86  -42.05   942.6  -32.04  944.67  -22.21  945.09  -13.84  943.22
  -11.49  941.47   -6.33  939.07    4.04  939.99    5.72  941.43   11.81  944.85
   17.33  946.12   47.41   945.4   78.71   946.1   94.08  947.23  105.84  951.84
  110.16  954.06  128.65  955.11  137.51  959.94  159.47  966.26  188.55  971.53
#Mann= 5 ,-1,0
 -302.81    .135       0    -125     .13       0  -11.49     .04       0
    5.72     .13       0  105.84     .13       0
#XS Ineff= 2 , 0
         -198.26  951.57
Permanent Ineff=
       F       F
Bank Sta=-11.49,5.72
XS Rating Curve= 0 ,0
Exp/Cntr=0.3,0.1

Type RM Length L Ch R = 1 ,49759.58,514.6816,574.8795,496.1618
XS GIS Cut Line= 3
   1488239.93701   1129537.90518   1488001.17782   1129804.57218
   1487777.69619   1130054.39895
#Sta/Elev= 30
 -356.99  985.24 -345.69  981.09 -326.82  971.56 -289.38  951.88 -281.36  945.83
 -274.06  945.88 -260.83  943.69    -246  943.41 -207.57  943.93 -155.19  942.85
  -85.92  944.43  -44.97  942.97  -23.02  943.71  -20.88  943.36  -13.68  939.14
  -11.49  938.86   -6.33  936.46    4.04  937.38    5.72  938.82   18.66  944.12
   37.86943.6053   62.69  943.66   91.78  945.44  176.34  946.19  219.15  947.92
  255.02  950.62  284.33955.4391  293.79  956.05  306.26  960.15  336.14  966.58
#Mann= 5 ,-1,0
 -356.99     .14       0  -11.49     .04       0    5.72     .14       0
   37.86      .1       0  284.33     .14       0
#XS Ineff= 1 ,-1
 -327.79 -225.56  950.71
Permanent Ineff=
       F
Bank Sta=-11.49,5.72
XS Rating Curve= 0 ,0
Exp/Cntr=0.3,0.1

Type RM Length L Ch R = 1 ,48667.24,459.8952,475.5148,473.1491
XS GIS Cut Line= 3
   1487250.35171   1129112.55676   1487186.11549   1129208.91142
   1487001.21916   1129491.02986
#Sta/Elev= 30
 -117.05  960.72  -95.89  957.46  -79.01  955.58  -71.67  952.85  -62.76  950.58
  -46.17  943.06  -38.27  942.02  -19.33   941.5  -15.22  940.66  -14.77  936.09
    -3.6  933.96    6.06  933.17   14.34  934.49   15.44  936.02   19.18  941.09
   23.31  941.29   42.11  939.08   49.62  938.97   68.49  940.63  162.84  941.09
  201.79   942.2  234.63  944.51  246.91   946.8  267.31  948.45  280.41  954.68
  283.83  955.71  296.06  958.24  304.22  961.14  320.86  964.17  336.06  967.66
#Mann= 5 ,-1,0
 -117.05     .14       0  -14.77     .04       0   15.44     .14       0
   68.49      .1       0  246.91     .14       0
Bank Sta=-14.77,15.44
XS Rating Curve= 0 ,0
Exp/Cntr=0.3,0.1

Type RM Length L Ch R = 1 ,47777.40,468.511,425.6777,370.561
XS GIS Cut Line= 3
   1486764.02231   1128491.89567   1486609.07415   1128629.91699
   1486334.33432   1128842.15682
#Sta/Elev= 30
  -212.4   955.9 -148.15   951.6 -112.73  947.96   -92.3  946.59  -54.59  942.05
  -21.47  941.31  -18.25  940.93  -17.65  938.02  -15.86     936  -14.55  934.41
    -3.6  932.54    6.06  931.75   14.34  933.07   16.57  935.98   16.57  936.03
   19.22  939.63   42.34  938.07  115.31  938.96  174.93  941.36  193.82  942.41
  201.21  943.96  211.64  947.43  224.87  948.16   233.1  951.42  266.31  956.36
  274.13  958.61   300.4  960.26   318.9   962.6  331.74  965.33  342.28  965.68
#Mann= 6 ,-1,0
  -212.4     .14       0  -15.86     .04       0   16.57     .14       0
   42.34      .1       0  174.93     .14       0  266.31      .1       0
Bank Sta=-15.86,16.57
XS Rating Curve= 0 ,0
Exp/Cntr=0.3,0.1

Type RM Length L Ch R = 1 ,47351.72,223.5139,243.5831,252.1278
BEGIN DESCRIPTION:
TWE_26X
END DESCRIPTION:
XS GIS Cut Line= 4
   1486278.34449   1128257.52034   1486278.29724   1128391.04462
   1486275.74016     1128478.875   1486118.18766   1128528.35433
#Sta/Elev= 30
 -132.37  982.22 -119.24  978.42 -103.55  972.08  -81.43  964.76  -65.51  952.44
  -49.39  952.37  -45.33  951.45  -44.01  950.76   -43.9  949.98  -27.24  941.63
   -19.2  938.58  -14.77  933.59    -3.6  931.46    6.06  930.67   13.93  931.89
   20.38  935.81   29.03  938.07   36.87  938.13   79.22   940.9   79.64  941.45
   85.77   941.1   89.02  939.98   93.93  941.34   98.42  941.78  111.37   941.8
  132.57  946.06  147.72  946.62  156.08  950.31  228.95     959  254.16  963.86
#Mann= 3 ,-1,0
 -132.37     .13       0  -14.77     .04       0   13.93     .13       0
#XS Ineff= 2 , 0
                           80.12          950.95
Permanent Ineff=
       F       F
Bank Sta=-14.77,13.93
XS Rating Curve= 0 ,0
Exp/Cntr=0.3,0.1

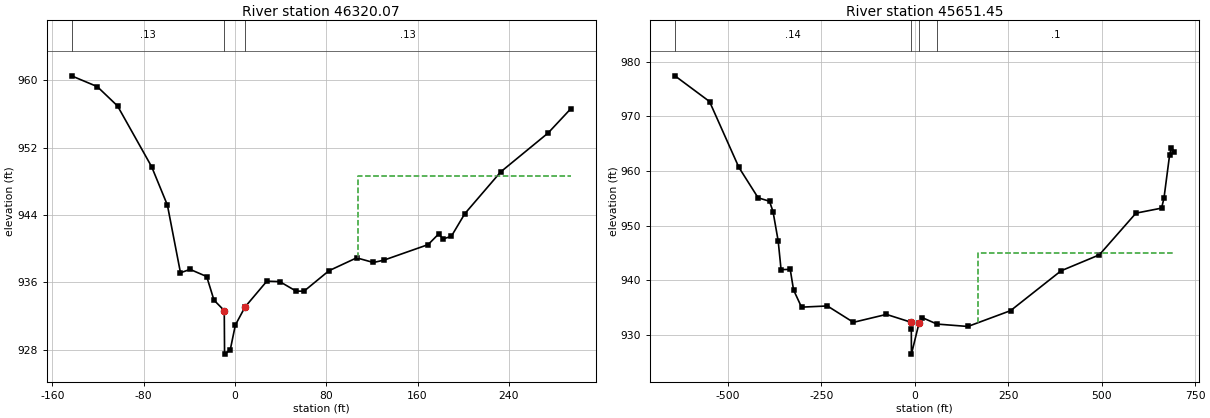
Type RM Length L Ch R = 1 ,46320.07,355.7927,668.618,610.6862
XS GIS Cut Line= 4
   1485380.84941   1127792.95899   1485379.57185   1127937.06726
   1485379.11319    1128128.0292   1485444.48228   1128207.20899
#Sta/Elev= 30
 -143.32  960.53 -120.76  959.25 -102.96  956.95  -73.09  949.74  -59.27  945.18
  -47.81  937.15  -39.37  937.55  -24.83   936.7  -18.44   933.9   -9.43  932.66
   -9.17  927.49   -4.18     928     .28  930.94     8.8  933.09   27.88  936.15
    39.2   936.1   53.54  934.97   60.45  934.96   82.32  937.39  106.58  938.92
  121.29  938.37  130.33  938.64  169.23  940.49  178.52  941.76  182.38  941.17
  189.58  941.47  201.39  944.16  232.91  949.13  274.41  953.74  294.43  956.64
#Mann= 3 ,-1,0
 -143.32     .13       0   -9.43     .04       0     8.8     .13       0
#XS Ineff= 2 , 0
                          107.42          948.64
Permanent Ineff=
       F       F
Bank Sta=-9.43,8.8
XS Rating Curve= 0 ,0
Exp/Cntr=0.3,0.1

Type RM Length L Ch R = 1 ,45651.45,594.5614,684.3304,641.0182
XS GIS Cut Line= 3
   1485248.56266    1127619.9101    1484906.6145   1128163.62927
   1484787.67585   1128847.52559
#Sta/Elev= 30
    -642  977.44 -549.45  972.73 -470.79  960.65 -419.48  955.09 -388.91  954.45
 -379.49  952.55 -365.67  947.16 -357.98  941.92 -333.47  941.96 -324.59   938.2
 -303.25  935.04 -234.06  935.26 -164.41  932.26     -76  933.71   -9.89  932.27
   -9.43   931.1   -9.17  926.43   11.24  932.12    19.5  933.13   59.16  931.94
  141.93   931.5  256.22   934.4  391.24   941.7  493.77  944.63  591.71  952.27
  660.24  953.19  666.64  954.99  681.75  962.92  686.42   964.3  694.47  963.51
#Mann= 4 ,-1,0
    -642     .14       0   -9.89    .045       0   11.24     .14       0
   59.16      .1       0
#XS Ineff= 2 , 0
       0                     170       0     945
Permanent Ineff=
       F       F
Bank Sta=-9.89,11.24
XS Rating Curve= 0 ,0
Exp/Cntr=0.5,0.3