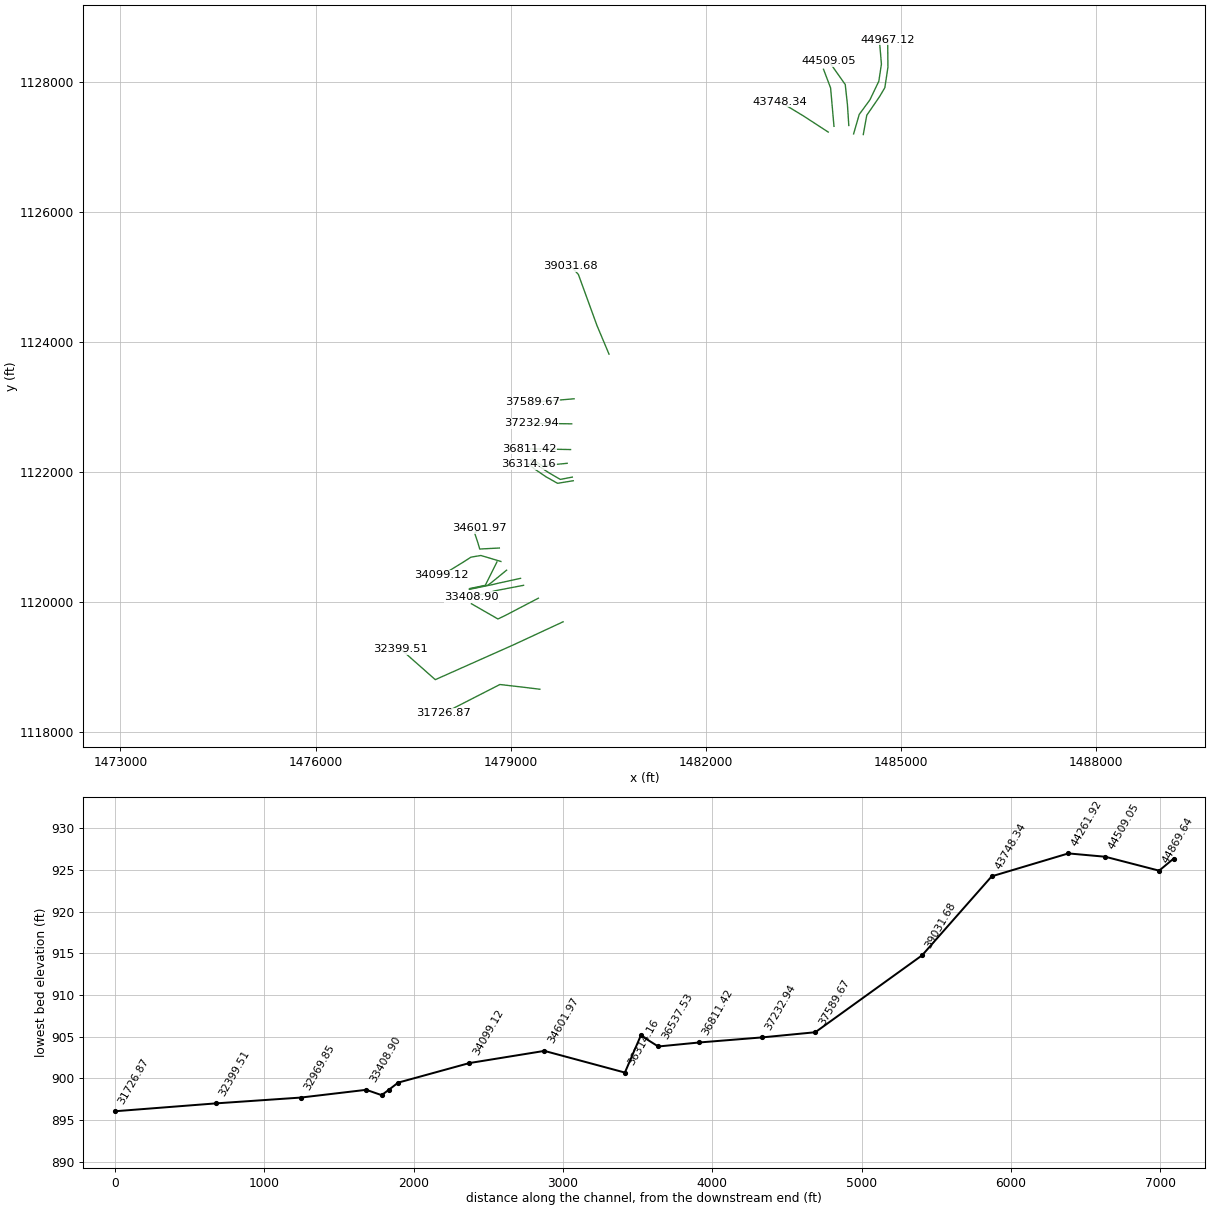
HEC-RAS study 12mile_Combined.prj: 12mile Creek Combined Model

--- 12mile_Combined.g01 (geometry) --- (continued)

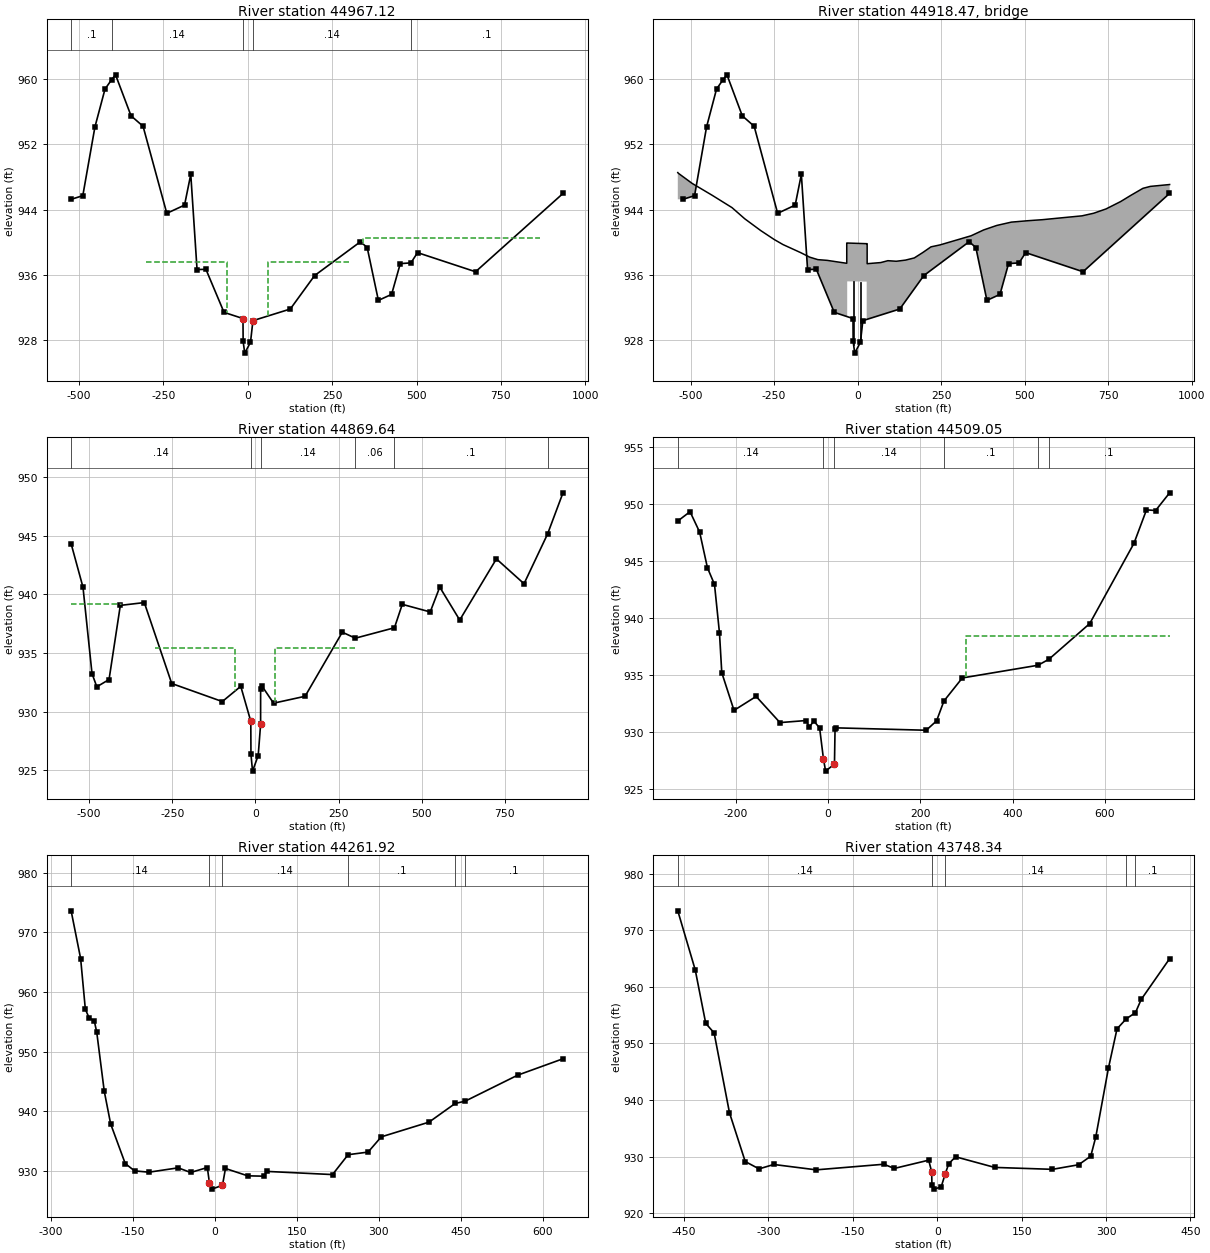
Type RM Length L Ch R = 1 ,44967.12,106.6229,97.47809,96.2407
BEGIN DESCRIPTION:
SC Hwy 178 (TWE_25) - US
END DESCRIPTION:
XS GIS Cut Line= 6
   1484418.68406   1127191.89534   1484472.19357   1127488.53675
   1484670.55512    1127777.4416   1484750.20636    1127913.0643
    1484797.5666   1128227.36483   1484793.26115   1128649.30217
#Sta/Elev= 30
-522.704  945.26-488.133  945.71-452.274  954.15-422.392  958.81-402.527  959.98
-391.194  960.56-345.281  955.52-309.741  954.24-239.452  943.54-186.905  944.55
-168.459  948.33-149.881  936.63-123.598  936.66 -69.979  931.37  -13.86  930.61
 -13.409   927.8  -8.664  926.36   8.382  927.69  15.608  930.35  126.22  931.78
   198.2  935.89 333.929  940.05 353.879  939.34 387.059  932.84 426.207  933.58
  451.87  937.36 483.378  937.45 502.999  938.71 674.812  936.36 933.632  945.98
#Mann= 5 ,-1,0
-522.704      .1       0-402.527     .14       0  -13.86    .045       0
  15.608     .14       0 483.378      .1       0
#XS Ineff= 3 ,-1
    -300     -60   937.5      60     300   937.5  340.45  866.36  940.56
Permanent Ineff=
       F       F       F
Bank Sta=-13.86,15.608
XS Rating Curve= 0 ,0
Skew Angle= 20
Exp/Cntr=0.5,0.3

Type RM Length L Ch R = 3 ,44918.47,,,
BEGIN DESCRIPTION:
SC Hwy 178 (TWE_25) - TOR
Skew = 20 Degrees
END DESCRIPTION:
Bridge Culvert--1,0,-1,-1, 0
Deck Dist Width WeirC Skew NumUp NumDn MinLoCord MaxHiCord MaxSubmerge Is_Ogee
29.1,39.1,2.6,20, 48, 48, 937.35, , 0.95, 0, 0,0,,
-538.369-536.978-495.124 -435.97-376.018 -337.97-290.083 -249.62-223.384-170.526
-149.524-143.923-119.162 -91.254 -32.589 -32.589 -31.179 -31.179  27.091  27.091
  28.501  28.501   69.34  90.511 115.704 142.908   143.2  169.68 195.315 218.873
 219.475 246.716 339.577 377.315 416.453 460.167  509.05 553.357 605.735 638.587
 671.476 706.555 743.607 787.491 817.918 854.011 876.273 934.054
  948.55  948.47  947.21  945.77  944.24  942.87  941.42  940.32   939.7  938.71
  938.28  938.16  937.85  937.76   937.4  939.89  939.89  939.89  939.81  939.81
  939.81  937.35  937.49  937.72  937.65  937.79  937.79  938.06  938.73   939.4
  939.42  939.66  940.78   941.5  942.05  942.46  942.63  942.76  942.97   943.1
  943.23  943.55  944.08  944.99  945.75  946.61  946.85  947.08
                                                                                
                                                          935.18  935.15
                                                                                
                                                                                
                                                                
-554.419-536.978-495.124 -435.97-376.018 -337.97-290.083 -249.62-223.384-170.526
-149.524-143.923-119.162 -91.254 -32.589 -32.589 -31.179 -31.179  27.091  27.091
  28.501  28.501   69.34  90.511 115.704 142.908   143.2  169.68 195.315 218.873
 219.475 246.716 339.577 377.315 416.453 460.167  509.05 553.357 605.735 638.587
 671.476 706.555 743.607 787.491 817.918 854.011 876.273 934.054
  948.55  948.47  947.21  945.77  944.24  942.87  941.42  940.32   939.7  938.71
  938.28  938.16  937.85  937.76   937.4  939.89  939.89  939.89  939.81  939.81
  939.81  937.35  937.49  937.72  937.65  937.79  937.79  938.06  938.73   939.4
  939.42  939.66  940.78   941.5  942.05  942.46  942.63  942.76  942.97   943.1
  943.23  943.55  944.08  944.99  945.75  946.61  946.85  947.08
                                                                                
                                                          935.22  935.14
                                                                                
                                                                                
                                                                
Pier Skew, UpSta & Num, DnSta & Num=  ,-11.934, 4 ,-11.934, 4 , 3 , 3 , 0 ,,
       1       1       2       2
     925  933.18  933.18     936
       1       1       2       2
     925  933.18  933.18     936
Pier Skew, UpSta & Num, DnSta & Num=  ,7.987, 4 ,7.987, 4 , 3 , 3 , 0 ,,
       1       1       2       2
     925  933.18  933.18     936
       1       1       2       2
     925  933.18  933.18     936
Abutment Skew #Up #Dn= , 2 , 2
  -31.18  -22.99
  935.18  931.73
  -31.18  -22.99
  935.18  930.73
Abutment Skew #Up #Dn= , 2 , 2
   21.34   27.09
  930.89  935.15
   21.34   27.09
  930.89  935.14
BR Coef=-1 , 1 , 0 ,, 0 ,,,0.8,0,2,0,
WSPro=,,,, 1 ,,,, 0 ,,,, 0 ,,,,-1 ,-1 ,-1 , 0 , 0 , 0 , 0 , 0
BC Design=,, 0 ,, 0 ,,,,,,
BC Use User HTab Curves=0
BC User HTab FreeFlow(D)= 0

Type RM Length L Ch R = 1 ,44869.64,347.6826,360.594,387.4614
BEGIN DESCRIPTION:
SC Hwy 178 (TWE_25) - DS
END DESCRIPTION:
XS GIS Cut Line= 6
   1484269.63222   1127201.15223   1484356.43832       1127501.5
     1484520.396   1127724.93077   1484657.63845   1128012.09022
   1484697.35728   1128274.56496   1484664.09678    1128670.8294
#Sta/Elev= 30
-553.855  944.32-518.212  940.61-491.121  933.24-476.659  932.11-439.917  932.73
-406.004  939.06-333.939   939.3-251.556  932.39 -99.532  930.85 -44.043  932.15
  -13.86  929.16 -13.409  926.35  -8.664  924.91   8.382  926.24  15.608   928.9
  15.665  931.88  20.504  932.14  54.549  930.71 149.289   931.3 261.141  936.77
  300.41  936.26 417.853  937.15 441.402  939.15 525.354   938.5 554.024  940.62
  614.07  937.81 724.306  943.03 807.337  940.91 878.152  945.16 924.385  948.67
#Mann= 6 ,-1,0
-553.855     .14       0  -13.86    .045       0  15.608     .14       0
  300.41     .06       0 417.853      .1       0 878.152     .06       0
#XS Ineff= 3 ,-1
 -561.64 -403.25   939.2  -300.5   -60.5   935.4      60     300   935.4
Permanent Ineff=
       F       F       F
Bank Sta=-13.86,15.608
XS Rating Curve= 0 ,0
Skew Angle= 20
Exp/Cntr=0.5,0.3

Type RM Length L Ch R = 1 ,44509.05,237.2591,247.1265,233.693
XS GIS Cut Line= 4
   1484195.95112    1127330.7185   1484175.11778   1127648.42749
   1484141.26345   1127960.92815   1483891.26312   1128315.09547
#Sta/Elev= 30
 -325.68  948.48 -299.13   949.3 -278.32  947.51 -261.44  944.39 -246.11  942.93
 -235.34  938.69 -230.32   935.2 -203.83   931.9 -155.84  933.12 -104.17  930.83
  -47.69  931.01  -40.38  930.44  -30.83  930.97  -18.23  930.36    -9.9  927.65
   -5.26  926.58   13.97   927.2   15.23  930.29   17.12  930.37  212.89  930.16
  235.29  930.98  251.25  932.72  291.13  934.74  455.08  935.85  478.61  936.37
  567.32   939.5  663.24  946.53  690.39  949.46  710.08   949.4  740.55  950.95
#Mann= 6 ,-1,0
 -325.68     .14       0    -9.9     .04       0   13.97     .14       0
  251.25      .1       0  455.08     .06       0  478.61      .1       0
#XS Ineff= 2 , 0
                          300.16          938.42
Permanent Ineff=
       F       F
Bank Sta=-9.9,13.97
XS Rating Curve= 0 ,0
Exp/Cntr=0.3,0.1

Type RM Length L Ch R = 1 ,44261.92,355.2933,513.582,597.9077
BEGIN DESCRIPTION:
TWE_24X
END DESCRIPTION:
XS GIS Cut Line= 4
   1483968.18602   1127318.16699    1483945.0351   1127579.95341
   1483916.10269   1127908.64272    1483807.2851   1128195.50033
#Sta/Elev= 30
 -262.81  973.63 -245.44  965.63 -236.81  957.13 -229.54  955.61 -220.51  955.21
 -215.94  953.26 -202.27  943.41 -190.53  937.91 -163.86  931.27 -146.81  930.04
 -120.46  929.82  -67.04  930.55  -44.29  929.77  -13.69   930.6    -9.9  928.05
   -5.26  926.98   14.02  927.63   19.45  930.44   60.13  929.21   89.84  929.15
   95.06  929.95  215.24  929.42  243.76  932.75  280.33  933.19  304.38  935.74
  391.77  938.21  439.57  941.34  457.77  941.72  553.83  946.08  636.76  948.83
#Mann= 6 ,-1,0
 -262.81     .14       0    -9.9     .04       0   14.02     .14       0
  243.76      .1       0  439.57     .06       0  457.77      .1       0
Bank Sta=-9.9,14.02
XS Rating Curve= 0 ,0
Exp/Cntr=0.3,0.1

Type RM Length L Ch R = 1 ,43748.34,466.6915,466.3208,455.0912
XS GIS Cut Line= 3
   1483879.97835   1127229.59022   1483501.50525   1127476.11811
   1483140.39337   1127694.86844
#Sta/Elev= 30
 -460.95  973.45 -429.95     963 -411.31  953.55 -396.37  951.85  -369.1  937.73
 -341.15  929.11 -316.54  927.81 -290.43  928.59    -215  927.64  -94.83  928.63
  -76.25  927.89  -15.18  929.35    -9.9   927.3   -9.38  924.95   -5.26  924.23
    7.09  924.64   13.97  926.85   20.48  928.73   32.65  929.95  102.06  928.07
  204.74  927.73  251.16  928.54   272.8  930.06  281.76  933.48  304.22  945.64
  319.46  952.58  335.97  954.36   352.2  955.44  362.44  957.78  412.94  964.99
#Mann= 5 ,-1,0
 -460.95     .14       0    -9.9    .045       0   13.97     .14       0
  335.97     .06       0   352.2      .1       0
Bank Sta=-9.9,13.97
XS Rating Curve= 0 ,0
Exp/Cntr=0.3,0.1

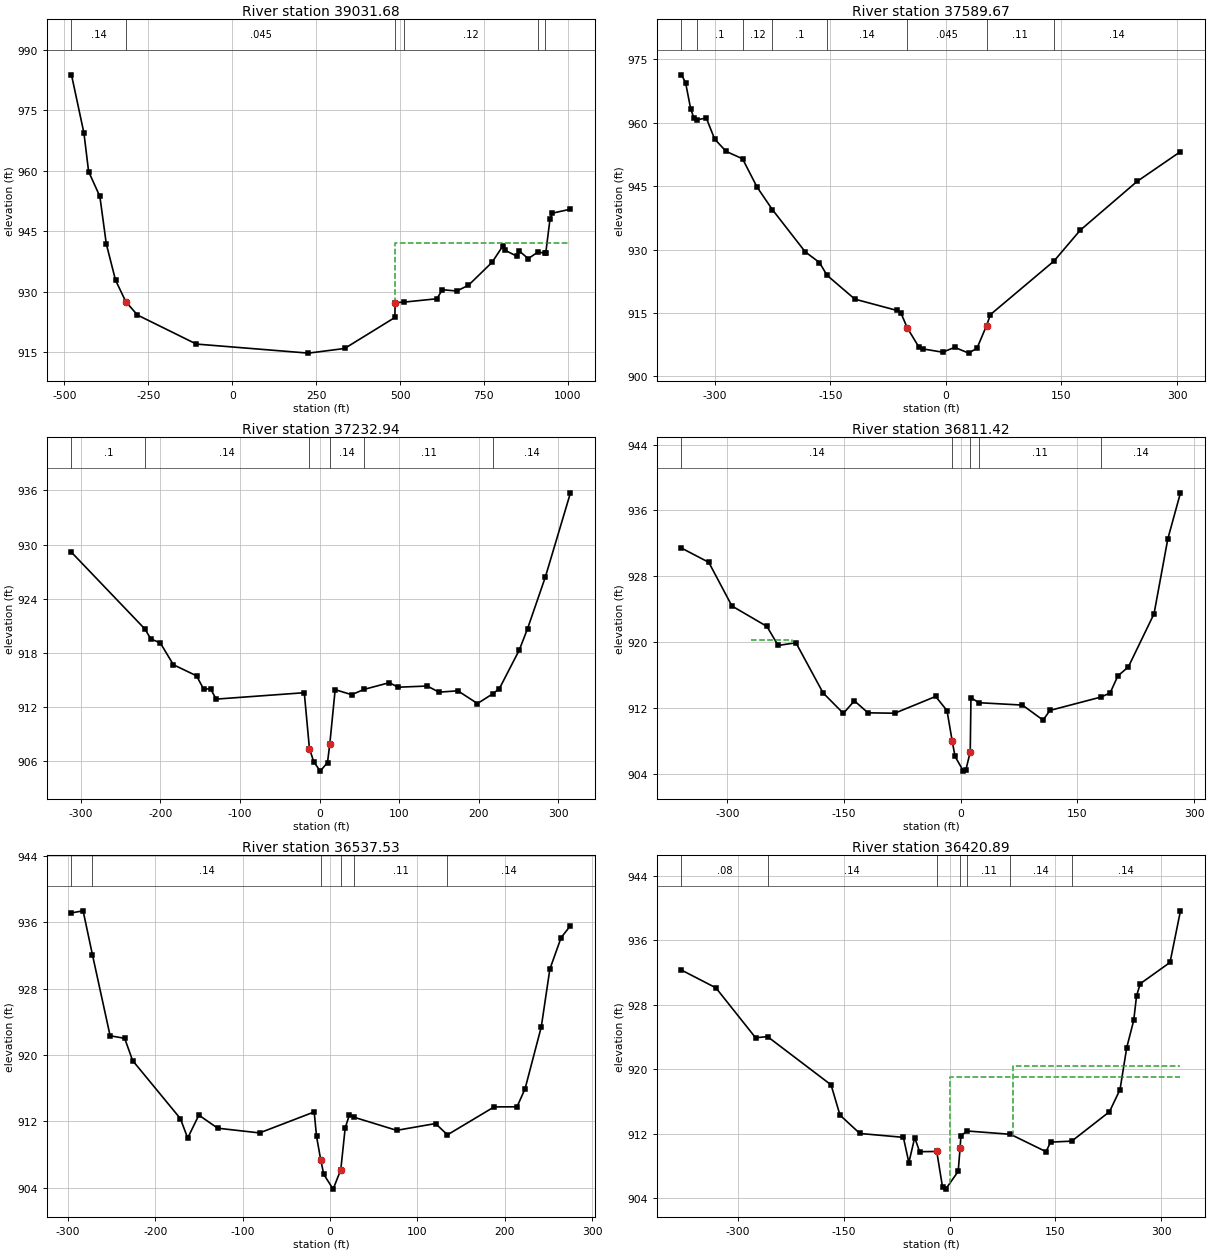
Type RM Length L Ch R = 1 ,39031.68,611.2044,715.2979,1057.36
XS GIS Cut Line= 4
    1480509.8645   1123816.19882   1480325.40256   1124254.56759
   1480039.26969   1125040.27362   1479921.75591   1125170.36811
#Sta/Elev= 30
  -479.1  983.83 -442.03  969.38 -428.07  959.82 -394.54  953.64  -375.3  941.84
 -347.92  932.88  -317.1   927.5  -282.5  924.21    -107     917  227.13  914.75
  334.83   915.9  484.79   923.6  485.34  927.28  510.95   927.4  610.09  928.25
  625.97  930.49   669.3  930.17  704.09   931.6  774.34  937.29  807.23  941.44
  812.52   940.3  848.35  938.81  854.47  940.17  881.96  938.21  911.23  939.84
  930.77  939.57  934.26  939.53  946.86  947.92  953.72  949.48    1008  950.48
#Mann= 6 ,-1,0
  -479.1     .14       0  -317.1    .045       0  485.34     .12       0
  510.95     .12       0  911.23     .06       0  930.77     .14       0
#XS Ineff= 2 , 0
       0                     486       0     942
Permanent Ineff=
       F       F
Bank Sta=-317.1,485.34
XS Rating Curve= 0 ,0
Exp/Cntr=0.3,0.1

Type RM Length L Ch R = 1 ,37589.67,363.8515,356.7317,357.6269
BEGIN DESCRIPTION:
TWE_23DSX
END DESCRIPTION:
XS GIS Cut Line= 3
   1479973.50328   1123130.03314   1479632.30052   1123100.65978
    1479328.1998   1123077.39797
#Sta/Elev= 30
 -343.04  971.32 -337.76  969.48 -331.16  963.31 -326.78  961.02 -322.98  960.68
 -310.89  961.11 -299.98  956.12 -285.18  953.22 -263.85  951.47 -244.91  944.75
 -225.07  939.44 -182.52  929.47 -164.01  926.94  -154.2  923.92 -118.07  918.28
  -63.58  915.62  -58.12  914.94  -50.17  911.52  -35.12  906.99  -29.82  906.52
   -4.23  905.74   11.41  906.88   29.64  905.52   40.45   906.7   52.76  912.02
   57.88  914.64  140.29  927.29  174.27  934.57     248   946.1  304.41  953.16
#Mann= 8 ,-1,0
 -343.04     .12       0 -322.98      .1       0 -263.85     .12       0
 -225.07      .1       0  -154.2     .14       0  -50.17    .045       0
   52.76     .11       0  140.29     .14       0
Bank Sta=-50.17,52.76
XS Rating Curve= 0 ,0
Exp/Cntr=0.3,0.1

Type RM Length L Ch R = 1 ,37232.94,395.0482,421.5169,394.4343
BEGIN DESCRIPTION:
TWE_22X
END DESCRIPTION:
XS GIS Cut Line= 3
   1479936.39403   1122744.77198    1479626.4977    1122749.1122
   1479309.65682   1122751.71621
#Sta/Elev= 30
 -311.63  929.15 -219.22  920.63 -212.03  919.55 -200.11  919.11 -183.63  916.69
 -154.52  915.46 -145.61  913.98    -137  914.03 -129.93  912.88  -19.21  913.59
  -12.75   907.4   -7.41  905.96     .79   904.9    9.96  905.85   12.87  907.94
   19.58  913.93    40.3  913.37   55.93  913.96   87.63   914.7   98.72   914.2
   135.3  914.33  150.02  913.65  173.71   913.8  198.33  912.39  217.61  913.47
   225.9  914.05  250.86  918.32  261.22  920.68  283.65  926.42  315.15  935.74
#Mann= 6 ,-1,0
 -311.63      .1       0 -219.22     .14       0  -12.75    .045       0
   12.87     .14       0   55.93     .11       0  217.61     .14       0
Bank Sta=-12.75,12.87
XS Rating Curve= 0 ,0
Exp/Cntr=0.3,0.1

Type RM Length L Ch R = 1 ,36811.42,230.7124,273.8848,256.8954
XS GIS Cut Line= 3
   1479918.38189   1122349.48031   1479561.39304   1122355.99081
   1479277.10466   1122359.24606
#Sta/Elev= 30
 -358.87  931.41 -323.82  929.68 -294.05  924.37 -249.12  921.89 -234.63  919.57
 -211.79   919.9 -176.88   913.8 -150.77  911.31  -136.7  912.84 -119.13  911.38
  -84.77  911.33  -32.19  913.37  -17.61  911.65  -10.93  907.95   -7.23  906.07
    3.52  904.29    6.77  904.48   12.26  906.63   13.19  913.21    23.4  912.61
   79.36  912.32   105.9  910.49  114.64  911.67  180.43   913.3  192.06   913.8
  201.97  915.86  215.55  916.97   248.5  923.42  266.22  932.53  282.48  938.13
#Mann= 5 ,-1,0
 -358.87     .14       0  -10.93    .045       0   12.26     .14       0
    23.4     .11       0  180.43     .14       0
#XS Ineff= 1 ,-1
 -270.07 -217.01  920.19
Permanent Ineff=
       F
Bank Sta=-10.93,12.26
XS Rating Curve= 0 ,0
Exp/Cntr=0.3,0.1

Type RM Length L Ch R = 1 ,36537.53,214.562,116.6427,97.99628
BEGIN DESCRIPTION:
TWE_21USX
END DESCRIPTION:
XS GIS Cut Line= 4
   1479866.29823    1122137.8914   1479571.85728   1122109.14698
   1479478.92782   1122099.91371   1479331.35794   1122206.25098
#Sta/Elev= 30
 -295.97  937.13 -282.68  937.38 -272.03   932.1 -251.77  922.31 -235.09     922
 -226.01  919.32 -171.35  912.32 -162.97  909.97 -150.18  912.74 -128.64  911.16
  -80.69  910.59  -18.18  913.12  -15.48  910.16  -10.75  907.38   -7.23  905.59
    3.52  903.81   12.26  906.15   17.29  911.18   22.15  912.79   26.89   912.5
   76.22   910.9  120.69  911.72  134.37  910.36  187.82  913.73     214  913.74
  223.19  915.92  241.75  923.38  251.56  930.34  264.37  934.13  275.15  935.59
#Mann= 6 ,-1,0
 -295.97     .08       0 -272.03     .14       0  -10.75    .045       0
   12.26     .14       0   26.89     .11       0  134.37     .14       0
Bank Sta=-10.75,12.26
XS Rating Curve= 0 ,0
Exp/Cntr=0.5,0.3

Type RM Length L Ch R = 1 ,36420.89,77.48199,106.7328,110.8034
BEGIN DESCRIPTION:
Gravley Rd (TWE_21) - US
END DESCRIPTION:
XS GIS Cut Line= 5
   1479945.50066   1121926.00558    1479760.8773   1121890.45833
    1479585.5502   1121992.59678   1479453.26837   1122080.78445
   1479308.38845   1122189.66962
#Sta/Elev= 30
-379.338  932.29-330.627  930.09-274.468   923.9-257.535  924.04-167.636  918.06
-155.041  914.31-126.913  912.03 -65.277  911.55 -57.531  908.42 -49.243  911.52
 -42.317  909.77 -18.063   909.8  -9.823  905.35  -5.457  905.13  12.306  907.33
  14.933   910.2   16.15  911.74  24.902  912.34  86.276  911.93  136.65  909.77
 142.957  910.96 173.007  911.08 226.413  914.73 241.346  917.48 250.861  922.69
 260.713  926.05 264.712  929.08 269.918   930.6 312.091  933.24 326.889  939.64
#Mann= 7 ,-1,0
-379.338     .08       0-257.535     .14       0 -18.063     .04       0
  14.933     .14       0  24.902     .11       0  86.276     .14       0
 173.007     .14       0
#XS Ineff= 2 , 0
       0     -90     919      90       0   920.4
Permanent Ineff=
       F       F
Bank Sta=-18.063,14.933
XS Rating Curve= 0 ,0
Skew Angle= 15
Exp/Cntr=0.5,0.3

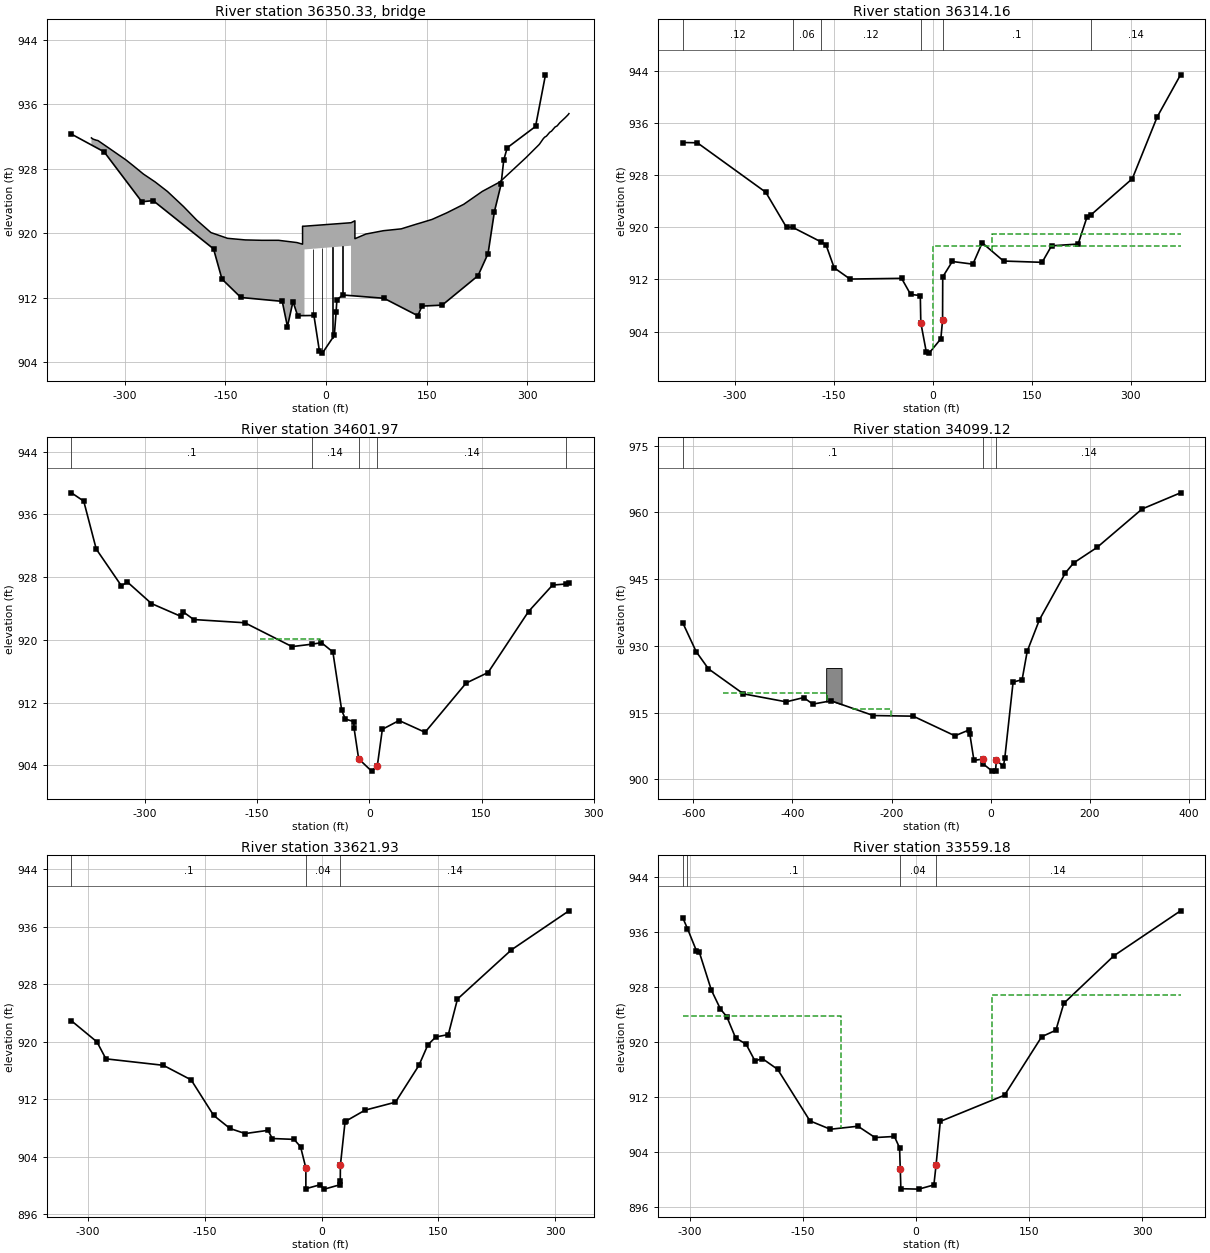
Type RM Length L Ch R = 3 ,36350.33,,,
BEGIN DESCRIPTION:
Gravley Rd (TWE_21) - TOR
Skew = 15 degrees
END DESCRIPTION:
Bridge Culvert--1,0,-1,-1, 0
Deck Dist Width WeirC Skew NumUp NumDn MinLoCord MaxHiCord MaxSubmerge Is_Ogee
56.81,27.5,2.6,15, 68, 68, 918.79, , 0.95, 0, 0,0,,
-349.559-347.579-344.101-343.715-342.817-341.397-339.958 -339.31-323.228-298.268
-287.373 -272.13-254.647-250.146-236.323-212.349-192.741-171.539-167.665-146.888
 -141.73-120.538 -95.801 -70.783  -43.36     -35     -35 -32.175  37.198      43
      43  59.433  85.301 111.931 134.766 140.127  157.89 180.174 204.989 232.836
 258.105 262.162 297.582 317.258 318.157 323.508 325.643 327.797 328.241 328.859
 333.225 335.775 336.026 337.755 341.175 341.358 344.159 344.266 344.884 348.081
 348.622 352.041 352.302 356.195 360.232 360.368 360.735 361.816
  931.82  931.69  931.58  931.58  931.54  931.52  931.49  931.46  930.54   929.1
  928.38  927.34  926.36  926.07  925.18  923.31  921.63  920.08  919.97  919.37
  919.33  919.17  919.12  919.12  918.84  918.64  920.87  920.87   921.3  921.54
  919.32   919.9  920.31  920.54  921.13  921.26  921.71  922.54  923.58  925.19
  926.32  926.61  929.35  930.98  931.07  931.71  931.91  932.01  932.04  932.09
  932.52  932.65  932.67  932.84  933.17  933.18   933.3  933.31  933.37  933.69
  933.73     934  934.02  934.32  934.66  934.67  934.71  934.83
                                                                                
                                                                                
                                                          917.99  918.45
                                                                                
                                                                                
                                                                                
                                                                
-349.559-347.579-344.101-343.715-342.817-341.397-339.958 -339.31-323.228-298.268
-287.373 -272.13-254.647-250.146-236.323-212.349-192.741-171.539-167.665-146.888
 -141.73-120.538 -95.801 -70.783  -43.36     -35     -35 -32.175  37.198      43
      43  59.433  85.301 111.931 134.766 140.127  157.89 180.174 204.989 232.836
 258.105 262.162 297.582 317.258 318.157 323.508 325.643 327.797 328.241 328.859
 333.225 335.775 336.026 337.755 341.175 341.358 344.159 344.266 344.884 348.081
 348.622 352.041 352.302 356.195 360.232 360.368 360.735 361.816
  931.82  931.69  931.58  931.58  931.54  931.52  931.49  931.46  930.54   929.1
  928.38  927.34  926.36  926.07  925.18  923.31  921.63  920.08  919.97  919.37
  919.33  919.17  919.12  919.12  918.84  918.64  920.87  920.87   921.3  921.54
  919.32   919.9  920.31  920.54  921.13  921.26  921.71  922.54  923.58  925.19
  926.32  926.61  929.35  930.98  931.07  931.71  931.91  932.01  932.04  932.09
  932.52  932.65  932.67  932.84  933.17  933.18   933.3  933.31  933.37  933.69
  933.73     934  934.02  934.32  934.66  934.67  934.71  934.83
                                                                                
                                                                                
                                                          917.93  918.43
                                                                                
                                                                                
                                                                                
                                                                
Pier Skew, UpSta & Num, DnSta & Num=  ,-19.319, 2 ,-19.319, 2 , 0 , 0 , 0 ,,
       1       1
     900     920
       1       1
     900     920
Pier Skew, UpSta & Num, DnSta & Num=  ,-5.796, 2 ,-5.796, 2 , 0 , 0 , 0 ,,
       1       1
     900     920
       1       1
     900     920
Pier Skew, UpSta & Num, DnSta & Num=  ,9.659, 2 ,9.659, 2 , 0 , 0 , 0 ,,
       1       1
     900     920
       1       1
     900     920
Pier Skew, UpSta & Num, DnSta & Num=  ,24.148, 2 ,24.148, 2 , 0 , 0 , 0 ,,
       1       1
     900     920
       1       1
     900     920
Abutment Skew #Up #Dn= , 2 , 2
  -32.17  -19.31
  917.99   909.7
  -32.17  -19.31
  917.93     909
Abutment Skew #Up #Dn= , 2 , 2
   24.38    37.2
  912.17  918.45
   24.38    37.2
  912.17  918.43
BR Coef=-1 , 1 , 0 ,, 0 ,,,0.8,0,1.2,0,
WSPro=,,,, 1 ,,,, 0 ,,,, 0 ,,,,-1 ,-1 ,-1 , 0 , 0 , 0 , 0 , 0
BC Design=,, 0 ,, 0 ,,,,,,
BC Use User HTab Curves=0
BC User HTab FreeFlow(D)= 0

Type RM Length L Ch R = 1 ,36314.16,482.54,539.155,447.0775
BEGIN DESCRIPTION:
Gravley Rd (TWE_21) - DS
END DESCRIPTION:
XS GIS Cut Line= 6
   1479960.79856   1121870.21358   1479718.73163   1121830.61909
   1479588.65486   1121904.39829   1479543.20013   1121929.10531
   1479368.80741   1122048.68471    1479274.0351   1122127.02953
#Sta/Elev= 30
-378.604  933.04-356.919     933 -253.15   925.4 -221.68     920-212.591  920.02
-169.269  917.77-162.005  917.37-149.438  913.79-125.368  912.06 -47.214  912.17
 -33.489   909.7 -18.836  909.53 -18.063  905.35  -9.823   900.9  -5.457  900.68
  12.306  902.88  14.933  905.75  15.175  912.39  29.673  914.76  60.892  914.35
  75.033  917.63 107.324  914.83 165.849  914.63 180.213  917.17 220.453  917.44
 233.822  921.56 240.342  921.96 302.625  927.48 340.383  936.98 375.755  943.44
#Mann= 6 ,-1,0
-378.604     .12       0-212.591     .06       0-169.269     .12       0
 -18.063     .04       0  14.933      .1       0 240.342     .14       0
#XS Ineff= 2 , 0
       0     -90   917.2      90       0     919
Permanent Ineff=
       F       F
Bank Sta=-18.063,14.933
XS Rating Curve= 0 ,0
Skew Angle= 15
Exp/Cntr=0.5,0.3

Type RM Length L Ch R = 1 ,34601.97,289.236,502.8473,547.3459
BEGIN DESCRIPTION:
TWE_20X
END DESCRIPTION:
XS GIS Cut Line= 5
   1478823.84186   1120835.94324   1478521.75853   1120820.31824
   1478495.97178   1120910.65584   1478445.07185   1121062.91109
   1478523.19685   1121137.56365
#Sta/Elev= 30
 -398.24  938.75 -381.77  937.69 -365.05  931.58 -331.51  926.91 -323.28  927.37
 -291.28  924.64 -251.56  922.99 -248.45  923.55 -234.73   922.6 -166.45  922.19
 -103.37  919.15  -76.74  919.46  -64.04  919.65  -48.76  918.47  -36.92  911.02
  -32.08  909.92   -20.8  909.59  -20.53  908.82   -14.3  904.85    2.99  903.28
   10.62  903.93   17.39  908.61   39.74  909.73   74.49  908.23  129.34   914.5
  158.73  915.85  212.74  923.62  244.89  926.99   262.5  927.13  266.78  927.22
#Mann= 5 ,-1,0
 -398.24      .1       0  -76.74     .14       0   -14.3     .04       0
   10.62     .14       0   262.5      .1       0
#XS Ineff= 1 ,-1
 -146.55  -66.33  920.15
Permanent Ineff=
       F
Bank Sta=-14.3,10.62
XS Rating Curve= 0 ,0
Exp/Cntr=0.3,0.1

Type RM Length L Ch R = 1 ,34099.12,423.6966,477.193,491.4279
XS GIS Cut Line= 5
   1478848.58169   1120628.91207   1478540.55774   1120720.89633
   1478388.55709   1120695.70276   1478264.29429   1120615.93602
    1477939.4895   1120416.51181
#Sta/Elev= 30
 -620.98  935.04 -594.28  928.66 -569.64  924.82 -499.08   919.2 -412.66   917.4
 -377.43  918.36 -358.97  916.89 -321.91  917.63 -236.84  914.32 -156.29  914.18
  -72.03  909.76  -44.53  911.04  -42.06   910.2  -33.72  904.25  -15.35  904.52
  -14.51   903.4    2.99  901.82    9.86  901.88   11.71   904.3    25.8  902.88
   28.61   904.8   45.34  921.84   63.55  922.38   73.83  928.77   98.55  935.87
  150.67  946.35  167.57  948.64   214.8  952.12  305.81  960.77  383.36   964.4
#Mann= 3 ,-1,0
 -620.98      .1       0  -15.35     .04       0   11.71     .14       0
#XS Ineff= 2 ,-1
 -539.55 -330.22  919.41 -280.39  -201.9915.8724
Permanent Ineff=
       F       F
#Block Obstruct= 1 ,-1
    -332    -301     925
Bank Sta=-15.35,11.71
XS Rating Curve= 0 ,0
Exp/Cntr=0.3,0.1

Type RM Length L Ch R = 1 ,33621.93,97.44409,62.74402,45.65453
BEGIN DESCRIPTION:
TWE_19USX
END DESCRIPTION:
XS GIS Cut Line= 4
   1478787.08629   1120621.93766   1478643.54954   1120333.91404
   1478607.60761   1120262.62959   1478375.24672   1120214.30676
#Sta/Elev= 30
 -321.33  922.92 -288.51  919.98 -277.03  917.62  -203.3  916.72 -167.56  914.69
 -138.64  909.74 -117.69  907.92  -98.17  907.21   -68.9  907.66  -63.32  906.52
  -35.39   906.4  -27.01  905.37  -20.22   902.4  -20.22  899.53   -1.49  900.09
     3.5  899.47   23.59  900.08   23.96  900.62   24.15  902.82    30.1  908.84
   30.76  908.92   55.75  910.47   94.84  911.58  124.99  916.71  136.55  919.59
  146.76  920.67  162.73     921   174.5  925.95  243.86  932.81  317.64  938.24
#Mann= 3 ,-1,0
 -321.33      .1       0  -20.22     .04       0   24.15     .14       0
Bank Sta=-20.22,24.15
XS Rating Curve= 0 ,0
Exp/Cntr=0.3,0.1

Type RM Length L Ch R = 1 ,33559.18,63.0086,47.51963,28.5916
BEGIN DESCRIPTION:
Pipeline Crossing
END DESCRIPTION:
XS GIS Cut Line= 4
   1478935.83169   1120495.33924   1478696.24836    1120300.0269
   1478646.76936   1120264.43668   1478362.91503   1120205.40879
#Sta/Elev= 30
 -309.19  938.03 -303.33  936.55  -291.4  933.31  -287.5  933.08 -271.67   927.6
 -259.58  924.83 -251.08   923.7 -239.51  920.64 -225.43  919.69 -213.76  917.27
 -203.96  917.61 -183.64  916.04 -140.84  908.54 -113.78  907.32  -77.12  907.76
  -54.47  906.11   -28.8  906.27  -21.92  904.62  -21.03  901.56  -20.22  898.66
     3.5   898.6   23.59  899.21   26.52  902.16    32.1  908.46  117.29  912.28
  166.65   920.8  185.42  921.74  195.94  925.66  262.34  932.58  350.79  939.13
#Mann= 4 ,-1,0
 -309.19     .14       0 -303.33      .1       0  -21.03     .04       0
   26.52     .14       0
#XS Ineff= 2 , 0
          -99.88  923.88  100.11          926.93
Permanent Ineff=
       F       F
#XS Lid=2
     -26  905.73  904.73      34  908.46  907.46
Bank Sta=-21.03,26.52
XS Rating Curve= 0 ,0
Exp/Cntr=0.5,0.3

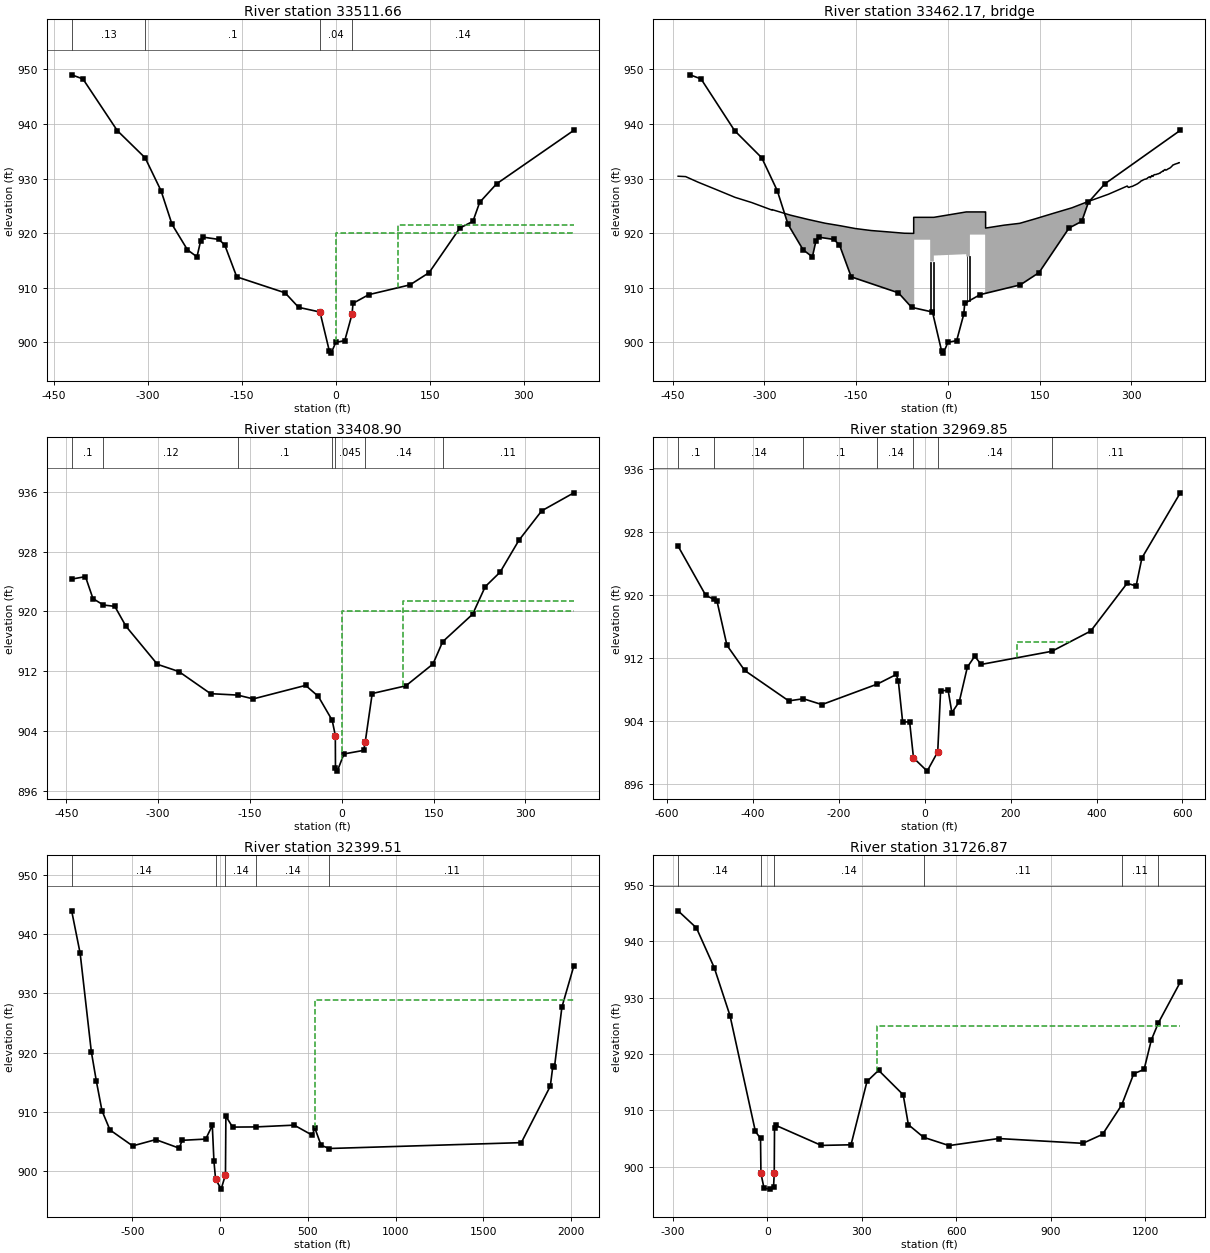
Type RM Length L Ch R = 1 ,33511.66,107.9683,102.7682,116.1268
BEGIN DESCRIPTION:
Red Hill Rd (TWE_19) - US
END DESCRIPTION:
XS GIS Cut Line= 4
   1479149.44029   1120369.55676   1478796.78642   1120292.44554
   1478725.84416   1120274.96719   1478365.99311   1120200.94094
#Sta/Elev= 30
 -421.52  949.02 -403.54  948.27  -348.7  938.79 -304.21  933.79 -278.88  927.76
  -261.3  921.58 -236.68  916.92 -221.52  915.63 -215.57   918.6 -211.48  919.24
  -186.6  918.83 -177.27  917.83 -158.06  911.96  -80.87  909.03  -59.35  906.37
  -25.22  905.51  -10.31  898.37    -7.4  897.97    -.01  899.94   14.34  900.27
   25.92   905.1   27.52  907.11   52.71   908.7  118.42  910.49  148.99  912.74
  198.08  920.92  218.85  922.14  229.67  925.63  256.56  929.02  379.92  938.84
#Mann= 4 ,-1,0
 -421.52     .13       0 -304.21      .1       0  -25.22     .04       0
   25.92     .14       0
#XS Ineff= 2 , 0
       0     -95     920     100       0   921.4
Permanent Ineff=
       F       F
Bank Sta=-25.22,25.92
XS Rating Curve= 0 ,0
Exp/Cntr=0.5,0.3

Type RM Length L Ch R = 3 ,33462.17,,,
BEGIN DESCRIPTION:
Red Hill Rd (TWE_19) - TOR
END DESCRIPTION:
Bridge Culvert--1,0,-1,-1, 0
Deck Dist Width WeirC Skew NumUp NumDn MinLoCord MaxHiCord MaxSubmerge Is_Ogee
31.7,35.6,2.6,0, 103, 103, 919.93, , 0.95, 0, 0,0,,
    -441 -428.71  -408.2 -378.44 -347.84  -320.7 -287.82 -287.65 -276.58  -257.4
 -228.83  -200.7 -176.08 -151.09 -125.57 -100.99     -71  -69.91  -55.92  -55.92
   -55.1   -55.1     -29     -29     -23     -23      30      30      36      36
   60.85   60.85   61.65   61.65   91.71  117.39  142.83  172.23  202.77  228.76
  262.52  293.15  295.02  296.54  297.54  299.14  301.55  304.41  305.72  309.58
  309.73  310.08  312.92  313.45  314.58  316.19  317.35  318.94  319.33  320.89
  322.36  322.88  325.14  326.61  329.44  330.72  331.27  333.02  334.06  335.24
   336.7  338.47  339.91  342.86  343.87  346.44  347.11  347.25  347.33   347.4
  347.64  351.31  351.86  352.79  355.02  356.22  357.58  360.56  360.99  362.61
  364.01  365.35  366.88  367.84  368.95  369.95  370.08  370.32  373.52  374.53
  375.93  376.84  378.12
  930.42  930.35  929.32  927.96  926.54  925.59  924.22   924.3  923.93  923.28
   922.5   921.8  921.34  920.82  920.46  920.24  919.96  919.96  919.93  922.88
  922.88  922.88  922.88  922.88  922.88  922.88  923.87  923.87  923.87  923.87
  923.87  923.87  923.87  920.91  921.44  921.78  922.61  923.61  924.63  925.76
  927.12  928.62  928.37  928.39  928.44  928.51  928.56  928.73  928.79  929.01
  929.02  929.04  929.27  929.29  929.42  929.59  929.61  929.72  929.74  929.83
  929.88  929.88  929.96  930.12  930.32  930.15  930.18  930.51  930.54  930.38
  930.66  930.73  930.72  930.85  930.86  931.01  931.06  931.07  931.08  931.07
   931.1  931.36  931.31  931.48  931.65  931.54  931.59  931.81  931.83   931.9
  932.03  932.16  932.35  932.48  932.51  932.57  932.57  932.59  932.72  932.76
  932.78  932.89   932.9
                                                                                
                                                                                
          918.77  918.77  914.77  914.77  915.87  916.12  915.71  915.71  919.71
  919.71
                                                                                
                                                                                
                                                                                
                                                                                
                                                                                
                                                                                
                        
    -441 -428.71  -408.2 -378.44 -347.84  -320.7 -287.82 -287.65 -276.58  -257.4
 -228.83  -200.7 -176.08 -151.09 -125.57 -100.99     -71  -69.91  -55.92  -55.92
   -55.1   -55.1     -29     -29     -23     -23      30      30      36      36
   60.85   60.85   61.65   61.65   91.71  117.39  142.83  172.23  202.77  228.76
  262.52  293.15  295.02  296.54  297.54  299.14  301.55  304.41  305.72  309.58
  309.73  310.08  312.92  313.45  314.58  316.19  317.35  318.94  319.33  320.89
  322.36  322.88  325.14  326.61  329.44  330.72  331.27  333.02  334.06  335.24
   336.7  338.47  339.91  342.86  343.87  346.44  347.11  347.25  347.33   347.4
  347.64  351.31  351.86  352.79  355.02  356.22  357.58  360.56  360.99  362.61
  364.01  365.35  366.88  367.84  368.95  369.95  370.08  370.32  373.52  374.53
  375.93  376.84  378.12
  930.42  930.35  929.32  927.96  926.54  925.59  924.22   924.3  923.93  923.28
   922.5   921.8  921.34  920.82  920.46  920.24  919.96  919.96  919.93  922.88
  922.88  922.88  922.88  922.88  922.88  922.88  923.87  923.87  923.87  923.87
  923.87  923.87  923.87  920.91  921.44  921.78  922.61  923.61  924.63  925.76
  927.12  928.62  928.37  928.39  928.44  928.51  928.56  928.73  928.79  929.01
  929.02  929.04  929.27  929.29  929.42  929.59  929.61  929.72  929.74  929.83
  929.88  929.88  929.96  930.12  930.32  930.15  930.18  930.51  930.54  930.38
  930.66  930.73  930.72  930.85  930.86  931.01  931.06  931.07  931.08  931.07
   931.1  931.36  931.31  931.48  931.65  931.54  931.59  931.81  931.83   931.9
  932.03  932.16  932.35  932.48  932.51  932.57  932.57  932.59  932.72  932.76
  932.78  932.89   932.9
                                                                                
                                                                                
          918.04  918.04  914.04  914.04  915.87  916.12     915     915     919
     919
                                                                                
                                                                                
                                                                                
                                                                                
                                                                                
                                                                                
                        
Pier Skew, UpSta & Num, DnSta & Num=  ,-28, 2 ,-28, 2 , 0 , 0 , 0 ,,
       1       1
     900     920
       1       1
     900     920
Pier Skew, UpSta & Num, DnSta & Num=  ,-24, 2 ,-24, 2 , 0 , 0 , 0 ,,
       1       1
     900     920
       1       1
     900     920
Pier Skew, UpSta & Num, DnSta & Num=  ,31, 2 ,31, 2 , 0 , 0 , 0 ,,
       1       1
     900     920
       1       1
     900     920
Pier Skew, UpSta & Num, DnSta & Num=  ,35, 2 ,35, 2 , 0 , 0 , 0 ,,
       1       1
     900     920
       1       1
     900     920
Abutment Skew #Up #Dn= , 2 , 2
   -55.1     -28
  918.77  905.71
   -55.1     -28
  918.04  905.71
Abutment Skew #Up #Dn= , 2 , 2
      35   60.85
  907.19  919.71
      35   60.85
   901.3     919
BR Coef=-1 , 1 , 0 ,, 0 ,,,0.8,0,1.2,0,
WSPro=,,,, 1 ,,,, 0 ,,,, 0 ,,,,-1 ,-1 ,-1 , 0 , 0 , 0 , 0 , 0
BC Design=,, 0 ,, 0 ,,,,,,
BC Use User HTab Curves=0
BC User HTab FreeFlow(D)= 0

Type RM Length L Ch R = 1 ,33408.90,429.2785,439.0403,382.9909
BEGIN DESCRIPTION:
Red Hill Rd (TWE_19) - DS
END DESCRIPTION:
XS GIS Cut Line= 4
   1479196.73491   1120262.62959    1478751.5479   1120177.29364
   1478683.69029    1120155.7021    1478396.8376   1120082.70407
#Sta/Elev= 30
 -441.35  924.32  -418.8  924.65 -406.53  921.71 -389.49  920.85 -370.85  920.67
 -352.57     918 -301.24  912.91 -266.13  911.94 -214.34  908.98 -170.13  908.79
  -144.6  908.28   -59.1  910.09  -38.37  908.62   -15.7  905.42  -10.55  903.38
  -10.31  899.01    -7.4  898.61    3.59  900.91   35.77  901.39   38.33  902.52
   49.71     909  104.67  910.03  148.98  912.95  164.79  915.93  213.77  919.62
   234.4  923.31   258.7  925.25  289.41  929.52  326.65  933.46  379.15  935.87
#Mann= 7 ,-1,0
 -441.35      .1       0 -389.49     .12       0 -170.13      .1       0
   -15.7     .14       0  -10.55    .045       0   38.33     .14       0
  164.79     .11       0
#XS Ineff= 2 , 0
       0     -95     920     100       0   921.4
Permanent Ineff=
       F       F
Bank Sta=-10.55,38.33
XS Rating Curve= 0 ,0
Exp/Cntr=0.5,0.3

Type RM Length L Ch R = 1 ,32969.85,484.9809,570.3428,730.3533
BEGIN DESCRIPTION:
TWE_18X
END DESCRIPTION:
XS GIS Cut Line= 4
   1479424.24049   1120064.64501   1478916.31004   1119799.55643
   1478802.59646   1119744.93504   1478394.60925   1119979.31037
#Sta/Elev= 30
 -574.55  926.21 -510.05  919.96 -491.04  919.48 -483.93  919.23 -460.83  913.64
 -419.51  910.45 -316.93  906.59  -282.9  906.86 -239.66  906.12  -110.2  908.73
   -66.5  909.94  -61.66  909.11  -51.57   903.9  -35.39  903.94  -26.34  899.36
    5.51  897.68   30.09  900.12   36.77  907.86   54.33  907.94   63.08  905.09
   80.32   906.5   99.14  910.88   116.4  912.26  130.95  911.21  295.85  912.88
  386.46  915.45  471.21  921.51   492.1  921.16  505.67  924.72  595.07  932.98
#Mann= 7 ,-1,0
 -574.55      .1       0 -491.04     .14       0  -282.9      .1       0
  -110.2     .14       0  -26.34    .045       0   30.09     .14       0
  295.85     .11       0
#XS Ineff= 1 ,-1
  213.92  341.07  914.02
Permanent Ineff=
       F
Bank Sta=-26.34,30.09
XS Rating Curve= 0 ,0
Exp/Cntr=0.3,0.1

Type RM Length L Ch R = 1 ,32399.51,860.4338,672.6442,491.1495
XS GIS Cut Line= 4
   1479803.44718   1119701.43241   1479038.20407   1119345.88878
   1477839.47474   1118812.22146   1477310.60564   1119279.52165
#Sta/Elev= 30
 -846.45  943.91 -797.99  936.74 -734.41  920.17 -705.66  915.19 -673.51  910.19
 -628.11  906.96 -498.89  904.27  -367.3  905.33 -232.78  903.88 -217.24  905.21
  -82.52  905.42  -44.92  907.72  -35.56  901.66  -26.34  898.66    5.51  896.98
   30.09  899.42   32.44  909.28   70.56  907.44  202.93  907.47  421.67  907.77
  523.88  906.09  539.76  907.25  575.06  904.37  620.99  903.83  1715.9  904.82
 1881.24  914.35 1895.79  917.75    1905  917.61 1947.41   927.7 2015.25  934.62
#Mann= 5 ,-1,0
 -846.45     .14       0  -26.34     .04       0   30.09     .14       0
  202.93     .14       0  620.99     .11       0
#XS Ineff= 2 , 0
       0                     540       0  928.95
Permanent Ineff=
       F       F
Bank Sta=-26.34,30.09
XS Rating Curve= 0 ,0
Exp/Cntr=0.3,0.1

Type RM Length L Ch R = 1 ,31726.87,456.2632,481.3701,514.452
XS GIS Cut Line= 4
   1479447.31332   1118664.81759   1479171.27165   1118698.67192
   1478832.72999   1118737.73425   1477964.48294   1118293.91273
#Sta/Elev= 30
 -282.94  945.44 -224.86  942.41 -168.33  935.36 -118.29  926.84  -37.69  906.29
  -21.37  905.03  -20.05  898.82  -10.23  896.21    8.91  896.04   20.01  896.46
   22.16  898.82   23.04  906.92   26.77  907.37  171.64   903.8  265.84  903.91
  316.62  915.16  353.44  917.13  431.47  912.79  447.93  907.48  496.22905.2398
  577.02  903.77  734.25  905.02 1001.59  904.17 1064.16  905.76 1124.92 910.963
 1163.22  916.52 1196.18  917.29 1219.13  922.52 1241.71925.5745 1311.07  932.79
#Mann= 6 ,-1,0
 -282.94     .14       0  -20.05     .04       0   22.16     .14       0
  496.22     .11       0 1124.92     .11       0 1241.71     .14       0
#XS Ineff= 2 , 0
       0                  348.07       0     925
Permanent Ineff=
       F       F
Bank Sta=-20.05,22.16
XS Rating Curve= 0 ,0
Exp/Cntr=0.3,0.1