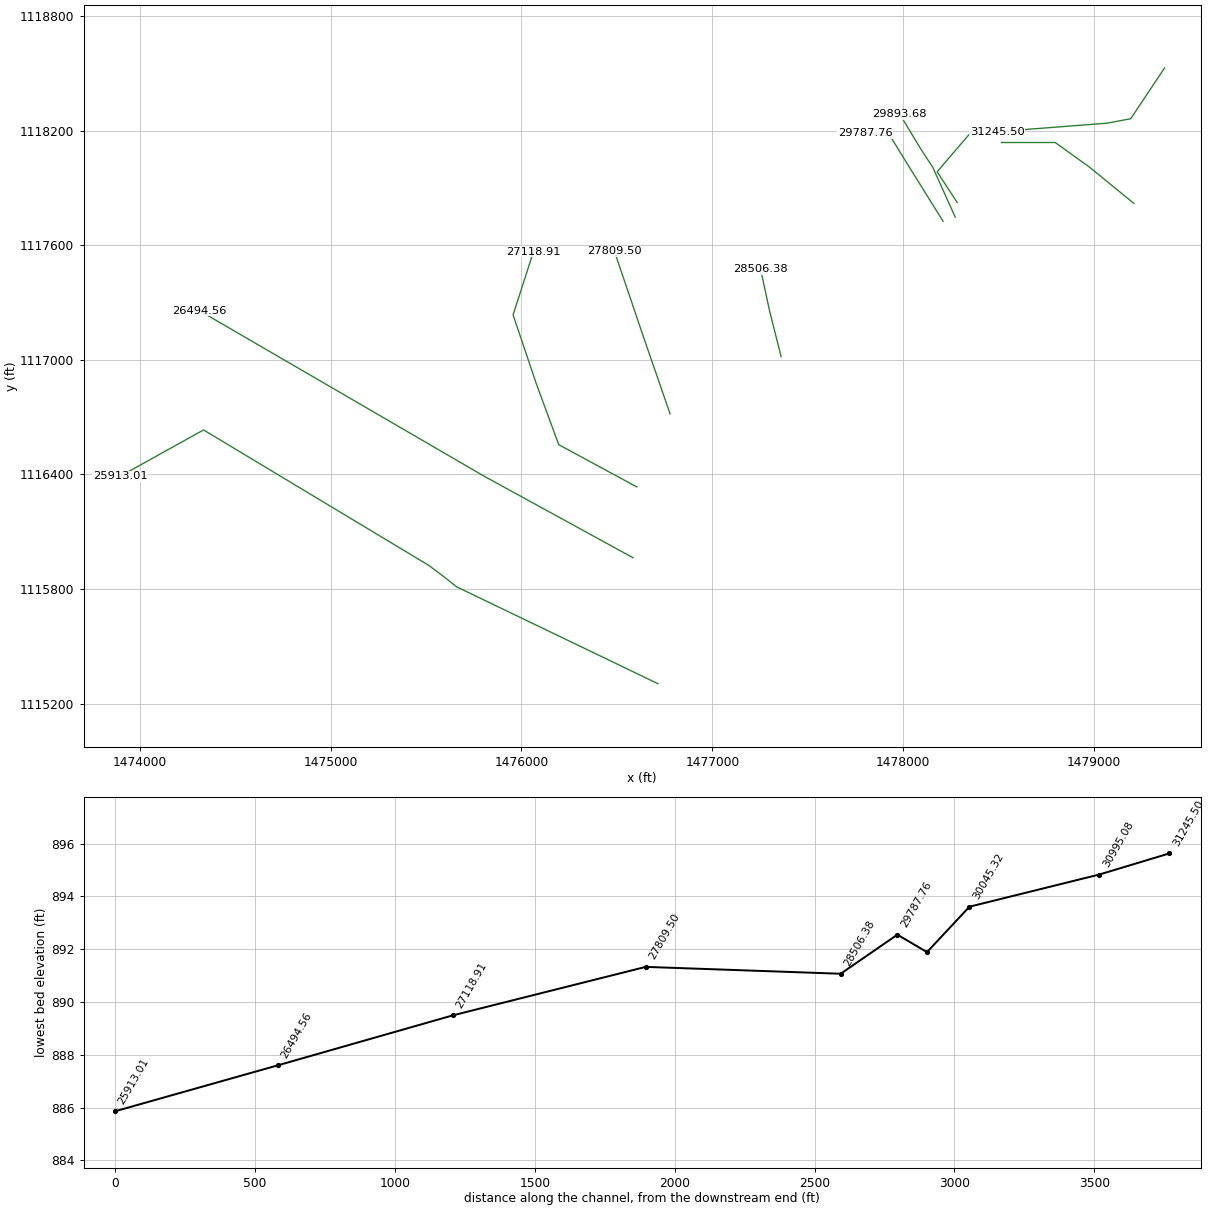
HEC-RAS study 12mile_Combined.prj: 12mile Creek Combined Model

--- 12mile_Combined.g01 (geometry) --- (continued)

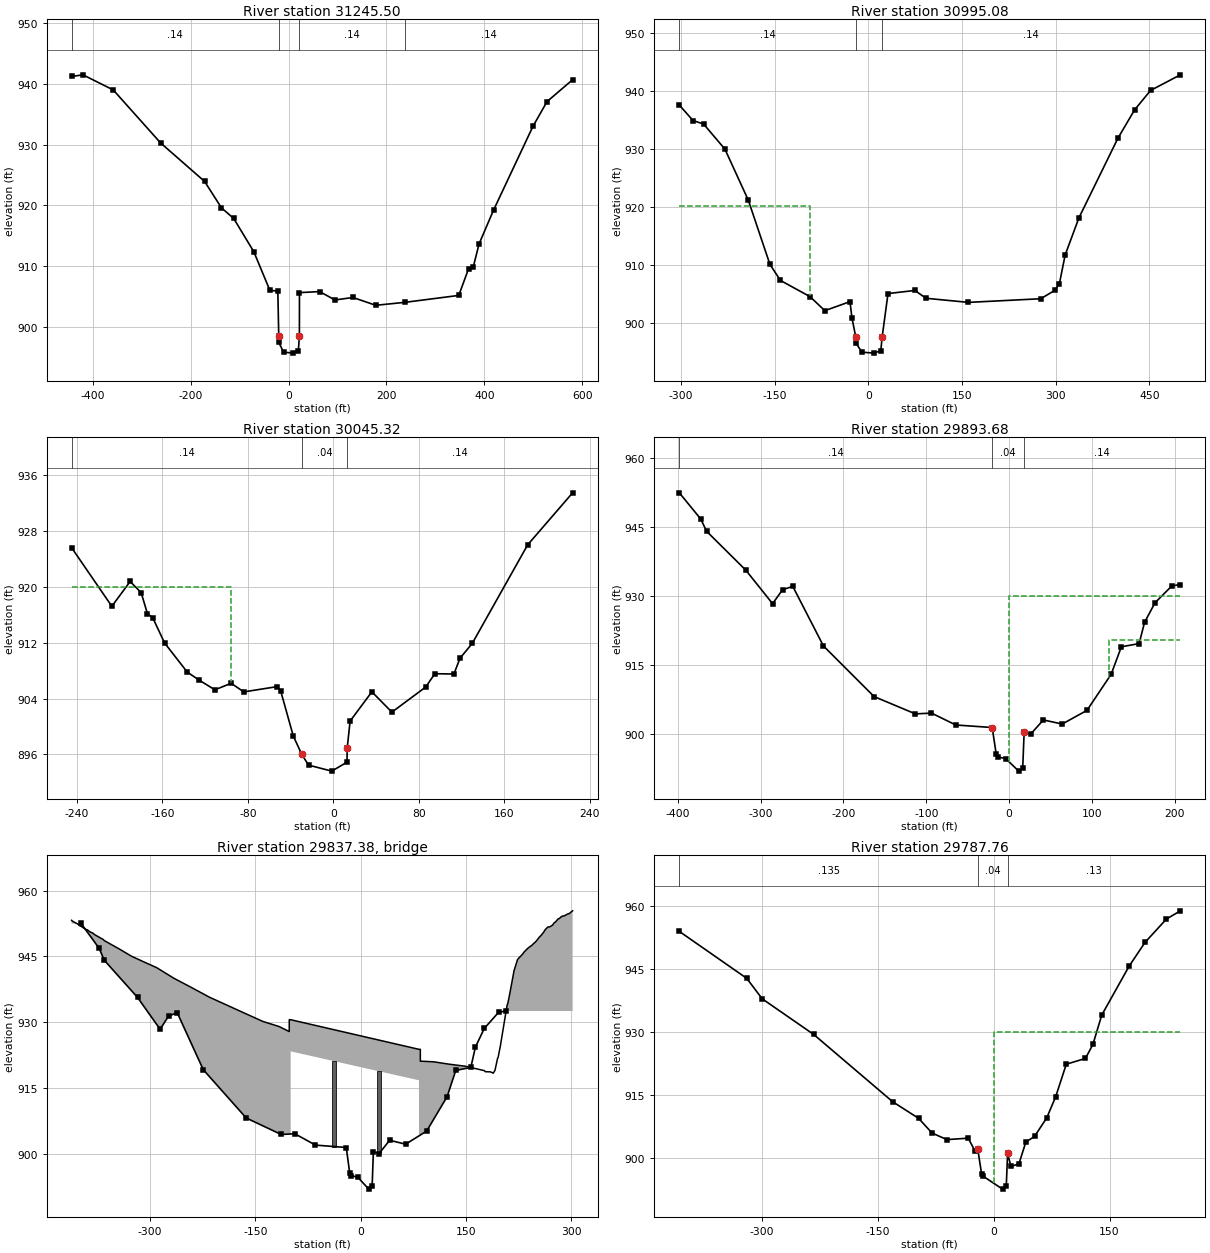
Type RM Length L Ch R = 1 ,31245.50,294.3723,250.416,146.7567
XS GIS Cut Line= 4
   1479369.18832   1118529.40092   1479192.10499   1118263.77592
   1479067.10499   1118240.33858   1478491.58399   1118196.06759
#Sta/Elev= 30
  -443.3  941.22 -420.09  941.49 -358.18     939 -261.37  930.26 -171.51  923.92
 -137.08  919.57 -112.07  917.82  -71.05  912.35   -38.1  905.96  -21.93  905.86
  -20.05  898.41  -19.93  897.39  -10.23   895.8    8.91  895.63   20.01  896.05
   22.16  898.41   22.28   905.6   63.49  905.77   94.81  904.39  131.58   904.8
  178.27  903.51  238.59904.0079  347.75  905.14  367.78  909.53  377.48  909.85
  389.24  913.63  418.78  919.19  499.21  932.98  528.07  937.08  580.34  940.68
#Mann= 4 ,-1,0
  -443.3     .14       0  -20.05     .04       0   22.16     .14       0
  238.59     .14       0
Bank Sta=-20.05,22.16
XS Rating Curve= 0 ,0
Exp/Cntr=0.3,0.1

Type RM Length L Ch R = 1 ,30995.08,457.8576,464.3595,353.1964
BEGIN DESCRIPTION:
TWE_17X
END DESCRIPTION:
XS GIS Cut Line= 4
   1479208.09285   1117820.67388   1478974.16339   1118011.68602
   1478796.23425   1118139.20538    1478515.0351   1118139.11155
#Sta/Elev= 30
 -302.51   937.6  -280.7  934.94 -263.64  934.33 -229.52     930 -192.14  921.21
  -157.6  910.16 -140.75  907.37  -93.15  904.56  -69.63  902.15  -29.29  903.71
   -26.2   900.9  -20.05  897.61  -19.93  896.59  -10.23     895    8.91  894.83
   20.01  895.25   22.16  897.61   31.55   905.1   74.58  905.64   92.34  904.29
  160.27  903.58  275.99  904.21  298.57  905.65  305.91   906.8  315.14  911.75
  337.22  918.17  399.48  931.86  426.34  936.78  451.92  940.13   499.6  942.82
#Mann= 3 ,-1,0
 -302.51     .14       0  -20.05     .04       0   22.16     .14       0
#XS Ineff= 2 , 0
          -93.87  920.13
Permanent Ineff=
       F       F
Bank Sta=-20.05,22.16
XS Rating Curve= 0 ,0
Exp/Cntr=0.3,0.1

Type RM Length L Ch R = 1 ,30045.32,97.19073,151.6482,202.5759
BEGIN DESCRIPTION:
TWE_16USX
END DESCRIPTION:
XS GIS Cut Line= 4
   1478282.83957   1117824.84547   1478178.07054     1117985.479
   1478212.42881   1118026.38156        1478358.   1118196.01345
#Sta/Elev= 30
 -244.99  925.59 -207.34   917.2  -190.2  920.75 -179.89  919.15 -173.99  916.12
 -169.03  915.55 -157.98  911.95  -136.8  907.79 -125.96  906.66 -110.93  905.25
   -95.7  906.18  -83.89  904.95  -52.41  905.71  -49.39   905.1  -37.59  898.64
  -29.78  896.05  -23.32  894.47   -1.57  893.61   12.66  894.89   12.87  896.92
   15.57  900.77   35.94  904.96   54.69  902.05   86.41  905.66    94.8  907.55
  112.69  907.51  118.41  909.77  129.86  911.89  181.72     926  223.74  933.44
#Mann= 3 ,-1,0
 -244.99     .14       0  -29.78     .04       0   12.87     .14       0
#XS Ineff= 2 , 0
          -96.08  920.03
Permanent Ineff=
       F       F
Bank Sta=-29.78,12.87
XS Rating Curve= 0 ,0
Exp/Cntr=0.5,0.3

Type RM Length L Ch R = 1 ,29893.68,109.4181,105.9196,106.1071
BEGIN DESCRIPTION:
Reece Mill Rd (TWE_16) - US
END DESCRIPTION:
XS GIS Cut Line= 4
   1478272.65551   1117748.29692   1478155.16437   1118008.97999
   1478091.17356   1118107.06398   1477982.04626   1118287.61352
#Sta/Elev= 30
 -398.03  952.52-372.287  946.83-365.108  944.14-317.729  935.65-285.496  928.37
-273.461  931.41-261.132  932.14-224.123  919.16-162.976  908.13-113.085  904.36
 -93.714  904.53 -64.357  901.94 -20.464  901.39  -15.58  895.57 -13.777     895
  -4.018   894.6  11.562  891.89  16.377  892.52   18.12  900.43  26.344  900.02
  41.303  903.04  64.081  902.15  93.961  905.13 123.071  912.97  135.46  918.98
  156.87  919.67 163.468  924.32 176.074  928.57 196.371  932.24 206.662  932.54
#Mann= 3 ,-1,0
 -398.03     .14       0 -20.464     .04       0   18.12     .14       0
#XS Ineff= 2 , 0
       0    -140     930     120       0   920.4
Permanent Ineff=
       F       F
Bank Sta=-20.464,18.12
XS Rating Curve= 0 ,0
Skew Angle= 10
Exp/Cntr=0.5,0.3

Type RM Length L Ch R = 3 ,29837.38,,,
BEGIN DESCRIPTION:
Reece Mill Rd (TWE_16) - TOR
Skew = 10 Degrees
END DESCRIPTION:
Bridge Culvert--1,0,-1,-1, 0
Deck Dist Width WeirC Skew NumUp NumDn MinLoCord MaxHiCord MaxSubmerge Is_Ogee
38.75,35.1,2.6,10, 145, 145, 919.17, , 0.95, 0, 0,0,,
-411.591-411.413-410.911-409.247-405.879-405.337-404.766-403.584-403.555-403.417
-399.221-397.902-397.754-397.242-394.031-393.204-392.357-390.654-389.147-386.803
-386.488-386.439 -386.36-384.804-383.376-382.421-381.711-380.215-378.521 -377.27
-374.276-373.872-372.425-371.657-369.401-366.989-365.964-365.186-342.467-326.523
-310.175-290.558-265.819-243.228-215.328-191.604-164.148-139.153-116.099-101.652
-101.652 -99.682 -99.682  83.039  83.039  85.009  85.009 103.996 125.061 149.159
 171.179 176.261 177.551 180.643 180.722 180.791 182.928 183.539 184.415 185.636
 185.814 188.187 188.807 191.299 194.992 195.731 198.921  206.79 207.942 208.307
 208.543 209.498 210.572 212.167 217.258  218.45  221.03 223.413 224.162  224.94
 226.998 227.313 228.436 228.456 231.046 232.159 232.454 232.927 236.462 237.004
 238.648 240.933 243.395 244.449 245.621 247.128 248.408 250.013 251.845 252.347
  253.49 254.839 256.542 258.286 260.738 261.979 262.865 265.819 267.178 268.793
 268.981 269.118 270.123 272.605 273.363 275.579 275.992 277.115 278.996 280.454
 281.212 282.246 283.004  285.19 286.353 286.874 289.888 292.941  293.65 294.054
 297.373  297.52 298.535 301.184 301.824
  953.25   953.2  953.11  952.95   952.6   952.6  952.55  952.49  952.49  952.47
  951.92  951.92  951.91  951.78  951.45  951.33  951.27  951.14  951.08  950.78
  950.75  950.74  950.73  950.56  950.46   950.4  950.36  950.17  949.95  949.83
  949.58  949.56   949.4  949.32  949.11  948.92  948.78  948.63  946.59  945.07
  943.86  942.45  940.01  938.11   935.7  933.96  931.97  930.16     929  927.86
  930.56  930.56  930.56   923.8   923.8   923.8   921.1  920.95  920.43  919.94
  919.12  918.93  918.69  918.66  918.66  918.66  918.66  918.66  918.67  918.58
  918.58  918.42  918.35  919.01  921.75  921.93  924.52  932.27  933.41  933.72
   933.9  934.22  935.03  936.34  940.64  941.76  943.05   944.3  944.42  944.58
  944.93  944.94  945.16  945.16  945.61   945.9  945.95  946.03  946.62  946.71
  946.94   947.2  947.47  947.63  947.84  948.07  948.22   948.5  948.88  948.98
   949.2  949.48  949.73  950.05  950.58  950.91  951.12  951.61  951.75  951.73
  951.73  951.74  951.83  952.07  952.19  952.68  952.72  952.83  953.15  953.44
  953.57  953.61  953.66  954.01  954.07   954.2  954.26  954.51  954.59  954.63
  954.82  954.84  954.99  955.36  955.41
                                                                                
                                                                                
                                                                                
                                                                                
                                                                                
                  923.34  916.73
                                                                                
                                                                                
                                                                                
                                                                                
                                                                                
                                                                                
                                                                                
                                                                                
                                        
-411.591-411.413-410.911-409.247-405.879-405.337-404.766-403.584-403.555-403.417
-399.221-397.902-397.754-397.242-394.031-393.204-392.357-390.654-389.147-386.803
-386.488-386.439 -386.36-384.804-383.376-382.421-381.711-380.215-378.521 -377.27
-374.276-373.872-372.425-371.657-369.401-366.989-365.964-365.186-342.467-326.523
-310.175-290.558-265.819-243.228-215.328-191.604-164.148-139.153-116.099-101.652
-101.652 -99.682 -99.682  83.039  83.039  85.009  85.009 103.996 125.061 149.159
 171.179 176.261 177.551 180.643 180.722 180.791 182.928 183.539 184.415 185.636
 185.814 188.187 188.807 191.299 194.992 195.731 198.921  206.79 207.942 208.307
 208.543 209.498 210.572 212.167 217.258  218.45  221.03 223.413 224.162  224.94
 226.998 227.313 228.436 228.456 231.046 232.159 232.454 232.927 236.462 237.004
 238.648 240.933 243.395 244.449 245.621 247.128 248.408 250.013 251.845 252.347
  253.49 254.839 256.542 258.286 260.738 261.979 262.865 265.819 267.178 268.793
 268.981 269.118 270.123 272.605 273.363 275.579 275.992 277.115 278.996 280.454
 281.212 282.246 283.004  285.19 286.353 286.874 289.888 292.941  293.65 294.054
 297.373  297.52 298.535 301.184 301.824
  953.25   953.2  953.11  952.95   952.6   952.6  952.55  952.49  952.49  952.47
  951.92  951.92  951.91  951.78  951.45  951.33  951.27  951.14  951.08  950.78
  950.75  950.74  950.73  950.56  950.46   950.4  950.36  950.17  949.95  949.83
  949.58  949.56   949.4  949.32  949.11  948.92  948.78  948.63  946.59  945.07
  943.86  942.45  940.01  938.11   935.7  933.96  931.97  930.16     929  927.86
  930.56  930.56  930.56   923.8   923.8   923.8   921.1  920.95  920.43  919.94
  919.12  918.93  918.69  918.66  918.66  918.66  918.66  918.66  918.67  918.58
  918.58  918.42  918.35  919.01  921.75  921.93  924.52  932.27  933.41  933.72
   933.9  934.22  935.03  936.34  940.64  941.76  943.05   944.3  944.42  944.58
  944.93  944.94  945.16  945.16  945.61   945.9  945.95  946.03  946.62  946.71
  946.94   947.2  947.47  947.63  947.84  948.07  948.22   948.5  948.88  948.98
   949.2  949.48  949.73  950.05  950.58  950.91  951.12  951.61  951.75  951.73
  951.73  951.74  951.83  952.07  952.19  952.68  952.72  952.83  953.15  953.44
  953.57  953.61  953.66  954.01  954.07   954.2  954.26  954.51  954.59  954.63
  954.82  954.84  954.99  955.36  955.41
                                                                                
                                                                                
                                                                                
                                                                                
                                                                                
                  923.41  916.69
                                                                                
                                                                                
                                                                                
                                                                                
                                                                                
                                                                                
                                                                                
                                                                                
                                        
Pier Skew, UpSta & Num, DnSta & Num=  ,-37.423, 4 ,-37.423, 4 , 3 , 3 , 0 ,,
       4       4       6       6
     900     919     919     922
       4       4       6       6
     900     919     919     922
Pier Skew, UpSta & Num, DnSta & Num=  ,26.59, 4 ,26.59, 4 , 3 , 3 , 0 ,,
       4       4       6       6
     900     917     917     919
       4       4       6       6
     900     917     917     919
Abutment Skew #Up #Dn= , 2 , 2
  -99.68     -39
  923.34  901.83
  -99.68     -39
  923.34  901.83
Abutment Skew #Up #Dn= , 2 , 2
   26.34   83.04
  900.02  916.73
   26.34   83.04
  897.68  916.69
BR Coef=-1 , 1 , 0 ,, 0 ,,,0.8,0,1.2,0,
WSPro=,,,, 1 ,,,, 0 ,,,, 0 ,,,,-1 ,-1 ,-1 , 0 , 0 , 0 , 0 , 0
BC Design=,, 0 ,, 0 ,,,,,,
BC Use User HTab Curves=0
BC User HTab FreeFlow(D)= 0

Type RM Length L Ch R = 1 ,29787.76,135.3192,202.6774,209.5373
BEGIN DESCRIPTION:
Reece Mill Rd (TWE_16) - DS
END DESCRIPTION:
XS GIS Cut Line= 4
   1478209.16765   1117726.30545   1477987.82644   1118081.65387
    1477932.0479   1118173.25098   1477800.65157   1118189.38812
#Sta/Elev= 30
-406.617  953.96-319.353  942.77-299.401   937.9 -232.72   929.4-130.625  913.38
 -97.023  909.42 -79.622  905.91 -60.369  904.35 -32.873  904.69 -24.128  901.66
 -20.464  902.05  -15.58  896.23 -13.777  895.66  11.562  892.55  16.377  893.18
   18.12  901.09  22.365  897.97  32.686  898.54  41.746  903.78  52.924   905.1
   68.74  909.52  80.301  914.56  94.049  922.32 118.788  923.69 128.468  927.02
 139.941  934.03 175.542  945.74 195.908  951.34 223.601  956.91 241.662  958.87
#Mann= 3 ,0,0
-406.617    .135       0 -20.464     .04       0   18.12     .13       0
#XS Ineff= 2 , 0
       0    -140     930     120       0     920
Permanent Ineff=
       F       F
Bank Sta=-20.464,18.12
XS Rating Curve= 0 ,0
Skew Angle= 10
Exp/Cntr=0.5,0.3

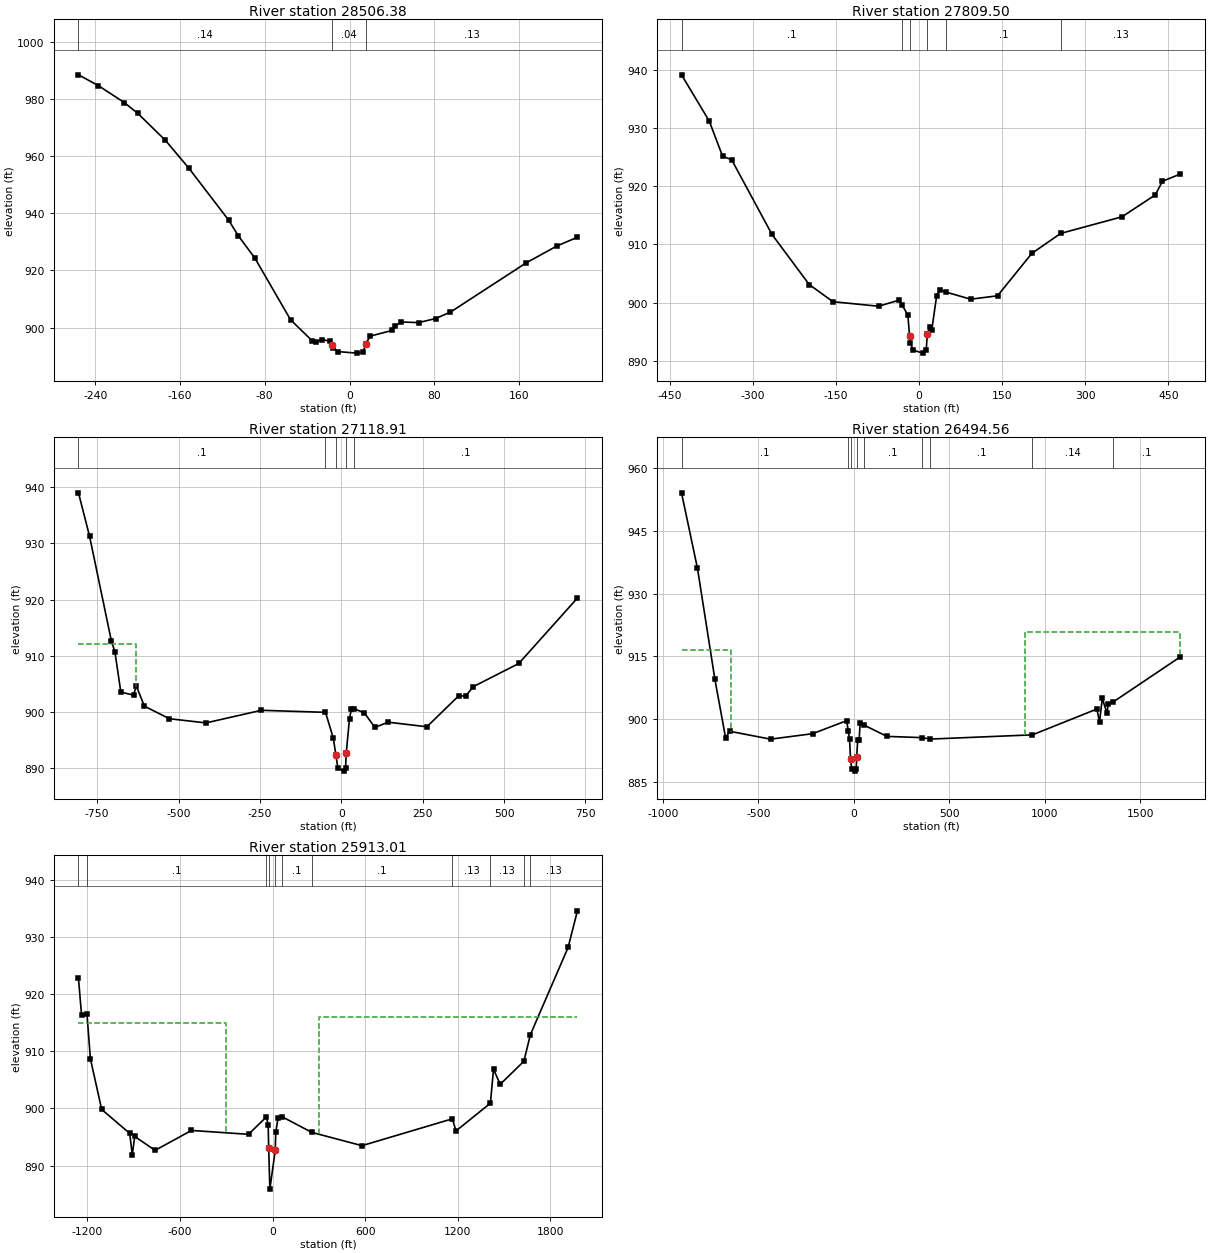
Type RM Length L Ch R = 1 ,28506.38,675.5677,696.8746,683.6249
XS GIS Cut Line= 3
   1477360.45735   1117017.59744   1477299.69324   1117258.91765
   1477252.81791   1117475.93176
#Sta/Elev= 30
 -255.76  988.36 -237.05   984.6 -212.58  978.68 -199.74  974.87 -173.68  965.43
 -151.56  955.71 -114.07  937.56 -105.09  932.18  -89.26  924.26  -55.66  902.75
  -35.54  895.48  -31.78  894.86  -26.23  895.81  -18.85  895.28  -16.84  893.97
  -15.63  892.87  -10.51  891.59    6.95  891.07   13.06  891.54   15.18  894.36
   19.73  897.03   40.34  899.02   42.94  900.56    48.8  901.96   65.29  901.74
   81.17  903.16    95.1  905.37  166.96  922.68  195.92  928.56  215.11  931.58
#Mann= 3 ,-1,0
 -255.76     .14       0  -16.84     .04       0   15.18     .13       0
Bank Sta=-16.84,15.18
XS Rating Curve= 0 ,0
Exp/Cntr=0.3,0.1

Type RM Length L Ch R = 1 ,27809.50,648.7662,690.5974,614.9048
XS GIS Cut Line= 3
    1476778.8586   1116717.68406   1476635.62959   1117131.74705
    1476487.1916   1117569.24803
#Sta/Elev= 30
 -428.32  939.11 -378.33  931.18 -354.24  925.13 -337.93  924.54 -265.07   911.7
 -197.96  903.11 -155.14  900.16  -72.85  899.38  -35.26  900.44  -30.62  899.62
  -20.04  897.87  -16.84  894.23  -15.63  893.13  -10.51  891.85    6.95  891.33
   13.06   891.8   15.18  894.62      20  895.82   22.98  895.22      32   901.2
   37.12  902.15   49.36  901.79   93.27  900.59  141.78  901.17  203.64  908.45
  255.63  911.88  366.47  914.74  426.27  918.49  439.29  920.83  471.81  922.09
#Mann= 6 ,-1,0
 -428.32      .1       0  -30.62     .12       0  -16.84    .045       0
   15.18     .12       0   49.36      .1       0  255.63     .13       0
Bank Sta=-16.84,15.18
XS Rating Curve= 0 ,0
Exp/Cntr=0.3,0.1

Type RM Length L Ch R = 1 ,27118.91,335.1646,624.3409,764.4692
BEGIN DESCRIPTION:
TWE_15X
END DESCRIPTION:
XS GIS Cut Line= 5
   1476604.37927   1116334.87041   1476195.52428   1116556.22539
   1476077.06693    1116877.9626   1475956.37434   1117235.91404
   1476062.71161   1117566.64403
#Sta/Elev= 30
 -807.49     939 -773.33  931.24 -706.15  912.57 -695.71  910.75 -677.36  903.54
 -638.16  903.02 -629.96  904.67 -605.11  901.05 -528.12  898.81 -415.78  898.07
 -245.71  900.31  -48.63  899.95  -24.53  895.35  -16.84  892.39  -10.51  890.01
    6.95  889.49   13.06  889.96   15.18  892.78   25.14  898.82   31.07  900.55
   39.67  900.58   70.61  899.86   103.3  897.26  143.47   898.2  262.92  897.38
  361.15  902.92  381.55  902.81  405.36  904.51  545.26  908.64  725.44  920.28
#Mann= 5 ,-1,0
 -807.49      .1       0  -48.63     .12       0  -16.84    .045       0
   15.18     .12       0   39.67      .1       0
#XS Ineff= 2 , 0
         -631.09  912.19
Permanent Ineff=
       F       F
Bank Sta=-16.84,15.18
XS Rating Curve= 0 ,0
Exp/Cntr=0.3,0.1

Type RM Length L Ch R = 1 ,26494.56,575.6857,581.5507,592.2119
XS GIS Cut Line= 3
   1476584.84777   1115963.77625   1475807.93701   1116389.12434
   1474314.87795   1117257.18143
#Sta/Elev= 30
 -901.87   954.1 -818.26  936.03 -727.05  909.53 -671.11  895.56 -649.38  897.12
 -435.53  895.24 -214.75  896.55  -36.95  899.66  -28.71  897.23  -21.88  895.16
  -16.84   890.5  -10.51  888.12    6.95   887.6   13.06  888.07   15.18  890.89
   20.89  895.07   28.15  894.97   33.45  899.07   56.12  898.55  173.89   895.9
  354.96  895.61  401.79  895.26   935.7  896.27 1273.45  902.44 1286.94  899.35
 1301.65  904.96 1325.94  901.46 1332.65  903.54 1356.64  904.07 1710.92  914.93
#Mann= 9 ,-1,0
 -901.87      .1       0  -28.71     .12       0  -16.84    .045       0
   15.18     .12       0   56.12      .1       0  354.96     .14       0
  401.79      .1       0   935.7     .14       0 1356.64      .1       0
#XS Ineff= 2 , 0
         -640.37  916.44  898.15          920.86
Permanent Ineff=
       F       F
Bank Sta=-16.84,15.18
XS Rating Curve= 0 ,0
Exp/Cntr=0.3,0.1

Type RM Length L Ch R = 1 ,25913.01,85.88181,110.4947,145.8901
BEGIN DESCRIPTION:
TWE_14USX
END DESCRIPTION:
XS GIS Cut Line= 6
   1476715.05643   1115304.05249   1475660.69915    1115811.4416
   1475593.04396   1115864.89698    1475514.5315   1115923.92126
   1474334.68832   1116633.46621   1473897.18734   1116390.41043
#Sta/Elev= 30
-1256.71   922.8-1237.02  916.43-1201.79  916.62 -1179.8  908.75 -1106.5  899.83
 -925.01  895.64  -908.3  891.91 -892.27  895.09 -760.54  892.66  -524.8  896.15
 -155.33  895.47  -39.15  898.54  -28.22  897.12  -24.72  893.03  -17.13  885.86
   17.58  892.64   21.18  895.85   35.94  898.36   63.37  898.53  254.61  895.81
  579.62  893.48 1165.01  898.19 1188.41  896.06 1411.34  900.93 1431.63  906.89
 1474.59  904.23 1628.11  908.28 1670.38  912.95 1914.45  928.23 1975.08  934.66
#Mann= 11 ,-1,0
-1256.71     .12       0-1201.79      .1       0  -39.15     .12       0
  -24.72    .045       0   17.58     .12       0   63.37      .1       0
  254.61      .1       0 1165.01     .13       0 1411.34     .13       0
 1628.11      .1       0 1670.38     .13       0
#XS Ineff= 2 , 0
         -299.48  915.05  300.29          916.01
Permanent Ineff=
       F       F
Bank Sta=-24.72,17.58
XS Rating Curve= 0 ,0
Exp/Cntr=0.5,0.3