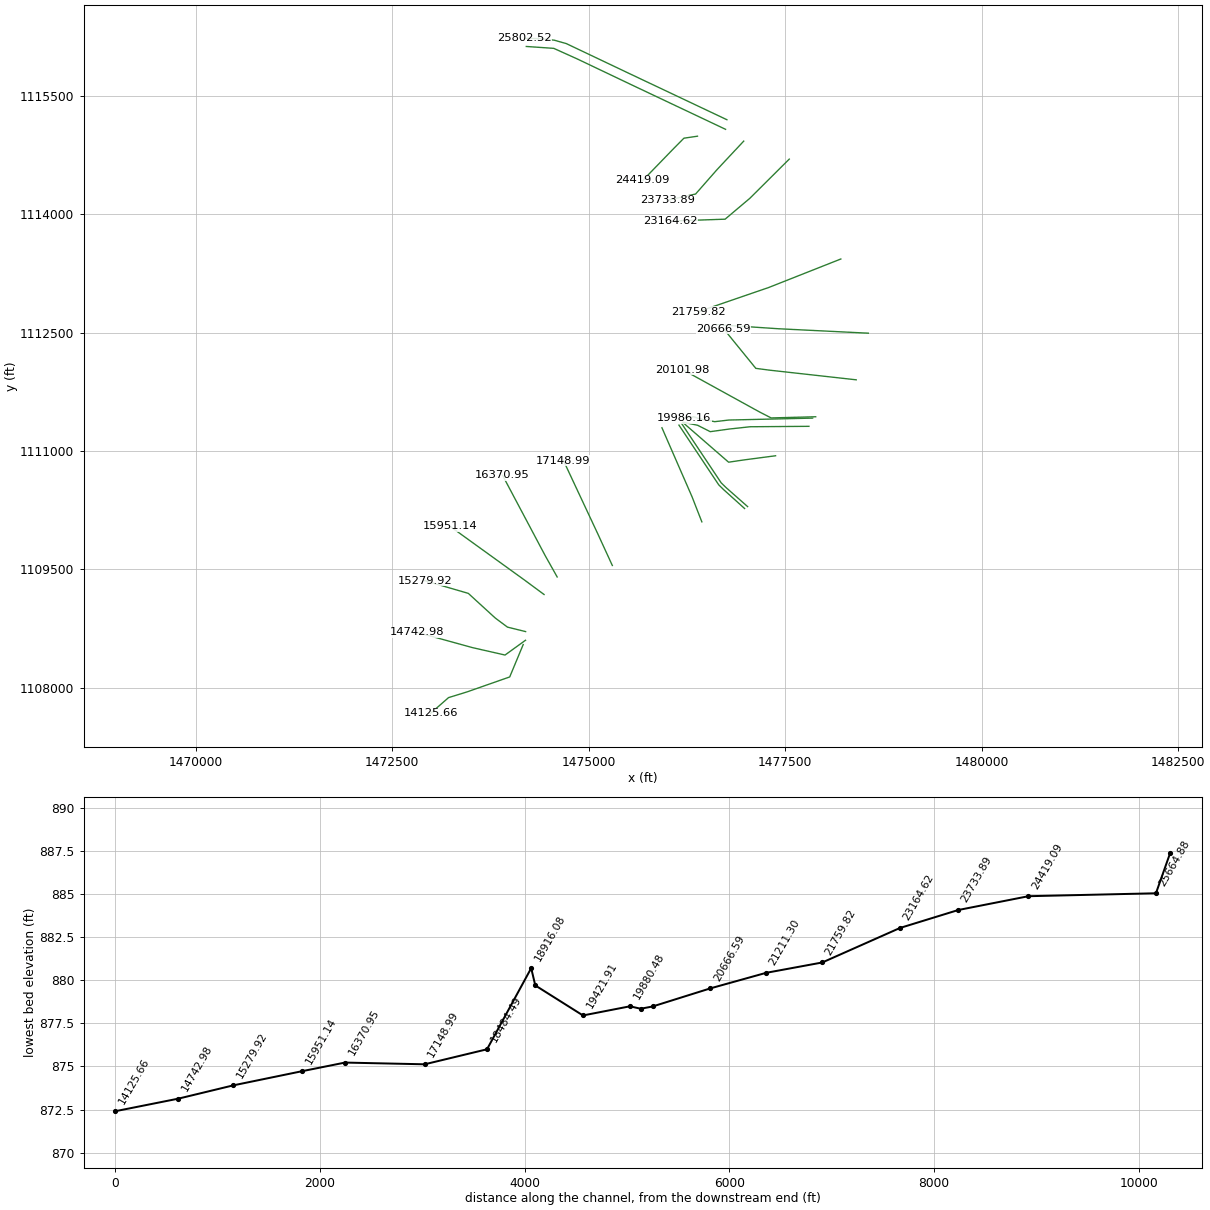
HEC-RAS study 12mile_Combined.prj: 12mile Creek Combined Model

--- 12mile_Combined.g01 (geometry) --- (continued)

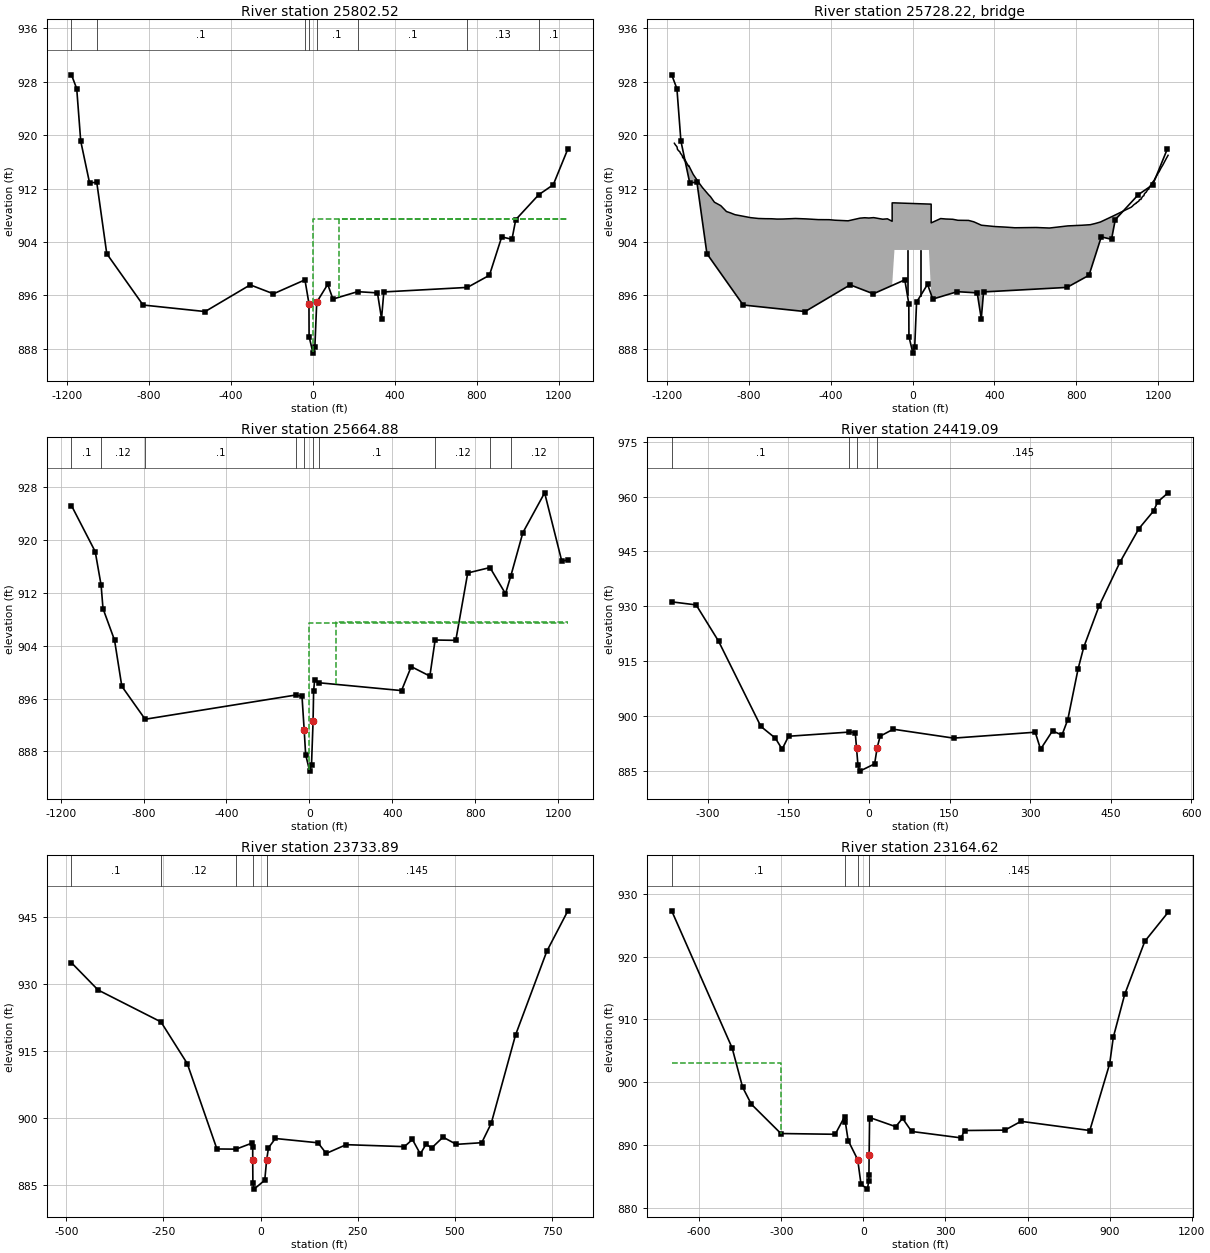
Type RM Length L Ch R = 1 ,25802.52,124.8866,137.6429,124.5588
BEGIN DESCRIPTION:
Shady Grove RD (TWE_14) - US
END DESCRIPTION:
XS GIS Cut Line= 6
   1476759.38911   1115198.56726   1475535.42848   1115775.82579
    1474715.1145   1116164.28117   1474564.28937   1116206.59875
   1474397.18832   1116226.13058   1474184.51444    1116230.4708
#Sta/Elev= 30
-1178.08  929.05-1152.49  926.97-1133.01  919.13-1089.97  912.87-1054.58  912.93
-1005.82  902.24-828.613  894.55-525.582  893.57 -305.43  897.57-192.206  896.23
 -38.209  898.32 -18.628  894.76 -18.022  889.83    1.29  887.34  10.262  888.32
  19.347  894.98  73.058  897.65  98.406  895.44 218.723  896.55 315.788  896.37
 335.697   892.5 346.956  896.51 755.001  897.19 862.535  899.01 922.508  904.76
  972.59   904.4 990.889  907.341103.585  911.091174.097  912.571245.483  917.94
#Mann= 8 ,-1,0
-1178.08     .12       0-1054.58      .1       0 -38.209     .12       0
 -18.628    .045       0  19.347      .1       0 218.723      .1       0
 755.001     .13       01103.585      .1       0
#XS Ineff= 2 , 0
       0    -140   907.4     130       0   907.5
Permanent Ineff=
       F       F
Bank Sta=-18.628,19.347
XS Rating Curve= 0 ,0
Skew Angle= 30
Exp/Cntr=0.5,0.3

Type RM Length L Ch R = 3 ,25728.22,,,
BEGIN DESCRIPTION:
Shady Grove RD (TWE_14) - TOR
Skew = 30 Degrees
END DESCRIPTION:
Bridge Culvert--1,0,-1,-1, 0
Deck Dist Width WeirC Skew NumUp NumDn MinLoCord MaxHiCord MaxSubmerge Is_Ogee
52.6,43.4,2.6,30, 166, 166, 905.93, , 0.95, 0, 0,0,,
-1164.89-1164.77-1160.34 -1154.4-1152.03 -1151.8-1149.83-1143.38-1138.84 -1135.7
-1127.87-1125.65-1124.21-1122.77-1121.62-1117.94 -1116.7-1115.34 -1115.2-1112.69
-1112.22 -1110.6-1099.83-1096.92-1094.73 -1072.7-1045.73-1027.84-997.427-988.715
-969.212-938.018-910.149-892.656-868.537-818.281-793.097 -753.91-721.174-689.815
-662.319-633.628-572.183-522.326-461.107-408.054-379.397-315.536-257.556-236.105
-234.199-213.882-190.465-167.896-146.176-123.435 -100.13 -100.13 -88.872 -88.872
  79.804  79.804   90.63   90.63 137.213 163.202 196.484 221.625 273.525 299.333
 336.477  402.52  452.49 500.277 603.992 668.857 717.433 759.063 829.834  869.03
 894.292 918.091 976.894 1068.711074.7121080.8171087.9361089.5291093.6081094.985
1097.3581100.8831106.0881109.4221112.7731116.2811117.398 1118.81 1120.811122.689
 1125.591130.0071130.9861132.3631132.6661135.922    11361139.1261141.7161143.309
1144.8331146.8951148.1851150.8441154.3251157.556 1159.141160.2921161.6431163.522
1165.6441167.2121168.5971170.2171171.1951172.7111175.1961175.2831177.6391179.327
1181.3021183.2941185.0081187.1561187.9271191.6081192.9071194.8471195.9121197.072
1199.2721201.2981202.4761203.4381205.3081207.6381208.8331211.8641215.3021215.423
1218.6541220.5851222.646 1225.01  1227.61229.2621231.3491234.225  1234.91237.611
1239.2481240.5211243.6211245.743 1248.151249.068
  918.79  918.78  918.57  918.35  918.25  918.21  917.88  917.64  917.55  917.32
     917  916.85  916.62  916.73  916.73  916.46  916.38  916.18  916.17  916.31
  916.29  916.17  915.58  915.39  915.46  914.12  912.91  912.16  911.07   910.8
  909.96  909.44  908.56  908.38  908.09   907.8  907.65  907.52  907.49  907.48
  907.43  907.44  907.52  907.46  907.35  907.34  907.26  907.17  907.57  907.63
  907.63  907.59  907.65  907.53  907.41  907.47   907.1  909.86  909.86  909.86
  909.67  909.67  909.67  906.86  907.51  907.44   907.4  907.25  907.23  907.02
  906.51  906.31  906.23  906.13  906.17  906.09  906.27  906.41  906.51  906.59
  906.78  906.99  907.84  909.21  909.36  909.56  909.71  909.77   909.8  909.92
  909.94  910.02  910.13  910.35  910.36  910.37  910.47  910.52  910.63  910.74
  910.85  910.91  910.98  911.09  911.18   911.3   911.3  911.41  911.45  911.53
  911.63  911.74  911.79  911.87   911.9  912.19  912.25  912.32  912.38   912.5
  912.54  912.59   912.7  912.83  912.87  912.93  913.04  913.04  913.13  913.19
  913.25  913.35  913.54  913.58  913.62  913.86  913.89  914.02  914.05  914.14
  914.27  914.35  914.38  914.43  914.53  914.66  914.72  914.92  915.13  915.13
  915.28  915.39  915.49  915.63  915.78  915.89  916.04  916.15  916.19   916.4
  916.46  916.52  916.68  916.82  916.93  916.99
                                                                                
                                                                                
                                                                                
                                                                                
                                                                                
                                                             890           902.8
   902.8             890
                                                                                
                                                                                
                                                                                
                                                                                
                                                                                
                                                                                
                                                                                
                                                                                
                                                                                
                                                
-1164.89-1164.77-1160.34 -1154.4-1152.03 -1151.8-1149.83-1143.38-1138.84 -1135.7
-1127.87-1125.65-1124.21-1122.77-1121.62-1117.94 -1116.7-1115.34 -1115.2-1112.69
-1112.22 -1110.6-1099.83-1096.92-1094.73 -1072.7-1045.73-1027.84-997.427-988.715
-969.212-938.018-910.149-892.656-868.537-818.281-793.097 -753.91-721.174-689.815
-662.319-633.628-572.183-522.326-461.107-408.054-379.397-315.536-257.556-236.105
-234.199-213.882-190.465-167.896-146.176-123.435 -100.13 -100.13 -88.872 -88.872
  79.804  79.804   90.63   90.63 137.213 163.202 196.484 221.625 273.525 299.333
 336.477  402.52  452.49 500.277 603.992 668.857 717.433 759.063 829.834  869.03
 894.292 918.091 976.894 1068.711074.7121080.8171087.9361089.5291093.6081094.985
1097.3581100.8831106.0881109.4221112.7731116.2811117.398 1118.81 1120.811122.689
 1125.591130.0071130.9861132.3631132.6661135.922    11361139.1261141.7161143.309
1144.8331146.8951148.1851150.8441154.3251157.556 1159.141160.2921161.6431163.522
1165.6441167.2121168.5971170.2171171.1951172.7111175.1961175.2831177.6391179.327
1181.3021183.2941185.0081187.1561187.9271191.6081192.9071194.8471195.9121197.072
1199.2721201.2981202.4761203.4381205.3081207.6381208.8331211.8641215.3021215.423
1218.6541220.5851222.646 1225.01  1227.61229.2621231.3491234.225  1234.91237.611
1239.2481240.5211243.6211245.743 1248.151249.068
  918.79  918.78  918.57  918.35  918.25  918.21  917.88  917.64  917.55  917.32
     917  916.85  916.62  916.73  916.73  916.46  916.38  916.18  916.17  916.31
  916.29  916.17  915.58  915.39  915.46  914.12  912.91  912.16  911.07   910.8
  909.96  909.44  908.56  908.38  908.09   907.8  907.65  907.52  907.49  907.48
  907.43  907.44  907.52  907.46  907.35  907.34  907.26  907.17  907.57  907.63
  907.63  907.59  907.65  907.53  907.41  907.47   907.1  909.86  909.86  909.86
  909.67  909.67  909.67  906.86  907.51  907.44   907.4  907.25  907.23  907.02
  906.51  906.31  906.23  906.13  906.17  906.09  906.27  906.41  906.51  906.59
  906.78  906.99  907.84  909.21  909.36  909.56  909.71  909.77   909.8  909.92
  909.94  910.02  910.13  910.35  910.36  910.37  910.47  910.52  910.63  910.74
  910.85  910.91  910.98  911.09  911.18   911.3   911.3  911.41  911.45  911.53
  911.63  911.74  911.79  911.87   911.9  912.19  912.25  912.32  912.38   912.5
  912.54  912.59   912.7  912.83  912.87  912.93  913.04  913.04  913.13  913.19
  913.25  913.35  913.54  913.58  913.62  913.86  913.89  914.02  914.05  914.14
  914.27  914.35  914.38  914.43  914.53  914.66  914.72  914.92  915.13  915.13
  915.28  915.39  915.49  915.63  915.78  915.89  916.04  916.15  916.19   916.4
  916.46  916.52  916.68  916.82  916.93  916.99
                                                                                
                                                                                
                                                                                
                                                                                
                                                                                
                                                             890           902.7
  902.62             890
                                                                                
                                                                                
                                                                                
                                                                                
                                                                                
                                                                                
                                                                                
                                                                                
                                                                                
                                                
Pier Skew, UpSta & Num, DnSta & Num=  ,-25.981, 4 ,-25.981, 4 , 3 , 3 , 0 ,,
     4.5     4.5     6.5     6.5
     890   900.8   900.8   902.9
     4.5     4.5     6.5     6.5
     890   900.8   900.8   902.9
Pier Skew, UpSta & Num, DnSta & Num=  ,38.971, 4 ,38.971, 4 , 3 , 3 , 0 ,,
     4.5     4.5     6.5     6.5
     890   900.8   900.8   902.9
     4.5     4.5     6.5     6.5
     890   900.8   900.8   902.9
Abutment Skew #Up #Dn= , 2 , 2
  -88.87  -26.04
   902.8  897.58
  -88.87  -26.04
  902.62     892
Abutment Skew #Up #Dn= , 2 , 2
   40.47    79.8
  897.05   902.8
   40.47    79.8
  897.05   902.8
BR Coef=-1 , 1 , 0 ,, 0 ,,,0.8,-1,1.2,0,
WSPro=,,,, 1 ,,,, 0 ,,,, 0 ,,,,-1 ,-1 ,-1 , 0 , 0 , 0 , 0 , 0
BC Design=,, 0 ,, 0 ,,,,,,
BC Use User HTab Curves=0
BC User HTab FreeFlow(D)= 0

Type RM Length L Ch R = 1 ,25664.88,778.3932,1245.781,1447.994
BEGIN DESCRIPTION:
Shady Grove RD (TWE_14) - DS
END DESCRIPTION:
XS GIS Cut Line= 5
   1476742.02822    1115077.0397    1475546.2792   1115641.27657
   1474856.17388    1115968.9685    1474556.6939   1116103.51739
   1474207.30085   1116127.38878
#Sta/Elev= 30
-1147.51  925.15-1033.05   918.2 -1004.6  913.12-995.505  909.59-939.854  904.82
-904.702  897.85-792.197  892.87 -63.532  896.54 -35.568  896.31 -25.141  891.26
 -18.022  887.52    1.29  885.03  10.262  886.01   17.71  892.54   20.43  897.14
  25.279  898.78  46.627  898.38  444.41   897.2 491.288  900.82 581.042  899.39
 606.495  904.84 706.174  904.79 763.713  914.97 870.996  915.79  945.83  911.84
 971.663  914.531029.635  921.061134.658  927.081217.554  916.741246.747  916.95
#Mann= 10 ,-1,0
-1147.51      .1       0 -1004.6     .12       0-792.197      .1       0
 -63.532     .14       0 -25.141    .045       0   17.71     .14       0
  46.627      .1       0 606.495     .12       0 870.996     .06       0
 971.663     .12       0
#XS Ineff= 2 , 0
       0    -140   907.4     130       0   907.5
Permanent Ineff=
       F       F
Bank Sta=-25.141,17.71
XS Rating Curve= 0 ,0
Skew Angle= 30
Exp/Cntr=0.5,0.3

Type RM Length L Ch R = 1 ,24419.09,602.4268,685.2051,612.0017
BEGIN DESCRIPTION:
TWE_13X
END DESCRIPTION:
XS GIS Cut Line= 4
   1476384.83694   1114989.85171   1476212.22671   1114964.61581
   1476078.12369   1114829.47835   1475688.55643   1114428.74672
#Sta/Elev= 30
 -366.99  931.18 -321.47  930.34 -279.78  920.42 -201.03  897.09  -174.2   893.9
 -161.46  890.87 -149.51   894.4  -36.12  895.55  -25.42  895.38  -23.07  891.29
  -20.44  886.56  -16.86  884.86   10.66  886.85    15.4  891.29    20.9  894.42
   45.29  896.33  157.65  893.89  309.52  895.51  319.43  890.85  341.68  895.88
  359.27  894.71   370.1  898.96  389.34  912.86  399.79  918.77  428.31  930.04
  467.13  942.01   502.4   951.2  529.76  956.05  537.46  958.55  556.72  961.01
#Mann= 4 ,-1,0
 -366.99      .1       0  -36.12     .14       0  -23.07    .045       0
    15.4    .145       0
Bank Sta=-23.07,15.4
XS Rating Curve= 0 ,0
Exp/Cntr=0.3,0.1

Type RM Length L Ch R = 1 ,23733.89,579.1484,569.2657,513.473
XS GIS Cut Line= 4
   1476972.87861   1114927.45079   1476636.50656   1114569.37697
   1476361.01772   1114257.02723   1476000.65453   1114176.58104
#Sta/Elev= 30
 -486.55  934.67 -418.13  928.58 -256.43  921.45 -188.77  912.14 -112.45  893.04
  -63.14     893   -21.9  894.36  -20.32  893.43   -20.3  890.49  -19.87  885.49
  -16.86  884.06   10.66  886.05    15.4  890.49   20.25   893.3   37.96  895.38
  147.63  894.42  168.79  892.04  220.13     894  369.97  893.56  390.57  895.16
  410.77  891.93  425.79  894.12  439.83  893.24  469.31  895.68  503.53  894.07
  568.88  894.44  593.26  898.76  655.78  918.51  736.26  937.24  790.45  946.28
#Mann= 5 ,-1,0
 -486.55      .1       0 -256.43     .12       0  -63.14     .14       0
   -20.3    .045       0    15.4    .145       0
Bank Sta=-20.3,15.4
XS Rating Curve= 0 ,0
Exp/Cntr=0.3,0.1

Type RM Length L Ch R = 1 ,23164.62,718.7921,759.3404,449.3556
XS GIS Cut Line= 4
   1477552.30676   1114699.58563   1477051.00361    1114202.6227
   1476736.33301   1113937.86549   1476039.71686   1113913.99377
#Sta/Elev= 30
  -700.6  927.27 -479.65  905.46 -441.53  899.24 -409.61  896.53 -301.46  891.86
 -102.98  891.74  -68.39  894.55  -65.84  893.66  -55.67  890.75  -20.73   887.7
   -8.79  883.82    14.5  883.02   19.54  884.25   20.29   885.2   20.95  888.41
   22.67  894.19   24.63  894.38  118.11  892.95  143.03  894.28  176.29  892.19
  356.84  891.17  370.04  892.34  517.34   892.4  576.03   893.8  827.48  892.34
  900.23  902.98  913.33  907.16  955.07  913.99 1028.51  922.42 1113.54  927.03
#Mann= 4 ,-1,0
  -700.6      .1       0  -65.84     .14       0  -20.73    .045       0
   20.95    .145       0
#XS Ineff= 2 , 0
         -300.44  903.05
Permanent Ineff=
       F       F
Bank Sta=-20.73,20.95
XS Rating Curve= 0 ,0
Exp/Cntr=0.3,0.1

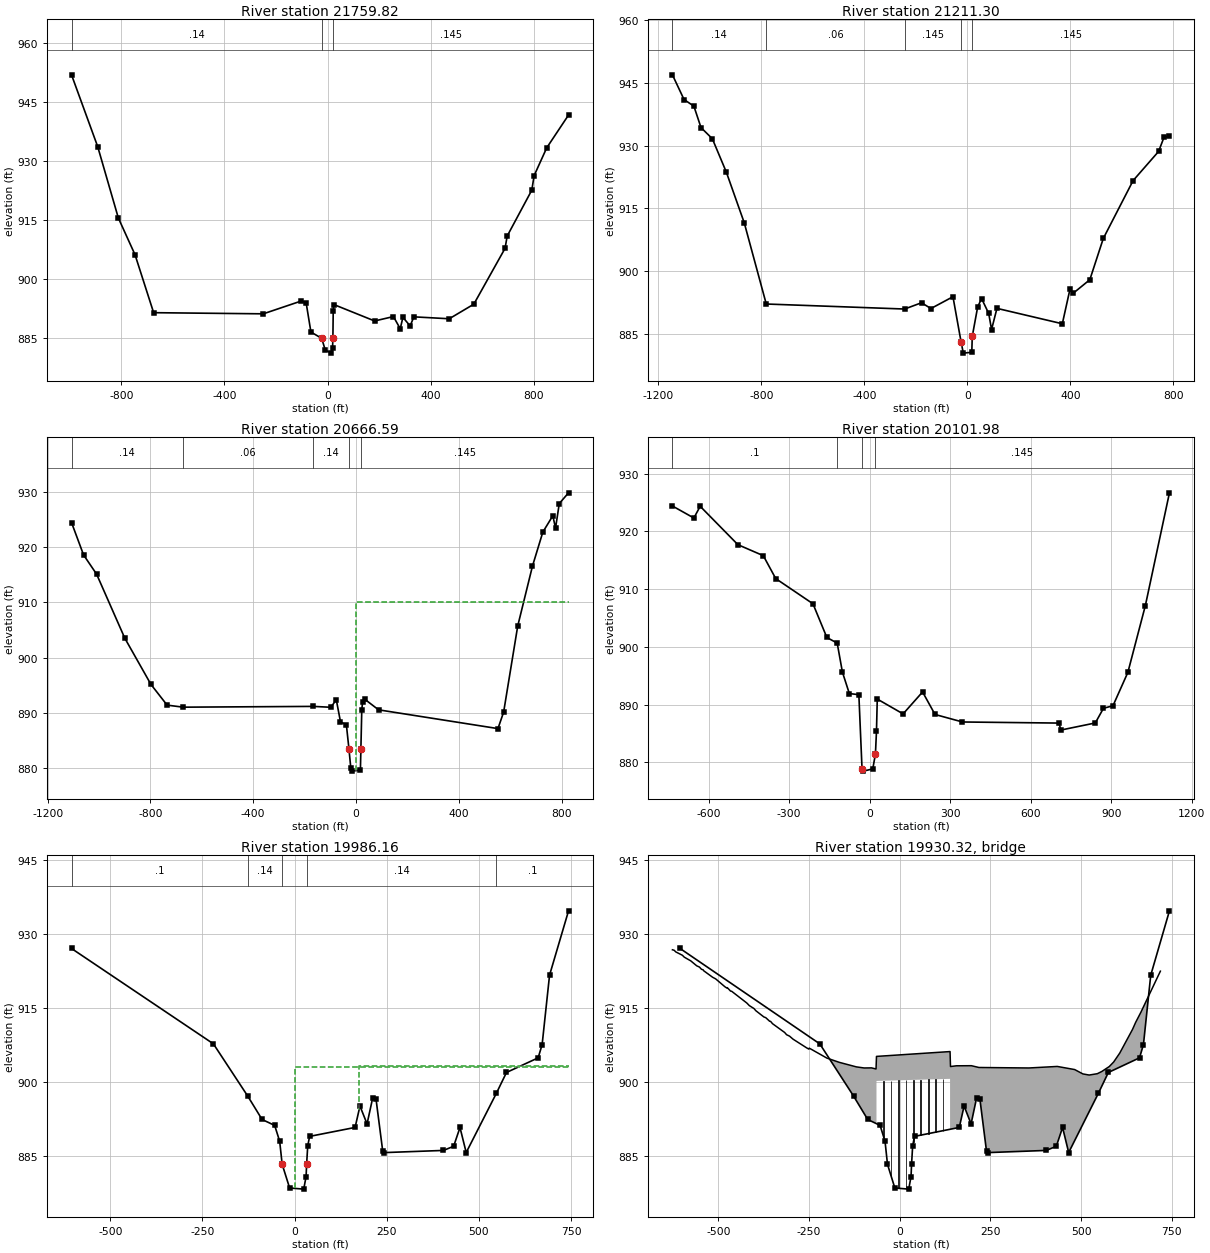
Type RM Length L Ch R = 1 ,21759.82,703.4542,548.5153,484.4774
XS GIS Cut Line= 3
   1478208.34121    1113433.0899    1477291.6729   1113071.97802
   1476399.30971   1112766.42192
#Sta/Elev= 30
 -993.24  951.97 -891.53  933.64 -811.65  915.49 -746.84  906.11 -674.63  891.33
 -249.12  891.04 -102.69  894.29  -83.06  893.91  -64.33   886.4  -22.55  884.79
   -8.79  881.82    14.5  881.02   19.54  882.25   20.89   884.8   22.18  891.73
   24.83   893.4  182.81  889.22  255.79  890.34  282.19  887.24   292.6  890.14
  320.56  887.96  335.19  890.27  472.34  889.78  567.74   893.5  688.86  907.73
  697.18  910.87  792.75  922.58  801.71  926.27  850.47  933.35  935.22  941.72
#Mann= 3 ,-1,0
 -993.24     .14       0  -22.55    .045       0   20.89    .145       0
Bank Sta=-22.55,20.89
XS Rating Curve= 0 ,0
Exp/Cntr=0.3,0.1

Type RM Length L Ch R = 1 ,21211.30,610.2067,544.715,527.129
XS GIS Cut Line= 3
   1478558.16798    1112492.5502   1477412.33235   1112548.97375
   1476631.08104   1112601.05709
#Sta/Elev= 30
-1145.45  946.94 -1100.3  941.03-1062.11  939.45-1034.46  934.33 -990.51  931.67
 -935.89  923.65  -866.5  911.57 -781.05  892.16 -243.82  890.96 -178.07  892.46
 -141.47  891.08  -55.95   893.9  -24.62  883.16  -15.79  880.42   17.15  880.62
   19.01  884.43   40.01  891.47   55.16  893.46   82.89   889.9   93.94  886.06
  114.88  891.12  368.76  887.44  398.25  895.64  410.35   894.7  475.57  897.97
  527.82  907.82  643.61  921.66  742.51  928.62  763.33  931.96  784.76  932.28
#Mann= 5 ,-1,0
-1145.45     .14       0 -781.05     .06       0 -243.82    .145       0
  -24.62     .04       0   19.01    .145       0
Bank Sta=-24.62,19.01
XS Rating Curve= 0 ,0
Exp/Cntr=0.3,0.1

Type RM Length L Ch R = 1 ,20666.59,645.7516,564.6043,507.8956
BEGIN DESCRIPTION:
TWE_11X
END DESCRIPTION:
XS GIS Cut Line= 4
   1478404.08793   1111901.40289   1477303.00787   1112023.66371
   1477126.72736   1112046.60039    1476716.8107   1112548.89272
#Sta/Elev= 30
-1106.95  924.42-1060.11  918.57 -1009.3  915.09 -899.76  903.54 -797.76  895.17
 -734.98  891.44 -672.61  891.07 -165.55  891.21  -98.11  891.05  -76.64   892.4
  -60.35  888.42  -37.45  887.88  -27.42  883.53  -20.31  880.12  -15.79  879.52
   17.15  879.72   19.01  883.53   22.48   890.6    25.8  892.04   34.19   892.5
   87.83  890.59  552.34   887.2  574.44  890.18  629.27  905.73   686.7  916.56
  726.99  922.69  765.82  925.64  776.37   923.4  790.98  927.85  826.99  929.78
#Mann= 5 ,-1,0
-1106.95     .14       0 -672.61     .06       0 -165.55     .14       0
  -27.42     .04       0   19.01    .145       0
#XS Ineff= 2 , 0
       0    -500     910               0
Permanent Ineff=
       F       F
Bank Sta=-27.42,19.01
XS Rating Curve= 0 ,0
Exp/Cntr=0.3,0.1

Type RM Length L Ch R = 1 ,20101.98,105.6221,115.8291,169.4414
BEGIN DESCRIPTION:
TWE_10USX
END DESCRIPTION:
XS GIS Cut Line= 4
   1477888.46194   1111433.08596    1477321.6998   1111418.33793
   1477172.48917   1111494.65551     1476193.146    1112032.0456
#Sta/Elev= 30
 -734.65  924.38 -654.74   922.3 -631.26  924.33 -490.66  917.68 -396.14  915.78
 -349.76  911.81 -211.11  907.45 -159.31  901.61 -120.81  900.64 -101.37  895.62
  -75.56   891.9  -40.11  891.71  -28.18  878.78  -22.95  878.47   11.79  878.86
   21.66  881.43   25.56  885.37   28.49  890.95  124.74  888.38  197.31  892.18
   243.6  888.28  345.96  886.98  705.74  886.79  712.18  885.58   840.8  886.81
  871.15  889.35  906.62  889.79   962.1  895.57 1027.27  907.14 1116.99  926.66
#Mann= 4 ,-1,0
 -734.65      .1       0 -120.81     .14       0  -28.18    .035       0
   21.66    .145       0
Bank Sta=-28.18,21.66
XS Rating Curve= 0 ,0
Exp/Cntr=0.5,0.3

Type RM Length L Ch R = 1 ,19986.16,93.96153,105.6731,113.0735
BEGIN DESCRIPTION:
Walhalla Hwy (TWE_10) - US
END DESCRIPTION:
XS GIS Cut Line= 6
   1477849.28182   1111415.87172   1476783.30709   1111391.56594
   1476604.48753   1111370.73261   1476408.30643   1111407.19094
    1476338.8622   1111433.23261   1476213.86188   1111415.87172
#Sta/Elev= 30
-605.091  927.02-220.163  907.73-127.067  897.17 -88.092  892.43 -53.917  891.23
 -40.327  888.02 -33.577  883.36 -13.336  878.57  24.943  878.34  31.333  880.88
  32.766  883.36  35.781  887.08  40.892  889.01 164.273  890.82  177.51  895.15
 196.752  891.53 212.103  896.83 221.204  896.49 239.332  885.99 243.411  885.73
 404.096  886.17 431.652  887.01 448.904  890.81 465.721  885.74   547.8  897.76
 575.012  901.94 660.966   904.9 671.762  907.59 691.872  921.62 743.397  934.64
#Mann= 5 ,-1,0
-605.091      .1       0-127.067     .14       0 -33.577    .035       0
  32.766     .14       0   547.8      .1       0
#XS Ineff= 2 , 0
       0    -100     903     175       0  903.33
Permanent Ineff=
       F       F
Bank Sta=-33.577,32.766
XS Rating Curve= 0 ,0
Skew Angle= 35
Exp/Cntr=0.5,0.3

Type RM Length L Ch R = 3 ,19930.32,,,
BEGIN DESCRIPTION:
Walhalla Hwy (TWE_10) - TOR
Skew = 35 Degrees
END DESCRIPTION:
Bridge Culvert--1,0,-1,-1, 0
Deck Dist Width WeirC Skew NumUp NumDn MinLoCord MaxHiCord MaxSubmerge Is_Ogee
36,39.5,2.6,35, 60, 60, 901.51, , 0.95, 0, 0,0,,
-626.201-621.401-616.936-598.718 -593.59-575.544 -559.35-551.699 -546.08-541.623
-540.067-515.238 -507.17-481.432-476.468-475.108-465.925 -463.05  -421.2 -414.18
-401.442-396.396-374.393 -368.93-358.305-355.758-350.392 -316.93-311.646-303.512
-293.871-255.707-250.423-249.112 -200.61 -165.96-119.252 -97.823 -77.598 -65.155
 -63.894 138.846 140.067 156.229 197.579 218.411 356.061 434.249 482.202 504.802
 522.111 544.671 556.966 577.592 589.708  606.41 641.601 650.153 664.742 718.413
  926.76  926.66  926.33  925.65  925.27  924.51  923.52  923.26  922.81  922.71
  922.52  921.19  920.88  919.27  919.03   919.1   918.4  918.37  915.99  915.46
  914.87  914.44  913.18  913.02   912.3  912.28  911.81  910.03  909.58  909.29
  908.68  906.89  906.67  906.86  904.85  903.98  903.07  902.85  902.87  902.65
  905.19  906.17  903.14  903.29  903.31  902.95  902.85  903.16  902.53  901.65
  901.42  901.69  902.14  903.14  904.06  905.86  910.65  912.06  914.13  922.43
                                                                                
                                                                                
                                                                                
                                                                                
  900.23  900.65
                                                                                
-626.201-621.401-616.936-598.718 -593.59-575.544 -559.35-551.699 -546.08-541.623
-540.067-515.238 -507.17-481.432-476.468-475.108-465.925 -463.05  -421.2 -414.18
-401.442-396.396-374.393 -368.93-358.305-355.758-350.392 -316.93-311.646-303.512
-293.871-255.707-250.423-249.112 -200.61 -165.96-119.252 -97.823 -77.598 -65.155
 -63.894 138.846 140.067 156.229 197.579 218.411 356.061 434.249 482.202 504.802
 522.111 544.671 556.966 577.592 589.708  606.41 641.601 650.153 664.742 718.413
  926.76  926.66  926.33  925.65  925.27  924.51  923.52  923.26  922.81  922.71
  922.52  921.19  920.88  919.27  919.03   919.1   918.4  918.37  915.99  915.46
  914.87  914.44  913.18  913.02   912.3  912.28  911.81  910.03  909.58  909.29
  908.68  906.89  906.67  906.86  904.85  903.98  903.07  902.85  902.87  902.65
  905.19  906.17  903.14  903.29  903.31  902.95  902.85  903.16  902.53  901.65
  901.42  901.69  902.14  903.14  904.06  905.86  910.65  912.06  914.13  922.43
                                                                                
                                                                                
                                                                                
                                                                                
   900.2  900.61
                                                                                
Pier Skew, UpSta & Num, DnSta & Num=  ,-44.234, 4 ,-44.234, 4 , 3 , 3 , 0 ,,
       1       1       2       2
     880  898.65  898.65  900.65
       1       1       2       2
     880  898.65  898.65  900.65
Pier Skew, UpSta & Num, DnSta & Num=  ,-23.755, 4 ,-23.755, 4 , 3 , 3 , 0 ,,
       1       1       2       2
     880  898.65  898.65  900.65
       1       1       2       2
     880  898.65  898.65  900.65
Pier Skew, UpSta & Num, DnSta & Num=  ,-3.277, 4 ,-3.277, 4 , 3 , 3 , 0 ,,
       1       1       2       2
     880  898.65  898.65  900.65
       1       1       2       2
     880  898.65  898.65  900.65
Pier Skew, UpSta & Num, DnSta & Num=  ,17.202, 4 ,17.202, 4 , 3 , 3 , 0 ,,
       1       1       2       2
     880  898.65  898.65  900.65
       1       1       2       2
     880  898.65  898.65  900.65
Pier Skew, UpSta & Num, DnSta & Num=  ,37.681, 4 ,37.681, 4 , 3 , 3 , 0 ,,
       1       1       2       2
     880  898.65  898.65  900.65
       1       1       2       2
     880  898.65  898.65  900.65
Pier Skew, UpSta & Num, DnSta & Num=  ,58.16, 4 ,58.16, 4 , 3 , 3 , 0 ,,
       1       1       2       2
     880  898.65  898.65  900.65
       1       1       2       2
     880  898.65  898.65  900.65
Pier Skew, UpSta & Num, DnSta & Num=  ,78.639, 4 ,78.639, 4 , 3 , 3 , 0 ,,
       1       1       2       2
     880  898.65  898.65  900.65
       1       1       2       2
     880  898.65  898.65  900.65
Pier Skew, UpSta & Num, DnSta & Num=  ,99.117, 4 ,99.117, 4 , 3 , 3 , 0 ,,
       1       1       2       2
     880  898.65  898.65  900.65
       1       1       2       2
     880  898.65  898.65  900.65
Pier Skew, UpSta & Num, DnSta & Num=  ,119.596, 4 ,119.596, 4 , 3 , 3 , 0 ,,
       1       1       2       2
     880  898.65  898.65  900.65
       1       1       2       2
     880  898.65  898.65  900.65
BR Coef=-1 , 1 , 0 ,, 0 ,,,0.8,0,1.2,0,
WSPro=,,,, 1 ,,,, 0 ,,,, 0 ,,,,-1 ,-1 ,-1 , 0 , 0 , 0 , 0 , 0
BC Design=,, 0 ,, 0 ,,,,,,
BC Use User HTab Curves=0
BC User HTab FreeFlow(D)= 0

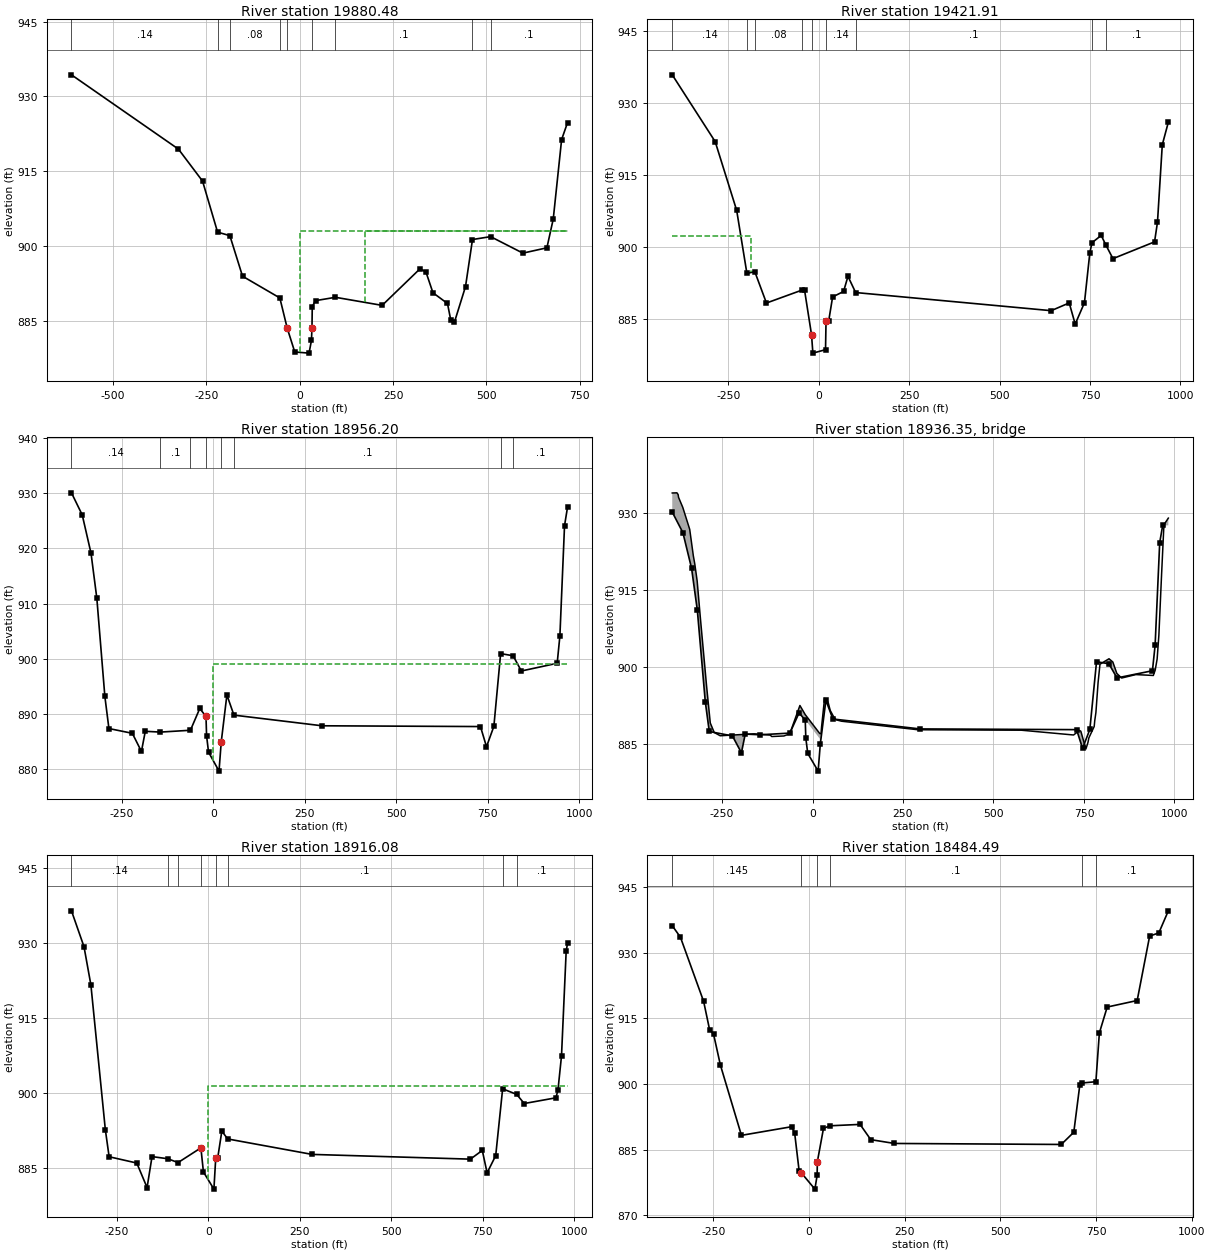
Type RM Length L Ch R = 1 ,19880.48,416.2491,458.5743,451.101
BEGIN DESCRIPTION:
Walhalla Hwy (TWE_10) - DS
END DESCRIPTION:
XS GIS Cut Line= 6
   1477802.40682   1111311.70505    1477055.8773   1111306.49672
   1476785.04331   1111276.98228   1476547.19587   1111243.99639
   1476386.37861   1111325.33005   1476208.03707   1111361.97966
#Sta/Elev= 30
-611.178  934.31-324.712   919.4-260.212  912.99-219.959  902.75-187.111  902.05
-153.173  893.91 -53.286  889.55 -33.577   883.5 -13.336  878.71  24.943  878.48
  31.333  881.02  32.766   883.5  33.544  887.83  42.383  889.01  95.603  889.68
 220.639  888.06  322.32  895.42 338.105  894.72 356.675  890.59 395.536  888.44
 404.448  885.08 414.098  884.67 443.874  891.84 462.551  901.27 510.995  901.85
 597.522  898.54 661.752  899.61 678.758  905.38 701.161  921.32 717.037  924.73
#Mann= 9 ,-1,0
-611.178     .14       0-219.959     .06       0-187.111     .08       0
 -53.286     .14       0 -33.577    .035       0  32.766     .14       0
  95.603      .1       0 462.551     .06       0 510.995      .1       0
#XS Ineff= 2 , 0
       0    -100     903     175       0     903
Permanent Ineff=
       F       F
Bank Sta=-33.577,32.766
XS Rating Curve= 0 ,0
Skew Angle= 35
Exp/Cntr=0.5,0.3

Type RM Length L Ch R = 1 ,19421.91,522.9336,465.7054,185.1479
XS GIS Cut Line= 4
   1477377.90814   1110938.60761   1476974.30643   1110885.60925
   1476780.65879   1110857.07185   1476199.35663   1111360.24377
#Sta/Elev= 30
 -405.13  935.83 -286.45  921.94 -227.02  907.64  -198.7  894.53  -176.9  894.89
  -144.7  888.37  -46.05  891.07  -39.23     891  -20.09   881.8  -16.28  877.95
   18.67  878.67   20.09  884.68   27.45  884.66   38.27  889.64   68.52  890.77
   80.71  893.92   101.9  890.55  642.55  886.78  692.47  888.39     709  883.98
  734.59  888.44  749.49  898.84  755.51  900.92  780.92  902.43  793.68  900.45
  813.44   897.6  928.38  901.09   936.5  905.17  949.79  921.28   966.5  925.97
#Mann= 9 ,-1,0
 -405.13     .14       0  -198.7     .06       0  -176.9     .08       0
  -46.05     .14       0  -20.09    .045       0   20.09     .14       0
   101.9      .1       0  755.51     .06       0  793.68      .1       0
#XS Ineff= 2 , 0
          -186.7  902.26
Permanent Ineff=
       F       F
Bank Sta=-20.09,20.09
XS Rating Curve= 0 ,0
Exp/Cntr=0.5,0.3

Type RM Length L Ch R = 1 ,18956.20,41.10629,40.11645,40.70418
BEGIN DESCRIPTION:
Unnamed Foot Bridge - US
END DESCRIPTION:
XS GIS Cut Line= 4
   1477022.27493   1110294.26903    1476747.2523   1110536.14403
   1476686.03609   1110595.77953   1476183.73163   1111346.35466
#Sta/Elev= 30
 -387.46  930.08 -358.06  926.08 -334.06  919.14 -318.16  910.97 -296.26  893.21
 -285.19   887.4 -221.27  886.54  -196.4  883.25 -185.84   886.9  -144.5  886.76
  -62.55  887.09  -37.06  891.03  -20.04  889.59  -18.48   886.1  -13.12  883.14
   15.54  879.69   21.53  884.95   37.02  893.48   56.28  889.83  296.97   887.9
  729.58  887.76  746.05  884.11  766.15  887.79  784.65  900.97  818.74  900.58
  841.17  897.82  939.09  899.22   946.5  904.18  959.18  924.14   967.4   927.5
#Mann= 8 ,-1,0
 -387.46     .14       0  -144.5      .1       0  -62.55     .14       0
  -20.04    .045       0   21.53     .14       0   56.28      .1       0
  784.65     .06       0  818.74      .1       0
#XS Ineff= 2 , 0
       0    -140  899.01      40       0     890
Permanent Ineff=
       F       F
Bank Sta=-20.04,21.53
XS Rating Curve= 0 ,0
Exp/Cntr=0.5,0.3

Type RM Length L Ch R = 3 ,18936.35,,,
BEGIN DESCRIPTION:
Unnamed Foot Bridge - TOR
END DESCRIPTION:
Bridge Culvert--1,0,-1,-1, 0
Deck Dist Width WeirC Skew NumUp NumDn MinLoCord MaxHiCord MaxSubmerge Is_Ogee
17.85,4,2.6,0, 60, 60, 886.97, , 0.95, 0, 0,0,,
 -387.46 -374.44 -371.21 -370.04 -358.38 -339.25 -329.24 -325.18 -318.64  -309.7
 -292.62 -282.38 -271.52 -255.01  -161.5 -116.79 -112.54  -78.93  -66.17  -59.09
  -34.81     -20     -20      20      20   23.52   25.06   33.31   39.03    43.8
   48.94   58.89    64.9   80.15  291.35  576.96  721.22  737.37  741.25  755.29
  760.92  763.58  778.18  779.77  782.94  788.96  794.19   819.1  829.67  840.69
  853.93  893.13  941.58  946.81  952.08  956.88  964.09  970.28  972.44     983
   933.8  933.83  933.48  932.95     931  926.73  921.59  919.98  916.68  909.44
  896.26  889.05  887.21  886.57  886.95   886.7  886.42  886.53  886.86  887.69
  892.46  890.67  890.67  887.01  887.01  886.97   888.3  893.84  893.64   892.9
   891.5   890.2  889.68   889.4  887.74  887.65  886.72   887.6  887.46     884
  885.25  886.17  888.37  889.52  891.09  896.94  900.49  901.55  900.92   898.7
   897.8  898.47   898.3  899.36   901.5  906.14  917.52   926.8  927.79  928.91
                                                                                
                                                                                
                  889.67  886.01
                                                                                
                                                                                
                                                                                
 -387.46 -374.44 -371.21 -370.04 -358.38 -339.25 -329.24 -325.18 -318.64  -309.7
 -292.62 -282.38 -271.52 -255.01  -161.5 -116.79 -112.54  -78.93  -66.17  -59.09
  -34.81     -20     -20      20      20   23.52   25.06   33.31   39.03    43.8
   48.94   58.89    64.9   80.15  291.35  576.96  721.22  737.37  741.25  755.29
  760.92  763.58  778.18  779.77  782.94  788.96  794.19   819.1  829.67  840.69
  853.93  893.13  941.58  946.81  952.08  956.88  964.09  970.28  972.44     983
   933.8  933.83  933.48  932.95     931  926.73  921.59  919.98  916.68  909.44
  896.26  889.05  887.21  886.57  886.95   886.7  886.42  886.53  886.86  887.69
  892.46  890.67  890.67  887.01  887.01  886.97   888.3  893.84  893.64   892.9
   891.5   890.2  889.68   889.4  887.74  887.65  886.72   887.6  887.46     884
  885.25  886.17  888.37  889.52  891.09  896.94  900.49  901.55  900.92   898.7
   897.8  898.47   898.3  899.36   901.5  906.14  917.52   926.8  927.79  928.91
                                                                                
                                                                                
                  889.67  886.01
                                                                                
                                                                                
                                                                                
BR Coef=-1 , 1 , 0 ,, 0 ,,,0.8,0,1.2,0,
WSPro=,,,, 1 ,,,, 0 ,,,, 0 ,,,,-1 ,-1 ,-1 , 0 , 0 , 0 , 0 , 0
BC Design=,, 0 ,, 0 ,,,,,,
BC Use User HTab Curves=0
BC User HTab FreeFlow(D)= 0

Type RM Length L Ch R = 1 ,18916.08,435.3299,431.5941,310.5046
BEGIN DESCRIPTION:
Unnamed Foot Bridge - DS
END DESCRIPTION:
XS GIS Cut Line= 4
   1476984.08038   1110269.96358   1476720.07054   1110506.78117
   1476655.09383    1110570.0794   1476149.00951   1111327.25755
#Sta/Elev= 30
 -373.84  936.48 -339.56  929.28 -320.74  921.63 -281.28  892.62  -270.9  887.18
 -195.29  885.92 -167.17     881 -153.62  887.21 -110.45  886.78  -82.54  886.01
  -20.05  888.96  -13.12  884.14   15.54  880.69   20.54  886.92   25.82   886.9
   37.25  892.33    53.1  890.75  283.96  887.65  716.64   886.7  749.21  888.45
  762.39  883.96  785.88   887.4  804.84   900.8   843.3  899.68  863.88  897.85
   950.6     899  956.17  900.62  965.77  907.41  978.51  928.36  982.27  930.01
#Mann= 8 ,-1,0
 -373.84     .14       0 -110.45      .1       0  -82.54     .14       0
  -20.05    .035       0   20.54     .14       0    53.1      .1       0
  804.84     .06       0   843.3      .1       0
#XS Ineff= 2 , 0
       0    -140  901.41      40       0     889
Permanent Ineff=
       F       F
Bank Sta=-20.05,20.54
XS Rating Curve= 0 ,0
Exp/Cntr=0.5,0.3

Type RM Length L Ch R = 1 ,18484.49,607.0316,609.0988,541.4633
XS GIS Cut Line= 3
   1476440.24705   1110100.82776    1476313.8668   1110422.89403
   1475932.68701   1111293.28806
#Sta/Elev= 30
 -357.15  936.14  -335.8  933.52 -275.14  918.85 -259.55  912.38 -249.22  911.39
 -231.42  904.34 -176.39  888.27  -45.39  890.24  -37.49  888.91  -25.71  880.21
  -20.04  879.72   15.54  875.99   21.43  879.16    21.9   882.2   37.94  889.84
   54.24  890.45  133.56  890.77  161.54  887.29  223.28  886.42  659.28  886.19
  692.01  888.98  707.79  899.81  713.05  900.22  749.75  900.52  758.84  911.65
   779.3  917.57  857.64  919.06   890.2  933.77  914.23   934.5  939.03  939.54
#Mann= 6 ,-1,0
 -357.15    .145       0  -20.04    .035       0    21.9     .14       0
   54.24      .1       0  713.05     .06       0  749.75      .1       0
Bank Sta=-20.04,21.9
XS Rating Curve= 0 ,0
Exp/Cntr=0.3,0.1

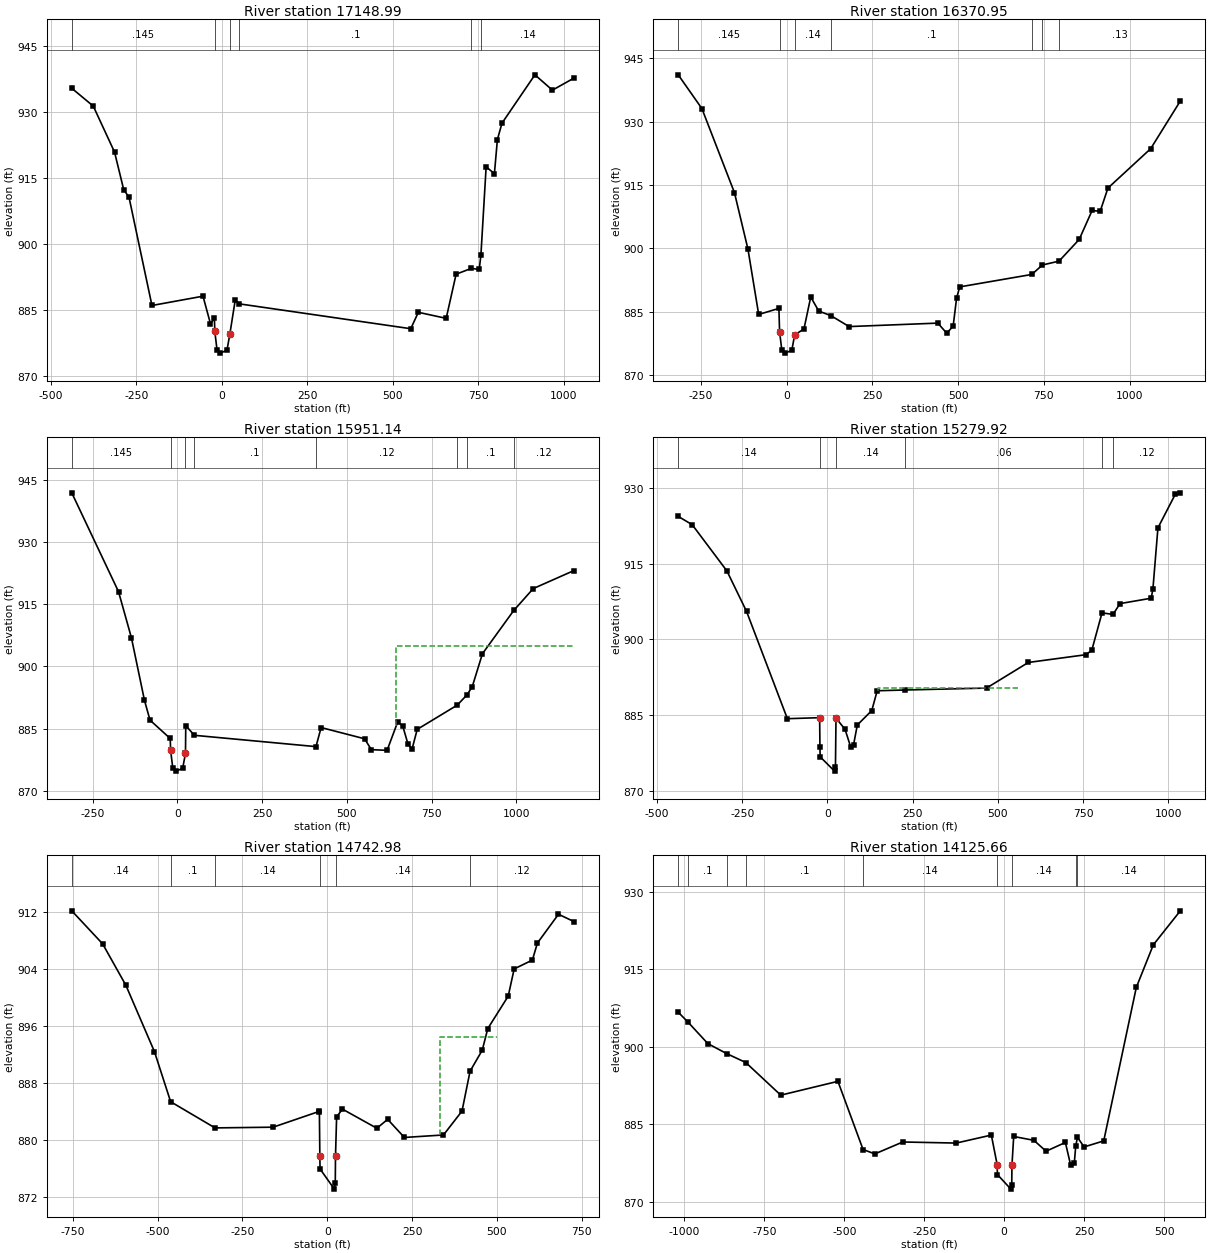
Type RM Length L Ch R = 1 ,17148.99,722.3938,778.0375,748.7724
XS GIS Cut Line= 3
   1475301.60236   1109547.77986   1475117.57415   1109947.08629
   1474680.07349    1110877.6437
#Sta/Elev= 30
 -438.39  935.45  -375.5  931.38 -313.37  920.92 -286.45  912.33 -271.05  910.64
 -203.96  885.97  -54.67  888.09  -32.86  881.81  -21.34  883.04  -20.25  880.16
  -13.66   875.8    -4.3  875.12   15.38  875.78   23.72  879.42    39.6  887.24
   51.54  886.34  552.79  880.68  574.83  884.42  656.32  883.04  685.31   893.1
   730.1  894.43  752.88  894.17  757.88  897.49  773.13  917.57  797.27  915.99
  806.06  923.77  819.41  927.49  915.72  938.51  966.91  935.02 1029.56  937.75
#Mann= 6 ,-1,0
 -438.39    .145       0  -20.25     .04       0   23.72     .14       0
   51.54      .1       0   730.1     .06       0  757.88     .14       0
Bank Sta=-20.25,23.72
XS Rating Curve= 0 ,0
Exp/Cntr=0.3,0.1

Type RM Length L Ch R = 1 ,16370.95,393.6167,419.8099,538.7955
BEGIN DESCRIPTION:
TWE_08X
END DESCRIPTION:
XS GIS Cut Line= 3
   1474600.21227   1109401.94619    1474445.3937   1109676.64633
    1473905.7664   1110690.14337
#Sta/Elev= 30
 -315.66  941.05 -246.65  933.06 -151.79  913.18  -112.4   899.8  -81.16  884.37
   -22.2   885.8  -20.25  880.26  -13.66   875.9    -4.3  875.22   15.38  875.88
   23.72  879.52   50.83  880.94   70.58   888.5   93.89  885.17  129.28  884.09
  182.44   881.5  441.01  882.32  467.03  879.93  485.68   881.6  495.86  888.32
  504.98  890.89  714.92  893.83   745.9  896.07  794.37  896.98  853.12  902.11
  890.76  908.96  914.26  908.76  936.88  914.26  1061.5  923.58 1147.87  934.85
#Mann= 7 ,-1,0
 -315.66    .145       0  -20.25     .04       0   23.72     .14       0
  129.28      .1       0  714.92     .06       0   745.9      .1       0
  794.37     .13       0
Bank Sta=-20.25,23.72
XS Rating Curve= 0 ,0
Exp/Cntr=0.3,0.1

Type RM Length L Ch R = 1 ,15951.14,634.259,671.2197,597.0951
XS GIS Cut Line= 3
   1474433.54528   1109179.72375   1474183.54495   1109363.75197
   1473232.15387   1110047.78084
#Sta/Elev= 30
 -311.99  941.84 -173.96     918 -135.85  906.87  -97.35  891.78  -80.98  887.01
  -21.34  882.59  -20.25  879.76  -13.66   875.4    -4.3  874.72   15.38  875.38
   23.72  879.02   24.53  885.71   49.76  883.36  408.95  880.63  424.13  885.23
  552.48  882.52  572.39   879.9  618.87  879.73  650.14  886.57  664.98  885.63
  680.57  881.25  692.38  879.97  707.81  884.79  825.83  890.63  855.46  893.17
  870.33   895.1  900.27  903.02  992.83  913.47 1050.45  918.75 1170.21  923.08
#Mann= 8 ,-1,0
 -311.99    .145       0  -20.25     .04       0   23.72     .14       0
   49.76      .1       0  408.95     .12       0  825.83     .06       0
  855.46      .1       0  992.83     .12       0
#XS Ineff= 2 , 0
                          645.63          904.95
Permanent Ineff=
       F       F
Bank Sta=-20.25,23.72
XS Rating Curve= 0 ,0
Exp/Cntr=0.3,0.1

Type RM Length L Ch R = 1 ,15279.92,420.462,536.9451,576.9656
XS GIS Cut Line= 5
   1474198.43045   1108709.60466   1473967.45801   1108766.40125
   1473812.21424   1108881.88747   1473469.54199   1109194.26804
   1472914.82972    1109355.1916
#Sta/Elev= 30
 -437.52  924.32 -396.52  922.68 -294.79  913.53 -237.25  905.53 -117.42  884.28
   -22.8  884.48  -21.86  878.61  -21.21  876.73   20.95   873.9   23.65  874.78
   25.18  884.41   51.85  882.15   67.87  878.77   76.61  879.06   87.67  883.03
  130.12  885.89  146.08  889.81  227.78  889.96   466.7  890.34  589.28  895.41
  757.54  896.94  775.39   897.8  805.44  905.23  837.82  904.92  858.09  907.06
  949.77  908.13  954.83  910.04  969.44  922.05 1020.32   928.7 1035.09  928.99
#Mann= 6 ,-1,0
 -437.52     .14       0   -22.8     .04       0   25.18     .14       0
  227.78     .06       0  805.44     .06       0  837.82     .12       0
#XS Ineff= 1 ,-1
  149.42  560.36  890.38
Permanent Ineff=
       F
Bank Sta=-22.8,25.18
XS Rating Curve= 0 ,0
Exp/Cntr=0.3,0.1

Type RM Length L Ch R = 1 ,14742.98,439.5438,617.3231,671.8304
XS GIS Cut Line= 4
   1474197.43373   1108599.86122    1473937.0164   1108412.36089
   1473523.82119   1108506.11089   1472815.48622    1108700.5561
#Sta/Elev= 30
 -752.65  912.13 -661.71   907.5 -593.17  901.69 -509.03  892.39 -461.38  885.38
 -330.57  881.71 -159.52  881.81  -23.77  884.02  -23.14   883.9  -21.86  877.84
  -21.21  875.96   20.95  873.13   23.65  874.01   24.31  877.73   27.61  883.26
   44.79  884.34  146.11  881.66  177.92  882.91  227.26  880.37  342.43  880.72
  397.03  884.07   420.7  889.65  456.64   892.6  472.93  895.63  533.09  900.17
  550.64  903.99  604.36  905.23  619.06  907.61  681.23  911.65  726.48  910.63
#Mann= 6 ,-1,0
 -752.65     .14       0 -461.38      .1       0 -330.57     .14       0
  -21.86     .04       0   24.31     .14       0   420.7     .12       0
#XS Ineff= 1 ,-1
  331.03   499.8894.4954
Permanent Ineff=
       F
Bank Sta=-21.86,24.31
XS Rating Curve= 0 ,0
Exp/Cntr=0.3,0.1

Type RM Length L Ch R = 1 ,14125.66,290.9466,620.2021,640.5469
BEGIN DESCRIPTION:
TWE_07X
END DESCRIPTION:
XS GIS Cut Line= 5
   1474168.05118   1108545.20472   1473996.54724   1108134.82119
   1473453.86155   1107944.94259   1473218.65682   1107872.66601
   1472989.09777   1107672.77592
#Sta/Elev= 30
-1019.34   906.7 -988.89  904.79 -926.67  900.61 -867.62  898.67 -808.13  896.95
 -698.68  890.62 -519.92   893.3 -441.33  880.08 -404.44  879.23 -317.04  881.54
 -150.11  881.33  -40.11  882.88  -21.86  877.11  -21.21  875.23   20.95   872.4
   23.65  873.28   24.31     877   29.74  882.61   92.94  881.86  131.07  879.75
  191.41  881.45  207.61  877.12  219.32  877.46  223.69   880.7  229.11  882.44
  249.96  880.58  311.32  881.75  413.26  911.52  466.42  919.77  550.83  926.36
#Mann= 9 ,-1,0
-1019.34     .14       0 -988.89      .1       0 -867.62     .14       0
 -808.13      .1       0 -441.33     .14       0  -21.86     .04       0
   24.31     .14       0  223.69      .1       0  229.11     .14       0
Bank Sta=-21.86,24.31
XS Rating Curve= 0 ,0
Exp/Cntr=0.3,0.1