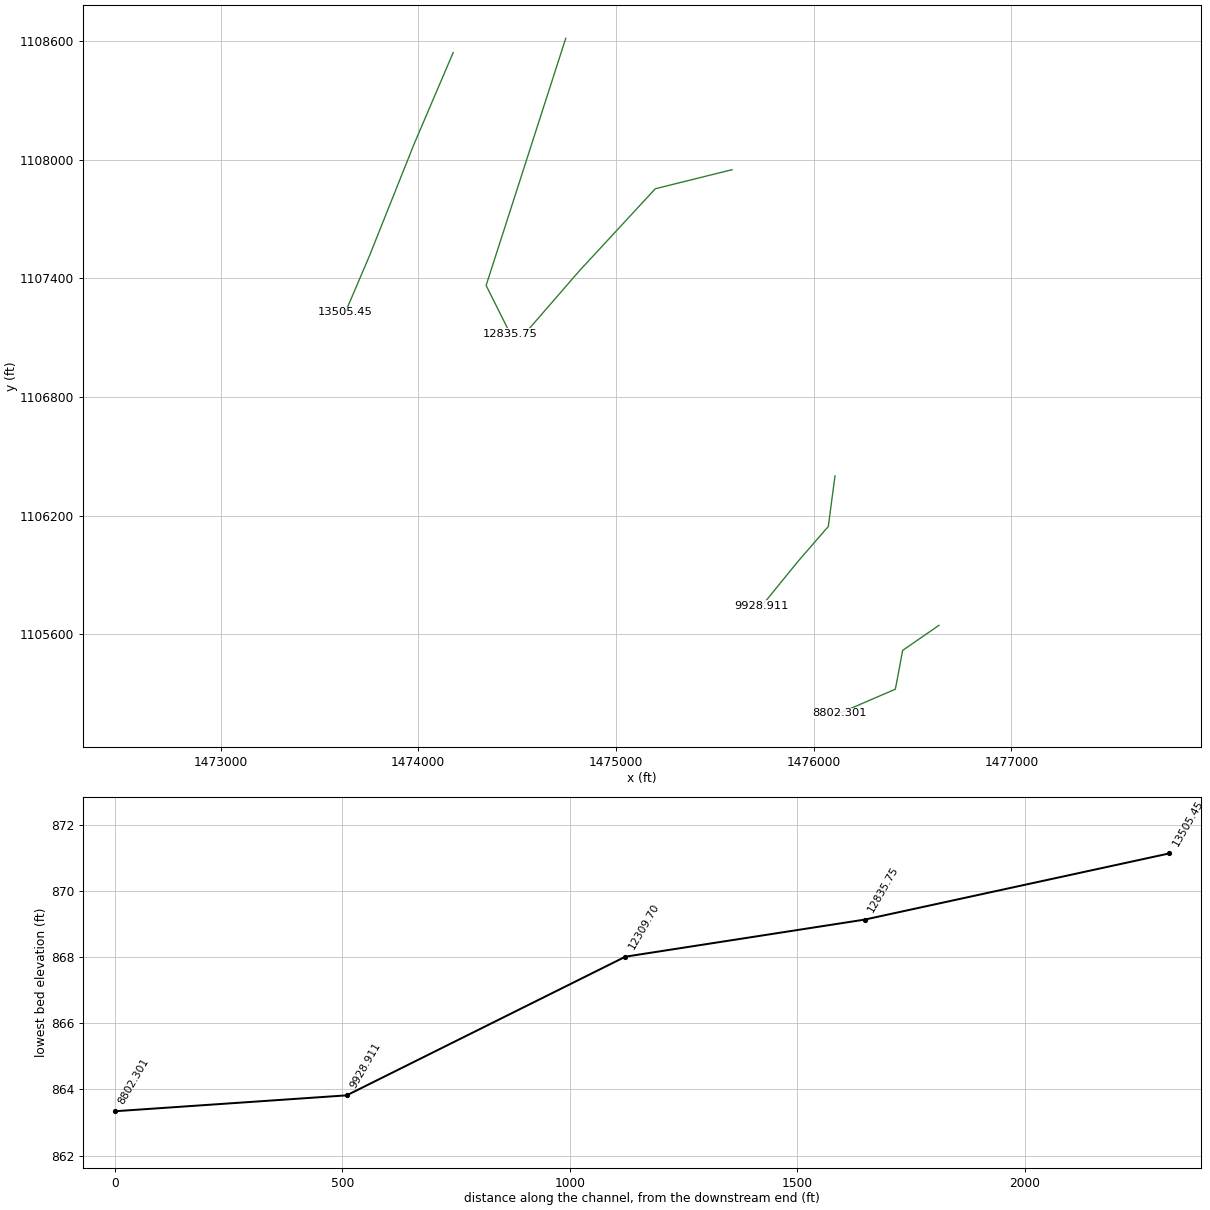
HEC-RAS study 12mile_Combined.prj: 12mile Creek Combined Model

--- 12mile_Combined.g01 (geometry) --- (continued)

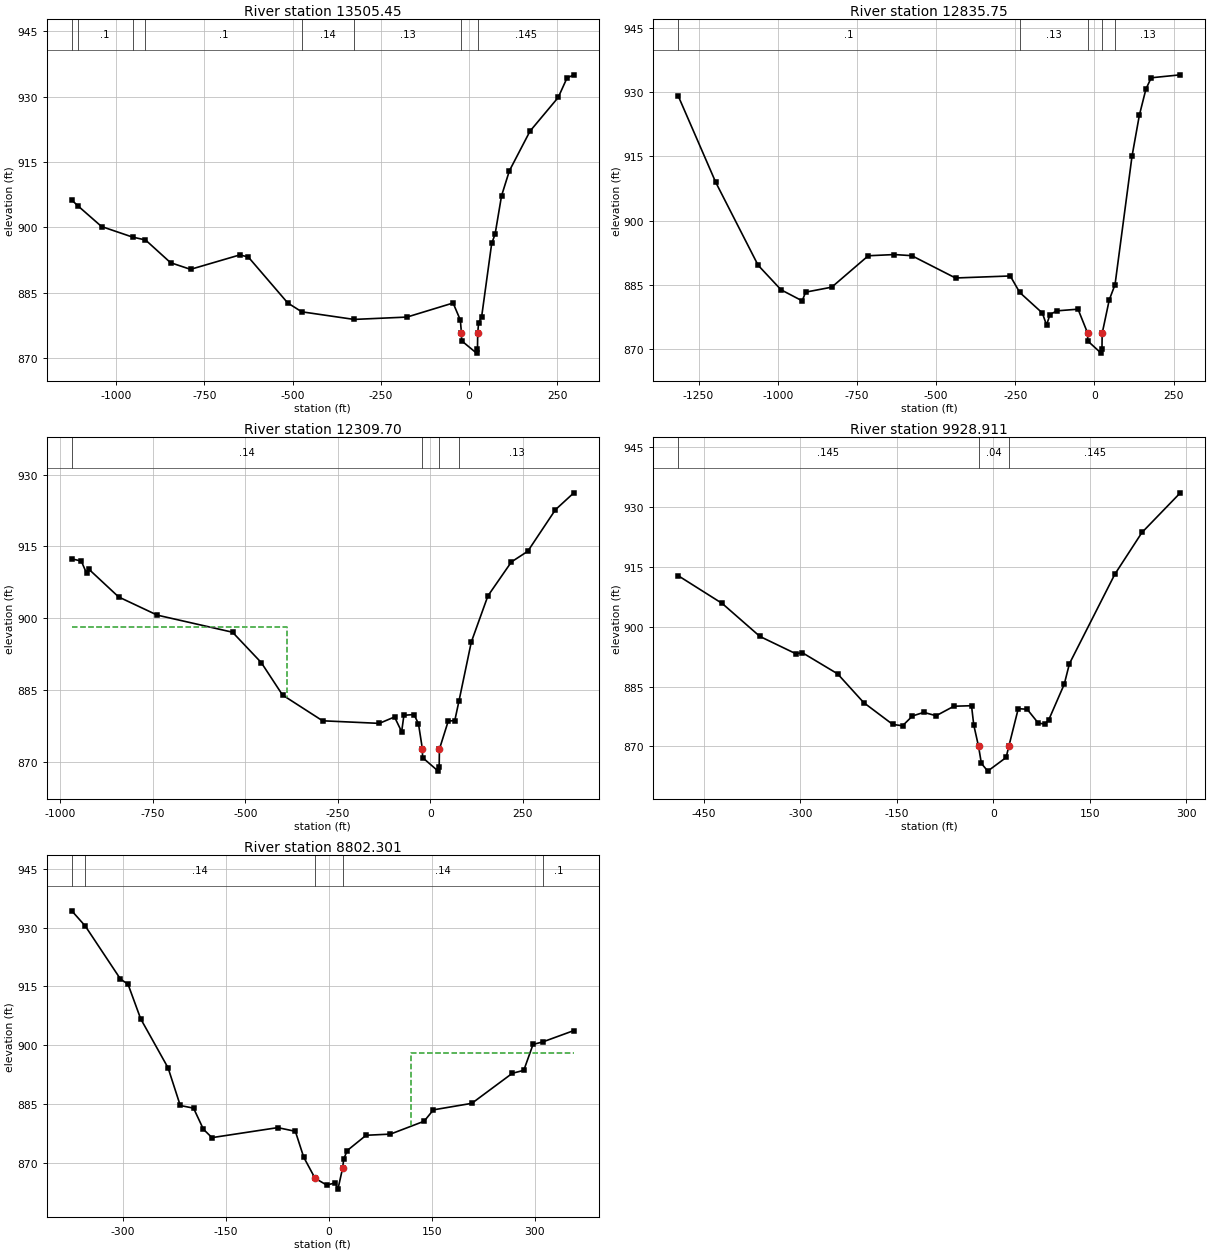
Type RM Length L Ch R = 1 ,13505.45,593.0652,669.6997,674.7907
XS GIS Cut Line= 4
   1474176.62631   1108541.52953   1473978.17192   1108077.24508
   1473752.98819   1107513.05348    1473631.4603   1107228.33104
#Sta/Elev= 30
-1125.39  906.28-1108.38  904.98-1041.04   900.2 -952.89  897.77 -916.62  897.12
 -845.65   891.9 -789.02  890.37 -649.54  893.68 -625.53  893.21 -513.71  882.65
 -474.13  880.62 -325.87  878.87 -176.06  879.41  -45.41  882.64  -24.94  878.73
  -21.86  875.84  -21.21  873.96   20.95  871.13   23.65  872.01   24.31  875.73
   26.92  878.14   35.25  879.38   63.87  896.32   73.48  898.43   91.78  907.25
     114     913  172.46  922.11  252.23  929.84  277.18  934.31  296.57  935.04
#Mann= 8 ,-1,0
-1125.39     .14       0-1108.38      .1       0 -952.89     .14       0
 -916.62      .1       0 -474.13     .14       0 -325.87     .13       0
  -21.86     .04       0   24.31    .145       0
Bank Sta=-21.86,24.31
XS Rating Curve= 0 ,0
Exp/Cntr=0.3,0.1

Type RM Length L Ch R = 1 ,12835.75,550.2411,526.0508,447.1309
XS GIS Cut Line= 3
   1474746.04593   1108613.75033   1474343.26739    1107363.7477
   1474464.79528    1107120.6916
#Sta/Elev= 30
-1314.03  929.05-1195.56  908.92-1061.89  889.61 -989.31  883.88 -922.62  881.31
 -911.92  883.34 -829.43   884.5 -714.09  891.82 -631.73   892.1 -576.79  891.84
 -438.68  886.64 -265.82  887.11 -235.95  883.27 -164.48  878.47 -151.31  875.68
 -140.45   878.1 -119.24  878.98  -51.87  879.37  -21.86  873.84  -21.21  871.96
   20.95  869.13   23.65  870.01   24.31  873.73   46.74  881.55    64.9  885.09
  118.53  915.01  141.83   924.6  162.49  930.67  179.15  933.29  271.01  933.98
#Mann= 5 ,-1,0
-1314.03      .1       0 -235.95     .13       0  -21.86     .04       0
   24.31     .13       0    64.9     .13       0
#XS Ineff= 1 ,-1
-1127.15 -703.94  889.96
Permanent Ineff=
       F
Bank Sta=-21.86,24.31
XS Rating Curve= 0 ,0
Exp/Cntr=0.3,0.1

Type RM Length L Ch R = 1 ,12309.70,680.5234,612.7648,355.1502
XS GIS Cut Line= 4
   1475587.19324    1107949.2523   1475199.17192   1107852.89797
   1474813.75427   1107436.23064    1474558.5456   1107141.95899
#Sta/Elev= 30
  -969.3  912.36 -943.64  911.92 -929.06  909.32 -922.59  910.17 -842.62  904.41
 -738.26  900.61 -534.83  897.04 -457.14  890.69 -399.72  883.92 -291.47  878.53
 -138.17  877.99  -97.03  879.33  -77.77  876.24  -71.65  879.68   -44.3  879.84
  -32.25  877.89  -21.86  872.72  -21.21  870.84   20.95  868.01   23.65  868.89
   24.31  872.61    48.2  878.48   65.78  878.56   77.29  882.71  110.41  894.97
  155.34  904.63  218.87  911.73  263.11  913.96  337.86  922.64  387.61  926.17
#Mann= 4 ,-1,0
  -969.3     .14       0  -21.86     .04       0   24.31     .14       0
   77.29     .13       0
#XS Ineff= 2 , 0
         -386.61  898.07
Permanent Ineff=
       F       F
Bank Sta=-21.86,24.31
XS Rating Curve= 0 ,0
Exp/Cntr=0.3,0.1

Type RM Length L Ch R = 1 ,9928.911,521.736,509.2589,310.9061
BEGIN DESCRIPTION:
TWE_06X
END DESCRIPTION:
XS GIS Cut Line= 4
   1476108.02756   1106399.77034   1476074.17356   1106144.56135
   1475921.69652   1105968.92454   1475738.23524   1105743.51903
#Sta/Elev= 30
 -489.97  912.78  -421.6  905.83 -363.01  897.57 -307.21  893.24 -296.98  893.49
  -242.2   888.2 -201.61  880.99 -156.44  875.52 -141.23  875.18 -125.75  877.64
 -108.24  878.54  -88.95   877.7  -61.41  880.08  -33.95  880.21   -30.5  875.41
     -23     870  -18.65  865.77   -8.75  863.82   19.84  867.24      24     870
   38.72  879.47   52.57  879.32   69.85  875.85   79.73  875.62   85.96  876.61
  110.23   885.6  118.29  890.74  188.77  913.12  231.04  923.61  290.69  933.55
#Mann= 3 ,-1,0
 -489.97    .145       0     -23     .04       0      24    .145       0
Bank Sta=-23,24
XS Rating Curve= 0 ,0
Exp/Cntr=0.3,0.1

Type RM Length L Ch R = 1 ,8802.301,132.8714,92.11585,37.6268
BEGIN DESCRIPTION:
TWE_05USX
END DESCRIPTION:
XS GIS Cut Line= 5
   1476634.07054   1105644.56037   1476450.24344    1105517.7185
   1476422.40682   1105368.48458   1476413.12828   1105321.31759
   1476129.35171   1105199.14665
#Sta/Elev= 30
 -374.95  934.25 -355.29  930.38 -303.99  916.88 -292.87  915.53 -274.47  906.74
 -234.48  894.23 -216.76  884.65 -197.34  883.97 -182.99  878.59 -170.49  876.46
  -74.54  879.01  -48.88  878.07  -36.72  871.48   -20.2  866.11   -3.21  864.38
    9.21  864.93   13.22  863.34   19.92  868.61   21.69  871.04   26.82  873.18
   54.25  877.06   89.85  877.36  138.87  880.64  152.42  883.54  208.43   885.2
  267.47  892.85  284.23  893.61  297.72  900.21  311.91  900.85  357.23  903.74
#Mann= 5 ,-1,0
 -374.95      .1       0 -355.29     .14       0   -20.2     .04       0
   19.92     .14       0  311.91      .1       0
#XS Ineff= 2 , 0
                          119.99          897.95
Permanent Ineff=
       F       F
Bank Sta=-20.2,19.92
XS Rating Curve= 0 ,0
Exp/Cntr=0.5,0.3