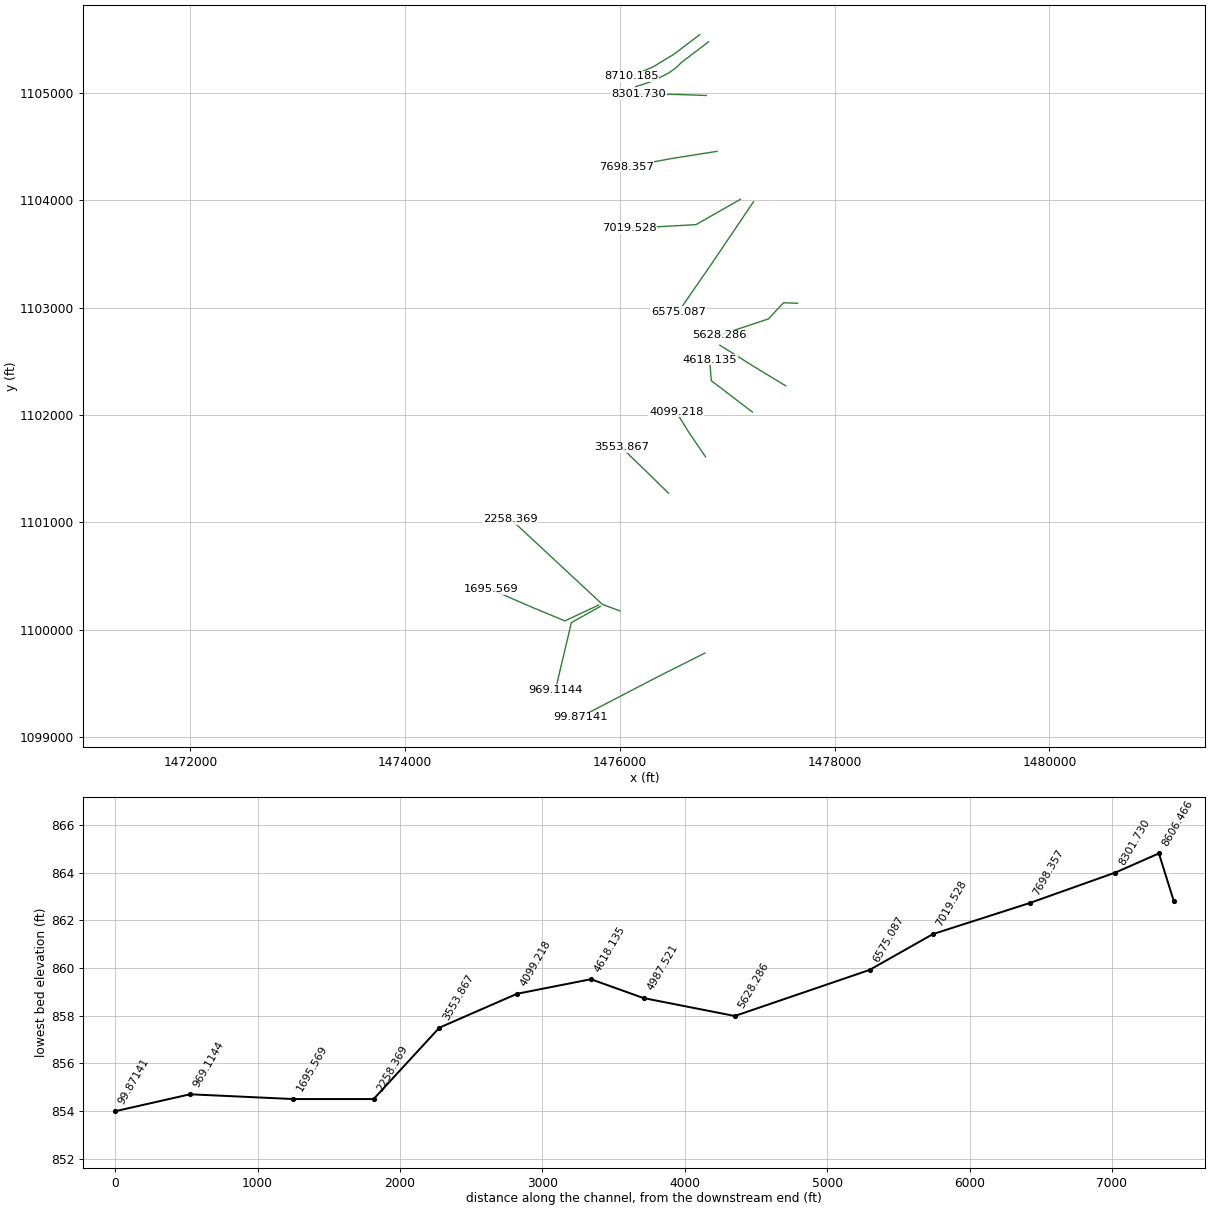
HEC-RAS study 12mile_Combined.prj: 12mile Creek Combined Model

--- 12mile_Combined.g01 (geometry) --- (continued)

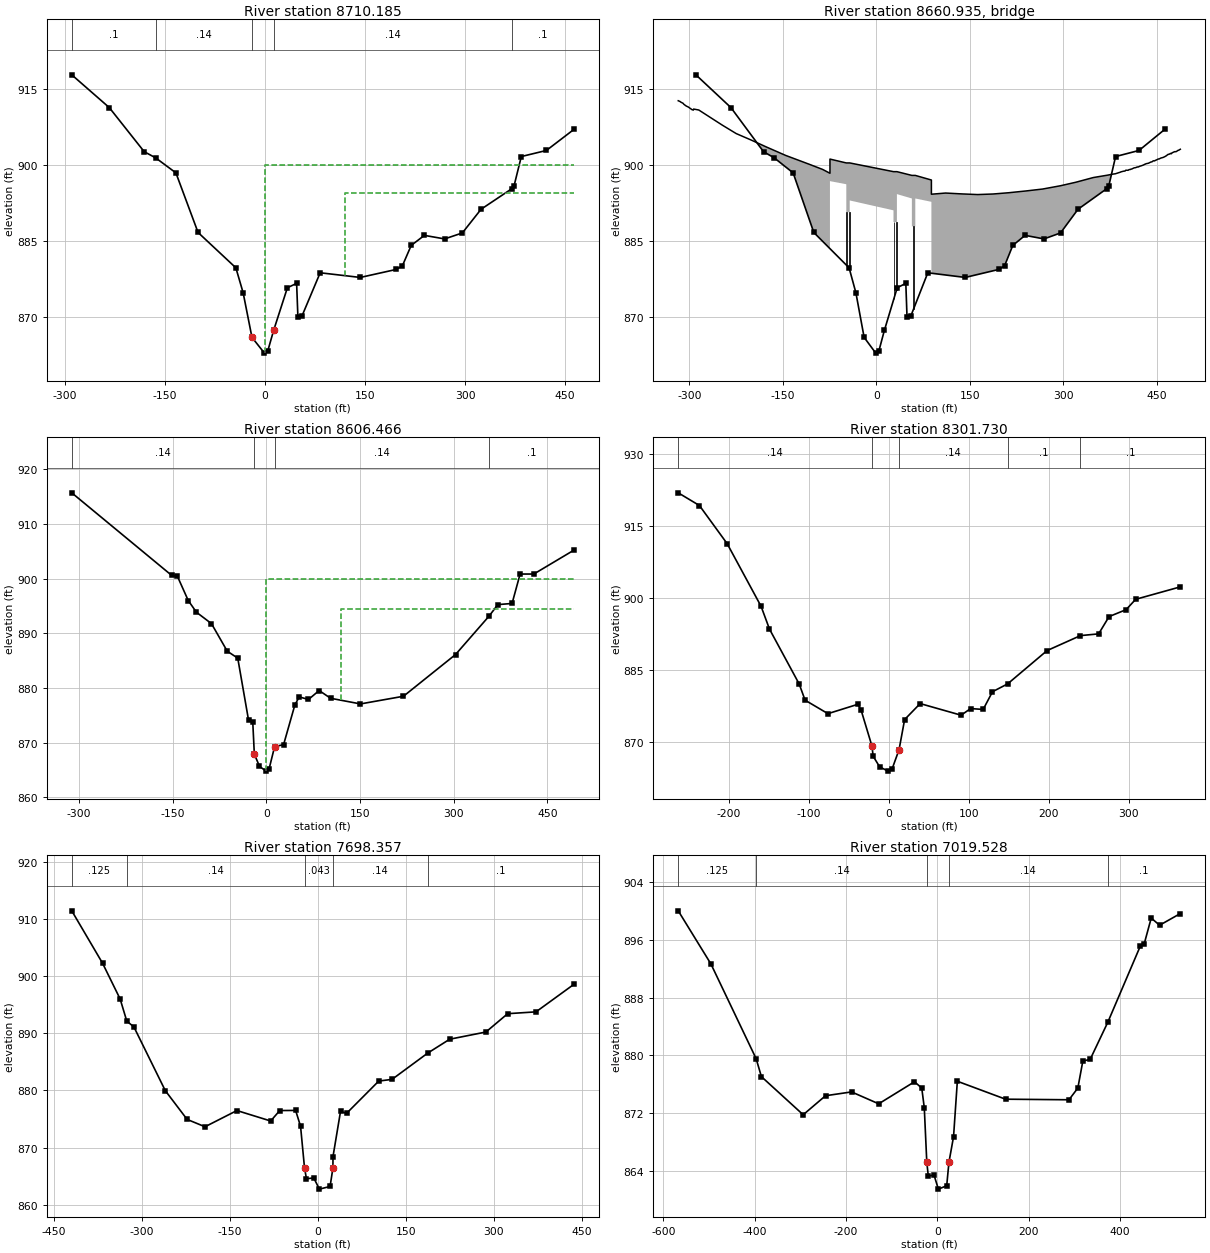
Type RM Length L Ch R = 1 ,8710.185,103.9837,103.7191,140.4866
BEGIN DESCRIPTION:
Allgoud Bridge Dr (TWE_05) - US
END DESCRIPTION:
XS GIS Cut Line= 5
   1476744.19521   1105543.17126   1476503.45604   1105360.07382
   1476427.71129   1105314.85466   1476313.57743   1105244.79035
   1476105.04954   1105153.24147
#Sta/Elev= 30
 -289.38  917.72 -233.19  911.26 -180.86  902.56 -163.67  901.34 -133.34  898.38
 -100.14  886.62   -43.5  879.65  -32.56  874.71  -19.38  865.93    -.69  862.82
    4.23  863.21   13.07  867.29   33.71  875.72   47.55  876.58   49.46  869.97
   55.82  870.22   82.83  878.67  142.94  877.75  197.15  879.34  206.04  880.05
  219.26  884.07  238.97  886.05  269.33  885.35  295.87  886.53   323.9   891.2
  369.95  895.25  373.17  895.72  384.22   901.6  421.82   902.8  462.95  906.94
#Mann= 5 ,-1,0
 -289.38      .1       0 -163.67     .14       0  -19.38     .04       0
   13.07     .14       0  369.95      .1       0
#XS Ineff= 2 , 0
       0    -105     900     120       0   894.5
Permanent Ineff=
       F       F
Bank Sta=-19.38,13.07
XS Rating Curve= 0 ,0
Exp/Cntr=0.5,0.3

Type RM Length L Ch R = 3 ,8660.935,,,
BEGIN DESCRIPTION:
Allgoud Bridge Dr (TWE_05) - TOR
END DESCRIPTION:
Bridge Culvert--1,0,-1,-1, 0
Deck Dist Width WeirC Skew NumUp NumDn MinLoCord MaxHiCord MaxSubmerge Is_Ogee
32.5,33.5,2.6,0, 156, 156, 894.1, , 0.95, 0, 0,0,,
 -317.73 -317.01 -314.75 -314.45 -314.13 -313.49 -310.25 -310.06 -308.47 -307.35
 -305.96 -304.19 -301.57 -299.89  -298.9  -296.3 -295.59 -293.98 -293.33 -293.05
 -284.75 -247.07 -224.71 -200.78  -176.3 -145.47 -116.36 -107.51  -85.99  -74.22
  -74.22     -48     -48   -42.5   -42.5   27.75   27.75   33.25   33.25   57.25
   57.25   62.75   62.75    88.6    88.6  111.38  114.27  137.44  162.84  187.52
  212.58  236.64  240.99  267.09  295.79  320.67  348.52  370.95  380.18  383.46
  383.57  383.89  385.27  387.33  388.08  388.89  389.22  389.72  390.34  390.85
  392.17  392.42  392.94  395.15  396.26  396.94  398.64  399.29  400.57  400.88
  403.96  404.21  404.29  406.06   407.9  408.36  410.13  412.42  412.45  412.74
  413.81  415.36  416.45  418.57  419.09  420.05  421.33  423.04  424.63   424.9
  425.86   428.4  428.71  431.05  431.52  431.91  432.54  433.07  436.75  436.93
  436.94  440.25  440.69   440.7  442.63  444.48  444.62  444.68  445.22  446.86
  448.07   449.1  451.98  452.31  452.89  454.27   456.1  456.58  458.07  458.26
  460.18  460.44   463.6  464.28  465.04  467.87  468.27  468.58  469.53   470.8
  472.52  473.67   474.6   474.9  476.57  477.59   479.3  479.78   481.7   483.5
  484.23  485.32  485.68  487.41  487.81   488.1
  912.61  912.57  912.44  912.43  912.38  912.33  912.12  912.11  911.88  911.79
  911.65  911.52  911.37  911.23  911.16  910.91  910.84  910.78  910.77  910.97
  910.78   907.8  906.13  904.86  903.49  901.83   900.5  900.08  899.06   898.3
   901.1  900.34  900.34  900.34  900.34  898.62  898.62  898.62  898.62  897.88
  897.88  897.88  897.88  896.97  894.17   894.4  894.38  894.23   894.1  894.21
  894.46  894.76  894.82  895.19  895.84  896.54  897.46  897.92  898.14  898.19
  898.19   898.2  898.26  898.35  898.38  898.42  898.44  898.45  898.46  898.47
  898.54  898.53  898.58  898.65  898.67  898.71  898.72  898.74   898.9   898.9
  898.89  898.89  898.89  899.03  899.04  899.09  899.14  899.28  899.28   899.3
  899.36  899.39  899.41  899.54  899.55  899.53  899.58  899.69  899.74  899.76
  899.79  899.91  899.92  900.07   900.1   900.1  900.14  900.18  900.27  900.28
  900.28  900.48  900.51  900.51  900.56  900.74  900.74  900.75  900.76  900.74
  900.85  900.89  901.08  901.09  901.12  901.13  901.25  901.29  901.34  901.36
  901.42  901.42   901.6  901.67   901.7  901.97  902.01  902.04  902.03   902.1
  902.23  902.15  902.28  902.33  902.44  902.49  902.57  902.55  902.58  902.73
  902.81  902.83  902.86  903.01  903.02  903.04
                                                                                
                                                                                
                                                                                
  896.75  896.14  890.64  890.64  892.94  890.99  888.69  888.69  894.19  893.33
  887.83  887.83  893.33  892.67
                                                                                
                                                                                
                                                                                
                                                                                
                                                                                
                                                                                
                                                                                
                                                                                
                                                                                
                                                                                
                                                
 -317.73 -317.01 -314.75 -314.45 -314.13 -313.49 -310.25 -310.06 -308.47 -307.35
 -305.96 -304.19 -301.57 -299.89  -298.9  -296.3 -295.59 -293.98 -293.33 -293.05
 -284.75 -247.07 -224.71 -200.78  -176.3 -145.47 -116.36 -107.51  -85.99  -74.22
  -74.22     -48     -48   -42.5   -42.5   27.75   27.75   33.25   33.25   57.25
   57.25   62.75   62.75    88.6    88.6  111.38  114.27  137.44  162.84  187.52
  212.58  236.64  240.99  267.09  295.79  320.67  348.52  370.95  380.18  383.46
  383.57  383.89  385.27  387.33  388.08  388.89  389.22  389.72  390.34  390.85
  392.17  392.42  392.94  395.15  396.26  396.94  398.64  399.29  400.57  400.88
  403.96  404.21  404.29  406.06   407.9  408.36  410.13  412.42  412.45  412.74
  413.81  415.36  416.45  418.57  419.09  420.05  421.33  423.04  424.63   424.9
  425.86   428.4  428.71  431.05  431.52  431.91  432.54  433.07  436.75  436.93
  436.94  440.25  440.69   440.7  442.63  444.48  444.62  444.68  445.22  446.86
  448.07   449.1  451.98  452.31  452.89  454.27   456.1  456.58  458.07  458.26
  460.18  460.44   463.6  464.28  465.04  467.87  468.27  468.58  469.53   470.8
  472.52  473.67   474.6   474.9  476.57  477.59   479.3  479.78   481.7   483.5
  484.23  485.32  485.68  487.41  487.81   488.1
  912.61  912.57  912.44  912.43  912.38  912.33  912.12  912.11  911.88  911.79
  911.65  911.52  911.37  911.23  911.16  910.91  910.84  910.78  910.77  910.97
  910.78   907.8  906.13  904.86  903.49  901.83   900.5  900.08  899.06   898.3
   901.1  900.34  900.34  900.34  900.34  898.62  898.62  898.62  898.62  897.88
  897.88  897.88  897.88  896.97  894.17   894.4  894.38  894.23   894.1  894.21
  894.46  894.76  894.82  895.19  895.84  896.54  897.46  897.92  898.14  898.19
  898.19   898.2  898.26  898.35  898.38  898.42  898.44  898.45  898.46  898.47
  898.54  898.53  898.58  898.65  898.67  898.71  898.72  898.74   898.9   898.9
  898.89  898.89  898.89  899.03  899.04  899.09  899.14  899.28  899.28   899.3
  899.36  899.39  899.41  899.54  899.55  899.53  899.58  899.69  899.74  899.76
  899.79  899.91  899.92  900.07   900.1   900.1  900.14  900.18  900.27  900.28
  900.28  900.48  900.51  900.51  900.56  900.74  900.74  900.75  900.76  900.74
  900.85  900.89  901.08  901.09  901.12  901.13  901.25  901.29  901.34  901.36
  901.42  901.42   901.6  901.67   901.7  901.97  902.01  902.04  902.03   902.1
  902.23  902.15  902.28  902.33  902.44  902.49  902.57  902.55  902.58  902.73
  902.81  902.83  902.86  903.01  903.02  903.04
                                                                                
                                                                                
                                                                                
  896.75  896.14  890.64  890.64  892.94  890.99  888.69  888.69  894.19  893.33
  887.83  887.83  893.33  892.67
                                                                                
                                                                                
                                                                                
                                                                                
                                                                                
                                                                                
                                                                                
                                                                                
                                                                                
                                                                                
                                                
Pier Skew, UpSta & Num, DnSta & Num=  ,-47.5, 2 ,-47.5, 2 , 0 , 0 , 0 ,,
       1       1
     860     897
       1       1
     860     897
Pier Skew, UpSta & Num, DnSta & Num=  ,-43, 2 ,-43, 2 , 0 , 0 , 0 ,,
       1       1
     860     897
       1       1
     860     897
Pier Skew, UpSta & Num, DnSta & Num=  ,28.5, 2 ,28.5, 2 , 0 , 0 , 0 ,,
       1       1
     860     897
       1       1
     860     897
Pier Skew, UpSta & Num, DnSta & Num=  ,32.5, 2 ,32.5, 2 , 0 , 0 , 0 ,,
       1       1
     860     897
       1       1
     860     897
Pier Skew, UpSta & Num, DnSta & Num=  ,60, 2 ,60, 2 , 0 , 0 , 0 ,,
       1       1
     860     897
       1       1
     860     897
Abutment Skew #Up #Dn= , 2 , 2
  -74.22  -47.07
  896.75  880.04
  -74.22  -47.07
  896.75  880.04
Abutment Skew #Up #Dn= , 2 , 2
   60.54    88.6
  871.18  892.67
   60.54    88.6
  871.18  892.67
BR Coef=-1 , 1 , 0 ,, 0 ,,,0.8,0,1.2,0,
WSPro=,,,, 1 ,,,, 0 ,,,, 0 ,,,,-1 ,-1 ,-1 , 0 , 0 , 0 , 0 , 0
BC Design=,, 0 ,, 0 ,,,,,,
BC Use User HTab Curves=0
BC User HTab FreeFlow(D)= 0

Type RM Length L Ch R = 1 ,8606.466,318.6339,304.7363,258.2462
BEGIN DESCRIPTION:
Allgoud Bridge Dr (TWE_05) - DS
END DESCRIPTION:
XS GIS Cut Line= 6
   1476824.72441   1105475.35728   1476573.81299   1105283.78314
   1476516.17126   1105228.68438   1476452.59547   1105184.60531
   1476302.65978   1105108.77625    1476147.4334   1105058.30184
#Sta/Elev= 30
 -311.75  915.69 -151.84   900.6 -142.69  900.46 -125.24     896 -112.15  893.86
  -88.01  891.77  -62.74  886.73  -45.93  885.46  -28.66  874.13  -21.89  873.77
  -19.38  867.91  -11.13  865.68    -.69   864.8    4.23  865.19   13.07  869.27
   27.49  869.65   45.46  876.87   52.48  878.38   67.32   877.9   84.41  879.54
  102.79  878.12  150.59  877.09  219.44  878.49  302.84  886.12  356.28  893.11
  370.56  895.25  393.39  895.46  406.25  900.84  428.21  900.84  492.32   905.2
#Mann= 4 ,-1,0
 -311.75     .14       0  -19.38     .04       0   13.07     .14       0
  356.28      .1       0
#XS Ineff= 2 , 0
       0    -105     900     120       0   894.5
Permanent Ineff=
       F       F
Bank Sta=-19.38,13.07
XS Rating Curve= 0 ,0
Exp/Cntr=0.5,0.3

Type RM Length L Ch R = 1 ,8301.730,570.8895,603.3726,607.1384
XS GIS Cut Line= 3
   1476804.64403    1104975.9393   1476542.92454   1104985.05381
   1476177.03839   1104990.26214
#Sta/Elev= 30
 -263.05  921.97 -236.58  919.33 -201.83  911.37 -159.44  898.32 -148.97  893.59
 -111.79  882.14 -104.45  878.78  -75.86  875.97  -38.45  877.92   -34.4  876.71
  -20.72  869.16  -19.38  867.11  -11.13  864.88    -.69     864    4.23  864.39
   13.07  868.47   20.02  874.74   39.45  878.07   90.63  875.65  102.57  877.03
  118.23  876.85   129.9  880.54   148.8  882.17  198.14  889.11  239.92  892.23
  262.61  892.59  275.68  896.19  296.91  897.63  308.92  899.79  364.75  902.38
#Mann= 5 ,-1,0
 -263.05     .14       0  -20.72     .04       0   13.07     .14       0
   148.8      .1       0  239.92      .1       0
Bank Sta=-20.72,13.07
XS Rating Curve= 0 ,0
Exp/Cntr=0.3,0.1

Type RM Length L Ch R = 1 ,7698.357,622.8832,678.829,623.3411
XS GIS Cut Line= 3
   1476904.47014   1104455.75591   1476487.80282   1104389.78346
    1476060.7185   1104311.65846
#Sta/Elev= 30
 -419.85  911.45 -367.32  902.27 -337.34     896 -326.06  892.14  -313.9  891.12
 -260.38  879.96 -223.22  874.93 -192.67  873.64 -138.27  876.48  -80.74  874.65
  -65.21  876.48  -38.17   876.5  -29.77  873.72  -23.02  866.42  -19.72  864.54
   -7.25  864.68    2.35  862.72   20.57  863.19    25.4  866.42   25.52  868.41
   38.37  876.34    48.6  875.98  103.52  881.64  126.23  881.94  187.03  886.54
  224.53  888.97  286.24  890.23  323.35  893.44  371.65  893.76  436.17  898.57
#Mann= 5 ,-1,0
 -419.85    .125       0 -326.06     .14       0  -23.02    .043       0
    25.4     .14       0  187.03      .1       0
Bank Sta=-23.02,25.4
XS Rating Curve= 0 ,0
Exp/Cntr=0.3,0.1

Type RM Length L Ch R = 1 ,7019.528,317.252,444.441,619.2998
BEGIN DESCRIPTION:
TWE_04X
END DESCRIPTION:
XS GIS Cut Line= 4
   1477122.70768   1104008.97047   1476708.67159   1103773.22769
    1476621.4836   1103768.25459   1476086.76017   1103738.74049
#Sta/Elev= 30
 -567.26  900.04 -495.72  892.67 -396.68  879.52 -385.15  877.03 -293.68  871.74
 -244.78  874.38 -187.78  874.91 -128.33  873.26  -49.96  876.32  -34.05  875.44
  -28.52  872.71  -23.02  865.12  -19.72  863.24   -7.25  863.38    2.35  861.42
   20.57  861.89    25.4  865.12   35.56  868.71   43.84  876.39  149.44   873.9
  288.29  873.82   307.7  875.45  318.61  879.19  334.72  879.43  373.29884.5801
  444.48  895.15  452.62  895.37  468.38  899.04  486.66  898.04  532.05  899.66
#Mann= 5 ,-1,0
 -567.26    .125       0 -396.68     .14       0  -23.02    .043       0
    25.4     .14       0  373.29      .1       0
Bank Sta=-23.02,25.4
XS Rating Curve= 0 ,0
Exp/Cntr=0.3,0.1

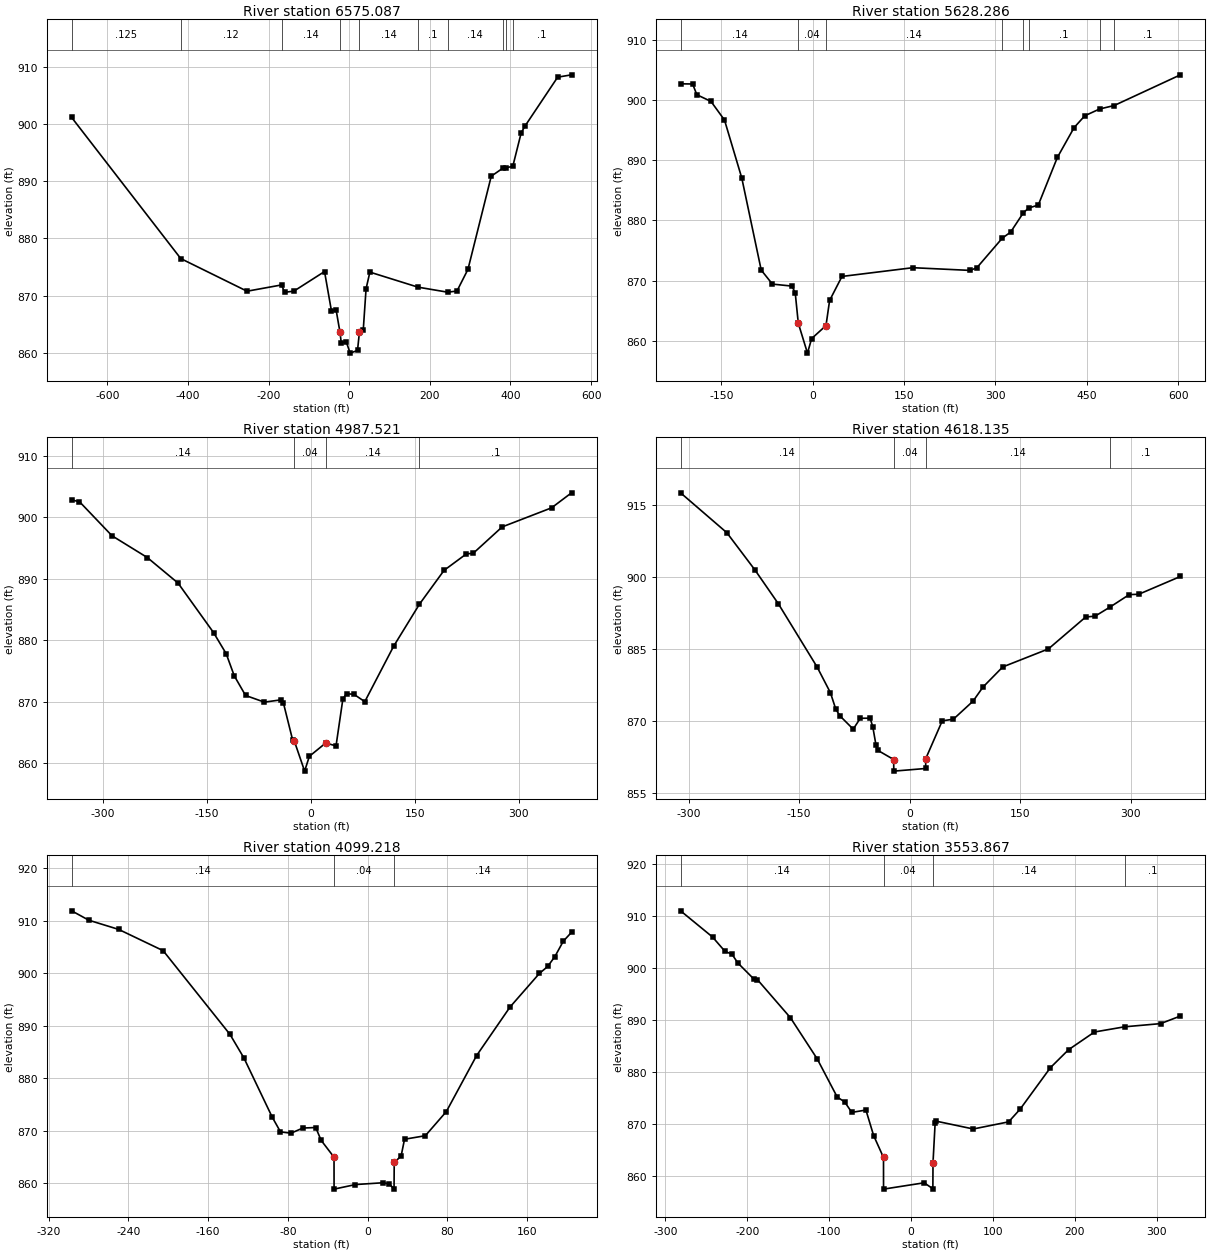
Type RM Length L Ch R = 1 ,6575.087,780.4042,946.8011,647.1896
XS GIS Cut Line= 3
   1477244.15781   1103985.77493   1476860.04265   1103417.19751
   1476545.37172   1102961.46752
#Sta/Elev= 30
 -688.52  901.14  -417.9  876.46 -253.42  870.75 -167.69  871.85 -160.47  870.56
 -137.36  870.76   -61.2  874.19  -44.23  867.36  -32.45  867.46  -23.02  863.62
  -19.72  861.74   -7.25  861.88    2.35  859.92   20.57  860.39    25.4  863.62
   34.91  864.03   41.81  871.17   51.27  874.09  170.66  871.46  244.17  870.58
   267.3  870.78  294.61  874.58  352.37  890.87  380.67  892.25  387.91  892.33
  405.79  892.59  426.64  898.46  435.83  899.61   517.1  908.19  551.46   908.6
#Mann= 10 ,-1,0
 -688.52    .125       0  -417.9     .12       0 -167.69     .14       0
  -23.02    .043       0    25.4     .14       0  170.66      .1       0
  244.17     .14       0  380.67      .1       0  387.91     .06       0
  405.79      .1       0
Bank Sta=-23.02,25.4
XS Rating Curve= 0 ,0
Exp/Cntr=0.3,0.1

Type RM Length L Ch R = 1 ,5628.286,683.7456,640.7651,395.2486
BEGIN DESCRIPTION:
TWE_03X
END DESCRIPTION:
XS GIS Cut Line= 5
   1477654.59121   1103041.12664   1477525.12238   1103045.57448
   1477462.72375   1102980.51214   1477384.50591   1102895.63976
   1476923.56759   1102741.99377
#Sta/Elev= 30
 -217.16  902.66 -197.33  902.63 -190.45  900.85 -167.22  899.74 -145.02  896.65
 -116.64  887.04   -84.7  871.76  -66.34  869.44  -34.31  869.11  -28.87  868.01
  -23.82  862.96   -8.73  857.99   -1.91   860.4   21.68  862.56   27.62  866.72
   47.93  870.71  164.31  872.16  258.59  871.71  269.62  872.17  311.24  877.06
   324.9  878.06  346.05   881.3  354.66  882.06  370.37  882.55  401.66  890.44
  429.21   895.4  446.78  897.36  471.03  898.48  495.06  899.06  603.82  904.15
#Mann= 8 ,-1,0
 -217.16     .14       0  -23.82     .04       0   21.68     .14       0
  311.24      .1       0  346.05     .06       0  354.66      .1       0
  471.03     .06       0  495.06      .1       0
Bank Sta=-23.82,21.68
XS Rating Curve= 0 ,0
Exp/Cntr=0.3,0.1

Type RM Length L Ch R = 1 ,4987.521,357.0032,369.3859,338.9796
XS GIS Cut Line= 3
    1477544.5794   1102271.62598   1477251.52822   1102449.89928
   1476931.61352   1102650.15092
#Sta/Elev= 30
  -344.5  902.81 -333.25  902.53 -286.33  896.99 -235.43  893.45 -191.15   889.3
 -140.02  881.26  -121.8  877.83 -110.15  874.23  -93.86  871.04  -66.71  869.95
  -42.56  870.33  -39.26   869.8  -26.17  863.87  -23.82  863.71   -8.73  858.74
   -1.91  861.15   21.68  863.31   36.53  862.84   46.46   870.5   51.65  871.32
   62.28  871.23   77.98  870.03  119.53  879.03  156.83  885.88  192.25  891.37
  224.35  894.04  234.45  894.16  275.99  898.43  347.19  901.53  375.94  903.97
#Mann= 4 ,-1,0
  -344.5     .14       0  -23.82     .04       0   21.68     .14       0
  156.83      .1       0
Bank Sta=-23.82,21.68
XS Rating Curve= 0 ,0
Exp/Cntr=0.3,0.1

Type RM Length L Ch R = 1 ,4618.135,531.4022,518.9171,484.8809
XS GIS Cut Line= 4
    1477234.4334   1102027.41667    1476985.3399   1102217.90026
   1476851.02461   1102320.46818   1476836.37205   1102515.83563
#Sta/Elev= 30
 -310.89   917.5 -248.06  909.19 -209.96  901.44 -178.24  894.41 -125.52  881.21
 -107.47  875.86 -100.08  872.38  -94.25  870.99  -76.54  868.27  -66.95  870.54
   -53.6  870.56  -49.96  868.75  -45.59  864.92  -43.28  863.87  -21.65  861.95
  -21.45  859.53   21.83  860.08   21.85  862.11   44.31     870   59.45  870.35
   86.14  874.11    99.6  877.04  126.41  881.23  188.45  884.99  239.06  891.64
  251.72   891.8   272.6  893.76  298.14   896.3  311.03  896.37  367.61  900.08
#Mann= 4 ,-1,0
 -310.89     .14       0  -21.65     .04       0   21.85     .14       0
   272.6      .1       0
Bank Sta=-21.65,21.85
XS Rating Curve= 0 ,0
Exp/Cntr=0.3,0.1

Type RM Length L Ch R = 1 ,4099.218,529.37,545.3509,563.7048
BEGIN DESCRIPTION:
TWE_02X
END DESCRIPTION:
XS GIS Cut Line= 3
   1476797.89042   1101610.62402   1476639.69259   1101842.92717
   1476523.97277   1102030.91634
#Sta/Elev= 30
 -297.03  911.91 -279.76  910.12 -249.81  908.37 -205.17  904.32 -138.05  888.37
 -124.05  883.88  -95.67  872.62  -87.38  869.82  -76.87  869.57  -64.96  870.55
     -52  870.65  -46.58  868.21  -33.64     865   -33.6  858.92  -12.14  859.79
   16.02  860.14   21.83  859.88   26.61  858.99   26.79     864   33.69  865.21
   37.14  868.42   58.04  869.09   79.09  873.68  109.49  884.35  143.04  893.59
  172.49  899.98  180.82  901.31  188.11  903.21  196.55  906.13  204.77  907.82
#Mann= 3 ,-1,0
 -297.03     .14       0  -33.64     .04       0   26.79     .14       0
Bank Sta=-33.64,26.79
XS Rating Curve= 0 ,0
Exp/Cntr=0.3,0.1

Type RM Length L Ch R = 1 ,3553.867,427.0496,461.7459,467.1004
XS GIS Cut Line= 3
   1476452.26115   1101272.59154   1476250.87172   1101470.50886
    1476014.7605   1101697.93996
#Sta/Elev= 30
 -281.37  910.99 -242.31  905.95  -227.1  903.19 -218.66  902.66 -211.42  900.96
 -192.22  897.93 -187.55  897.76 -147.25  890.44 -114.64  882.55  -90.14   875.2
  -81.05  874.26  -72.35  872.25   -55.1   872.7  -45.68  867.79  -33.64  863.58
   -33.6   857.5   16.02  858.72   26.61  857.57   26.79  862.58   29.41   870.3
   30.76  870.56   75.96  869.06  119.11  870.43   133.2  872.88  170.14  880.85
  192.21  884.29   223.9   887.7   260.7   888.7  304.55  889.31  328.82  890.77
#Mann= 4 ,-1,0
 -281.37     .14       0  -33.64     .04       0   26.79     .14       0
   260.7      .1       0
Bank Sta=-33.64,26.79
XS Rating Curve= 0 ,0
Exp/Cntr=0.3,0.1

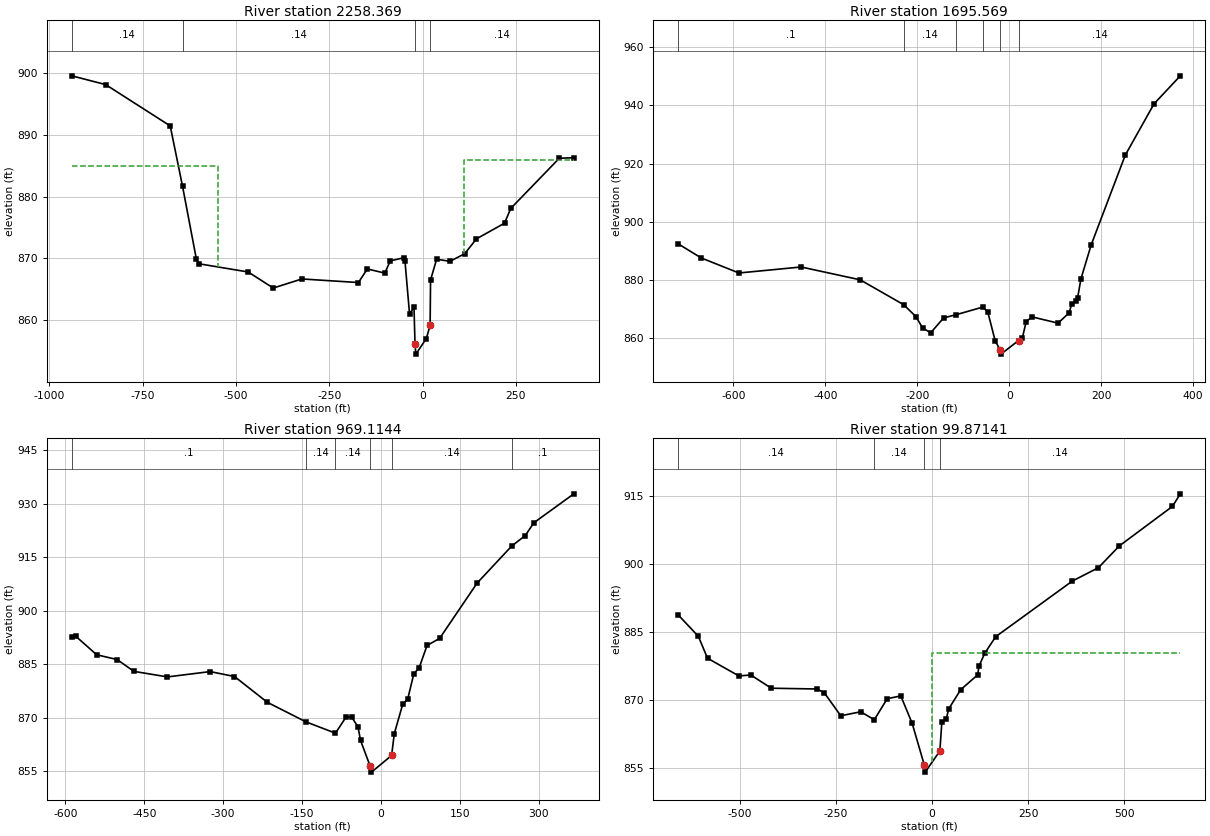
Type RM Length L Ch R = 1 ,2258.369,511.7773,562.8007,577.5682
XS GIS Cut Line= 5
   1476001.42979   1100175.31496   1475837.36713    1100236.5128
   1475276.86581   1100757.43898   1475055.04167   1100963.62238
   1474978.96883   1101032.19423
#Sta/Elev= 30
 -940.29  899.57 -849.44  898.15 -676.45  891.46 -643.46  881.69 -606.41  869.91
  -598.6  869.13 -467.52  867.81 -400.32  865.21 -323.68  866.68 -172.11   866.1
 -148.18   868.3 -101.41  867.63  -86.64  869.61  -49.99  870.12  -47.38  869.63
  -35.09  861.04  -23.14  862.07  -20.35  856.09  -18.12  854.51    9.82  857.02
   20.09  859.18   21.26  866.52   37.53  869.88   73.24  869.53  112.98  870.78
  144.18  873.17  219.51  875.71  236.22   878.1  366.34  886.23  405.27  886.31
#Mann= 4 ,-1,0
 -940.29     .14       0 -643.46     .14       0  -20.35     .04       0
   20.09     .14       0
#XS Ineff= 2 , 0
         -549.72  884.97  110.13          885.94
Permanent Ineff=
       F       F
Bank Sta=-20.35,20.09
XS Rating Curve= 0 ,0
Exp/Cntr=0.3,0.1

Type RM Length L Ch R = 1 ,1695.569,436.1527,726.4543,810.4975
XS GIS Cut Line= 4
   1475801.82579   1100230.16043   1475487.84678   1100083.03904
   1475150.54364   1100222.98392   1474802.47539   1100375.48786
#Sta/Elev= 30
 -720.01   892.4 -669.98  887.56    -588   882.4 -452.69  884.46 -324.32  880.05
 -229.79  871.51 -203.23  867.42 -188.62  863.55 -171.11  861.82 -142.79  866.96
 -115.59  868.06  -58.11  870.66  -46.88  869.07  -30.74  859.08  -20.35  856.09
  -18.12  854.51   20.09  859.18   28.34  860.01   36.56  865.63   49.21  867.32
  106.02  865.16  129.79  868.65  136.06  871.86  145.44  872.69  148.35  873.66
  155.87  880.42   178.2  892.12   252.1  922.86  314.77  940.54  371.92  950.16
#Mann= 6 ,-1,0
 -720.01      .1       0 -229.79     .14       0 -115.59      .1       0
  -58.11     .14       0  -20.35     .04       0   20.09     .14       0
Bank Sta=-20.35,20.09
XS Rating Curve= 0 ,0
Exp/Cntr=0.3,0.1

Type RM Length L Ch R = 1 ,969.1144,537.2684,525.7077,496.0154
XS GIS Cut Line= 4
    1475817.9731   1100217.60138   1475548.03018   1100066.70472
   1475482.92585   1099790.66306   1475399.59252   1099439.10072
#Sta/Elev= 30
  -587.7  892.68 -580.27  892.87 -540.42  887.66 -501.53  886.31 -469.51  882.99
 -405.88  881.44 -324.65  882.93 -278.45  881.55 -215.98   874.3 -142.62  868.82
  -86.54  865.64  -66.38  870.19  -55.87  870.15  -43.79  867.45  -38.96  863.63
  -20.35  856.29  -18.12  854.71   20.09  859.38   25.29  865.54   41.38  873.82
    50.8  875.25   62.35  882.32   72.56  884.02   87.45  890.26  111.37  892.24
   182.7  907.79  248.38  918.17  274.15  921.12  290.56  924.72  366.47  932.83
#Mann= 6 ,-1,0
  -587.7      .1       0 -142.62     .14       0  -86.54     .14       0
  -20.35     .04       0   20.09     .14       0  248.38      .1       0
Bank Sta=-20.35,20.09
XS Rating Curve= 0 ,0
Exp/Cntr=0.3,0.1

Type RM Length L Ch R = 1 ,99.87141,68.07822,99.87141,126.4536
BEGIN DESCRIPTION:
Limit of Detailed Study (Just US of SC Hwy 267)
END DESCRIPTION:
XS GIS Cut Line= 4
   1476792.64895   1099783.43012   1476415.20997   1099593.88091
   1476203.08858   1099484.80709    1475630.5397   1099186.64173
#Sta/Elev= 30
 -660.61  888.75 -608.23  884.02 -584.41  879.18 -502.89  875.27 -471.58  875.47
 -418.43  872.55 -299.16  872.38  -280.3  871.51 -237.71  866.46 -186.06  867.34
 -150.34865.5909  -116.9  870.23  -81.53  870.85  -52.07  864.83  -20.35  855.58
  -18.12     854   20.09  858.67    25.3  865.01   36.68  865.71    43.2  867.99
   74.37  872.23  118.48   875.5  121.99  877.44  137.07  880.31  165.54  883.95
   364.6  896.23  432.69   899.2  487.21  904.02  625.42  912.76  645.81  915.53
#Mann= 4 ,-1,0
 -660.61     .14       0 -150.34     .14       0  -20.35     .04       0
   20.09     .14       0
#XS Ineff= 2 , 0
       0    -108   880.3               0
Permanent Ineff=
       F       F
Bank Sta=-20.35,20.09
XS Rating Curve= 0 ,0
Exp/Cntr=0.5,0.3
LCMann Table=0

--- 12mile_Combined.g03 (geometry) ---

Geom Title=Unrestricted
Program Version=6.10

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
River Reach=Twelvemile Crk  ,Reach1

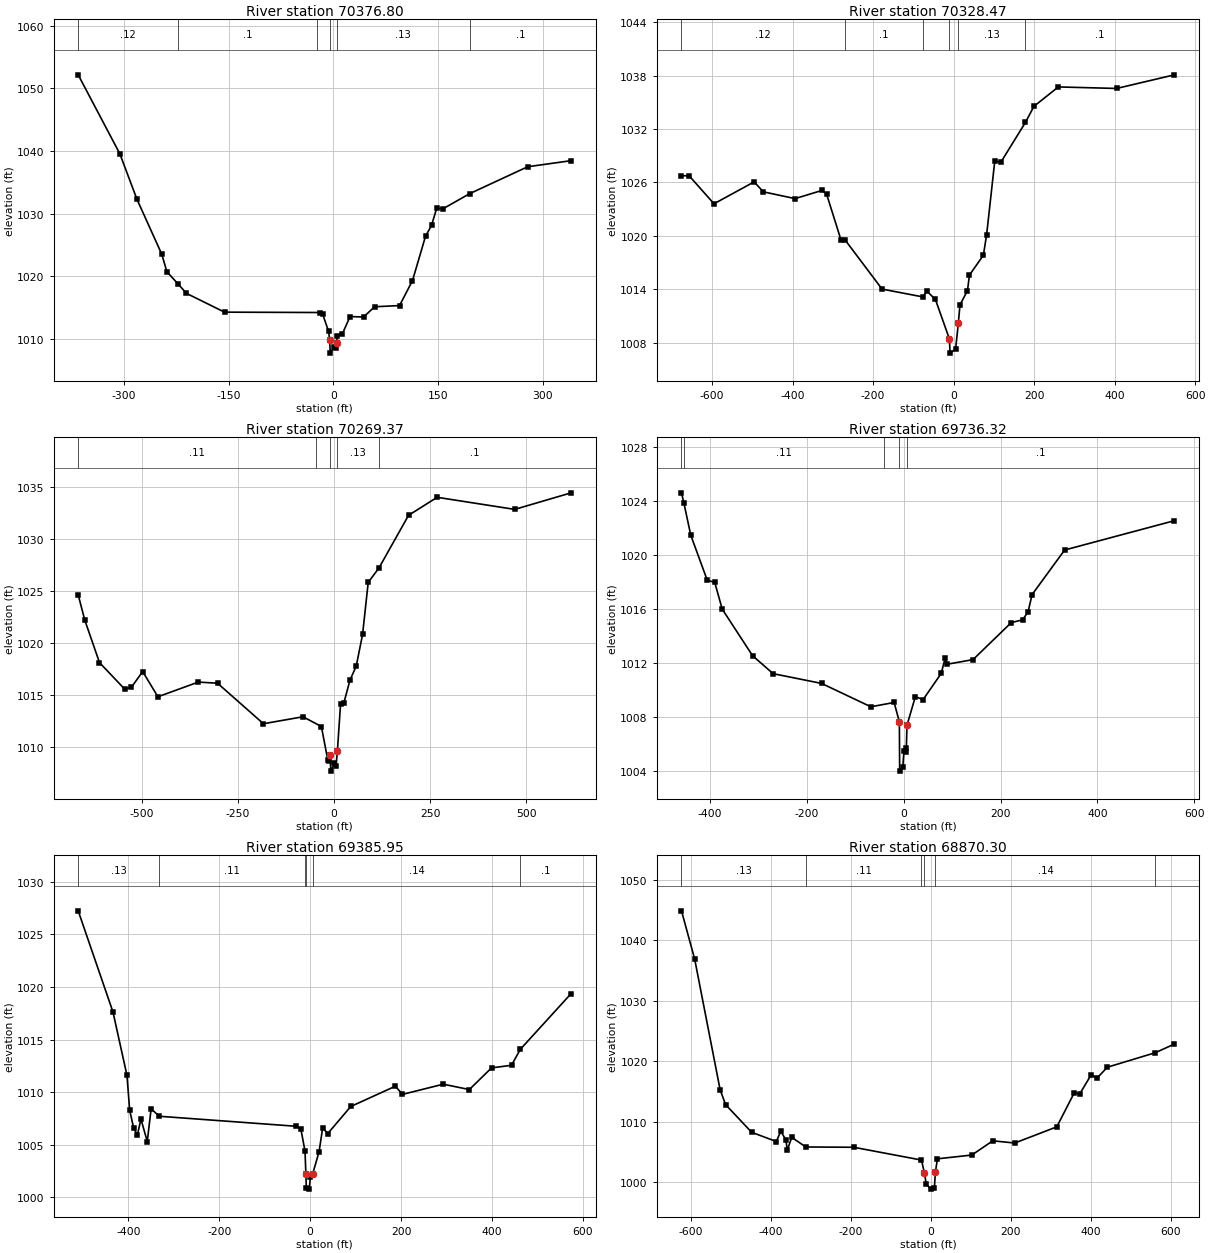
Type RM Length L Ch R = 1 ,70376.80,96.50882,48.3321,38.07024
BEGIN DESCRIPTION:
TWE_39USX
END DESCRIPTION:
XS GIS Cut Line= 5
   1496091.77723   1144119.63615   1495867.47835    1144060.1706
   1495738.18734   1144028.10171    1495665.0876   1144013.22441
   1495421.00984   1144118.80413
#Sta/Elev= 30
 -365.44 1052.18 -305.77 1039.55 -281.42 1032.32 -245.78 1023.51 -238.46 1020.71
  -221.9 1018.69  -210.4 1017.25 -155.93 1014.25  -19.04 1014.19  -15.27 1013.88
   -6.87 1011.16   -5.45  1009.8   -4.45  1007.7     .91 1008.71    4.13  1008.5
    4.71 1009.39    5.33 1010.36   12.52 1010.71   23.79 1013.55   43.11 1013.47
   58.95 1015.11   94.65  1015.3  113.17 1019.28  131.86 1026.38  140.43 1028.11
  147.92 1030.88  157.35  1030.8  195.09 1033.19  278.13 1037.49  340.35 1038.46
#Mann= 6 ,-1,0
 -365.44     .12       0  -221.9      .1       0-24.1499     .13       0
-5.45001    .045       04.709991     .13       0  195.09      .1       0
Bank Sta=-5.45,4.71
XS Rating Curve= 0 ,0
Exp/Cntr=0.3,0.1

Type RM Length L Ch R = 1 ,70328.47,64.05273,59.09576,61.7731
BEGIN DESCRIPTION:
Log House Rd (TWE_39) - US
END DESCRIPTION:
XS GIS Cut Line= 3
   1496421.06857   1143843.50164   1495734.58333   1143980.87303
   1495183.18602   1144116.22277
#Sta/Elev= 30
-675.955 1026.76-656.733 1026.73-595.203  1023.6-495.472 1026.06-472.637 1024.94
 -393.74 1024.18-327.043  1025.1-315.568  1024.7-279.481  1019.5-269.223 1019.52
-177.711 1014.02 -76.163 1013.14 -66.572  1013.8 -45.157 1012.86 -10.335 1008.41
  -8.732 1006.83   5.023 1007.28  11.794 1010.19  15.841 1012.24  34.561 1013.86
  39.361 1015.59  74.038 1017.83  82.152 1020.15 102.253 1028.37 117.785 1028.29
 178.551 1032.74  199.57 1034.54 260.259 1036.72 404.974 1036.55 548.704 1038.08
#Mann= 6 ,-1,0
-675.955     .12       0-269.223      .1       0 -76.163     .13       0
 -10.335    .045       011.79401     .13       0 178.551      .1       0
#XS Ineff= 2 , 0
Permanent Ineff=
       F       F
Bank Sta=-10.335,11.794
XS Rating Curve= 0 ,0
Skew Angle= 15
Exp/Cntr=0.3,0.1

Type RM Length L Ch R = 1 ,70269.37,376.0072,533.0539,464.8225
BEGIN DESCRIPTION:
Log House Rd (TWE_39) - DS
END DESCRIPTION:
XS GIS Cut Line= 3
    1496398.9334   1143770.58465   1495727.60039   1143922.15157
   1495103.20636   1144057.00722
#Sta/Elev= 30
-665.397 1024.63-648.368 1022.21-609.992 1018.12-544.647 1015.58-527.048 1015.75
-497.713 1017.26-458.081 1014.84-352.959 1016.25-303.059 1016.14 -183.68 1012.25
 -80.751 1012.92 -32.996 1011.98 -16.575  1008.8 -12.538 1008.68 -10.335 1009.28
  -8.732  1007.7    .715 1008.47   5.023 1008.15    8.74 1009.67  16.778 1014.14
  25.616 1014.28  41.255 1016.43  57.579 1017.78  74.058 1020.82   88.73 1025.82
 116.732 1027.21  193.63 1032.26 267.977 1033.99 469.662 1032.83 616.406 1034.42
#Mann= 5 ,-1,0
-665.397     .11       0-46.0549     .13       0 -10.335    .045       0
 8.73999     .13       0 116.732      .1       0
#XS Ineff= 2 , 0
Permanent Ineff=
       F       F
Bank Sta=-10.335,8.74
XS Rating Curve= 0 ,0
Skew Angle= 15
Exp/Cntr=0.3,0.1

Type RM Length L Ch R = 1 ,69736.32,289.2822,350.3647,257.4523
XS GIS Cut Line= 4
   1496409.72703   1143752.26673   1495989.57251   1143563.15518
   1495774.30906   1143458.86352   1495546.87828   1143681.08629
#Sta/Elev= 30
 -458.82 1024.59 -453.93 1023.84  -439.7 1021.46 -405.62 1018.12  -390.2 1017.97
 -374.79 1015.99 -312.05 1012.54 -269.64 1011.21  -169.6 1010.49  -67.79 1008.76
  -19.77 1009.08   -8.92 1007.65   -8.33    1004   -1.84 1004.28     .53 1005.48
    4.65 1005.43    5.51 1005.72    6.78 1007.39   24.07 1009.51   40.04 1009.29
   77.52 1011.23   85.48 1012.35   89.89 1011.91  143.22 1012.25  222.13 1014.99
  245.42 1015.19  256.79 1015.78   265.1 1017.06  332.37 1020.36  559.11 1022.53
#Mann= 5 ,-1,0
 -458.82     .11       0 -453.93     .11       0-40.7099     .13       0
-8.92001    .045       06.779999      .1       0
#XS Ineff= 2 , 0
Permanent Ineff=
       F       F
Bank Sta=-8.92,6.78
XS Rating Curve= 0 ,0
Exp/Cntr=0.3,0.1

Type RM Length L Ch R = 1 ,69385.95,412.9951,515.6531,392.017
BEGIN DESCRIPTION:
TWE_38X
END DESCRIPTION:
XS GIS Cut Line= 4
   1496526.70341   1143251.30709   1496116.98031   1143313.80741
   1496022.39239   1143304.99541   1495448.57612    1143270.4042
#Sta/Elev= 30
 -510.22 1027.25 -433.72 1017.63 -402.95  1011.6 -396.95 1008.28 -388.16 1006.58
 -380.02 1005.94 -372.17 1007.44 -358.29 1005.31 -349.81 1008.41 -331.55 1007.71
  -31.27 1006.76  -20.52 1006.52  -11.27 1004.39   -9.41 1002.22   -8.33 1000.85
   -1.84 1000.78     .53 1001.98    5.51 1002.22   19.68 1004.35   27.51 1006.59
   38.86 1006.07   89.37 1008.64  187.55 1010.57  202.99 1009.79  292.88 1010.76
  350.16 1010.25  398.93 1012.31  442.92 1012.56  462.35 1014.08   574.1 1019.38
#Mann= 6 ,-1,0
 -510.22     .13       0 -331.55     .11       0-11.2699     .14       0
   -9.41     .04       05.509979     .14       0  462.35      .1       0
#XS Ineff= 2 , 0
Permanent Ineff=
       F       F
Bank Sta=-9.41,5.51
XS Rating Curve= 0 ,0
Exp/Cntr=0.3,0.1

Type RM Length L Ch R = 1 ,68870.30,37.21201,44.13676,38.35141
BEGIN DESCRIPTION:
TWE_37USX
END DESCRIPTION:
XS GIS Cut Line= 5
   1496605.63648   1142829.78609   1496012.44554   1142909.22507
   1495987.34022   1142913.22408   1495949.92782   1142918.97867
   1495441.45177   1143181.21161
#Sta/Elev= 30
 -624.06 1044.91 -590.99 1036.89 -527.33 1015.27 -513.55 1012.82 -448.43 1008.25
 -386.77 1006.72 -375.61 1008.41 -362.87 1007.03 -359.26 1005.31 -348.07 1007.41
 -313.08 1005.82 -192.92 1005.77  -23.39 1003.65  -16.28 1001.56  -11.32  999.65
     .04  998.84     8.9  998.99   11.39 1001.64   16.56 1003.86  102.57 1004.48
  155.13 1006.84  209.94 1006.47  315.27 1009.15  359.21 1014.81  372.38 1014.56
  400.66 1017.69  416.89 1017.28  441.87 1019.02  562.18 1021.43  609.81 1022.86
#Mann= 6 ,-1,0
 -624.06     .13       0 -313.08     .11       0  -23.39     .14       0
  -16.28     .05       011.39001     .14       0  562.18      .1       0
#XS Ineff= 2 , 0
Permanent Ineff=
       F       F
Bank Sta=-16.28,11.39
XS Rating Curve= 0 ,0
Exp/Cntr=0.3,0.1

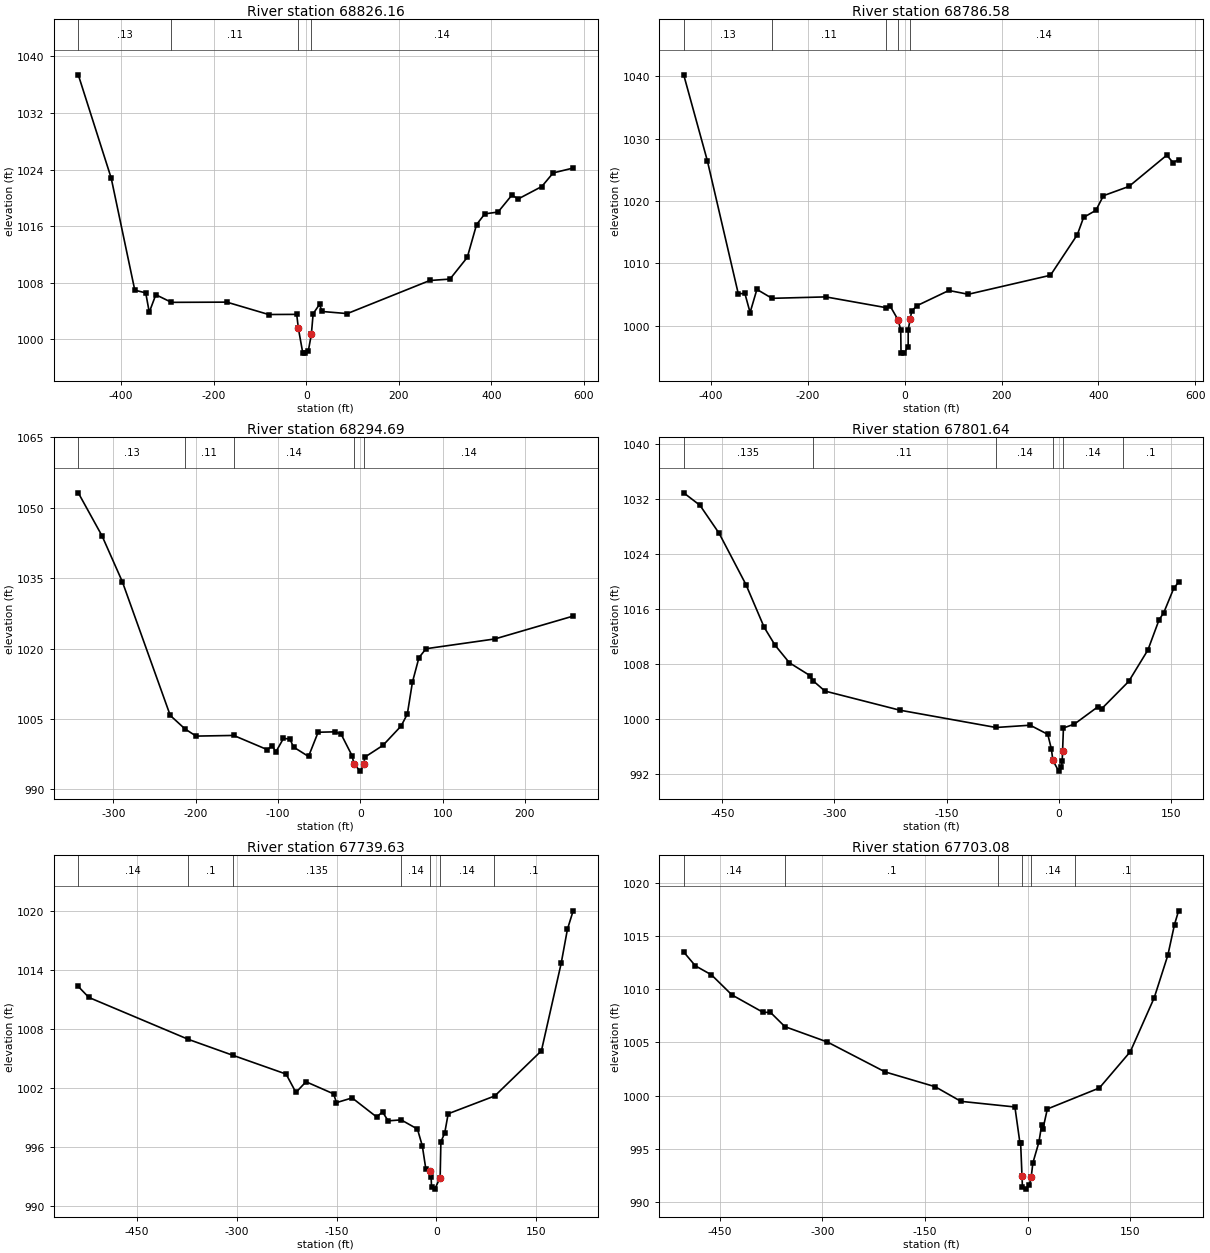
Type RM Length L Ch R = 1 ,68826.16,65.08826,39.57481,37.44172
BEGIN DESCRIPTION:
E. of Midway Rd (US) (TWE_37) - US
END DESCRIPTION:
XS GIS Cut Line= 6
   1496466.19357   1142756.73163   1496075.21063   1142864.33202
   1495983.78248   1142869.49934   1495950.60564   1142876.84711
   1495871.80282   1142945.02034    1495475.3061   1143122.61745
#Sta/Elev= 30
 -492.72 1037.39 -421.55 1022.78 -370.57 1006.94 -346.93 1006.56 -339.29 1003.82
 -325.11  1006.3 -291.34 1005.22 -171.61 1005.25  -81.23  1003.5  -20.62 1003.52
  -16.98 1001.55   -7.64  998.12   -1.79  998.04    4.37   998.3    11.1  1000.7
   14.93 1003.61   28.78 1004.94   34.08 1003.93   88.73 1003.63   267.1 1008.31
  310.74 1008.51  348.14 1011.58  368.21 1016.22  386.01 1017.73  414.64 1017.99
  444.54 1020.38   458.2 1019.84   509.2  1021.6  533.78 1023.52     577 1024.21
#Mann= 4 ,-1,0
 -492.72     .13       0 -291.34     .11       0  -16.98     .05       0
11.10001     .14       0
#XS Ineff= 1 ,-1
           27.72  1003.9
Permanent Ineff=
       F
Bank Sta=-16.98,11.1
XS Rating Curve= 0 ,0
Exp/Cntr=0.3,0.1

Type RM Length L Ch R = 1 ,68786.58,419.7679,491.8906,444.9928
BEGIN DESCRIPTION:
E. of Midway Rd (US) (TWE_37) - DS
END DESCRIPTION:
XS GIS Cut Line= 5
   1496410.20374   1142683.81496   1495972.06332   1142833.04101
   1495896.19291   1142871.40584   1495842.32448   1142920.92126
    1495466.1916   1143061.41962
#Sta/Elev= 30
 -456.67 1040.23 -407.77 1026.43 -343.88 1005.11  -330.3 1005.17 -319.49  1002.1
 -305.43 1005.81 -274.16 1004.38 -163.11 1004.61  -38.25 1002.88  -29.71 1003.09
  -13.58  1000.9   -8.22   999.3   -7.64  995.67   -1.79  995.59    7.14  996.63
    7.21  999.34   11.26 1001.01   14.39 1002.34   25.58 1003.21   91.21 1005.64
  131.26 1005.03  301.16 1008.08  356.67 1014.59  369.59 1017.36  395.13  1018.5
  410.56 1020.84  463.38 1022.33  541.46 1027.34  554.53 1026.15  565.89 1026.63
#Mann= 5 ,-1,0
 -456.67     .13       0 -274.16     .11       0  -38.25     .14       0
-13.5799     .05       011.26001     .14       0
#XS Ineff= 1 ,-1
           34.381002.115
Permanent Ineff=
       F
Bank Sta=-13.58,11.26
XS Rating Curve= 0 ,0
Exp/Cntr=0.3,0.1

Type RM Length L Ch R = 1 ,68294.69,365.8345,493.0584,410.2743
XS GIS Cut Line= 3
   1496244.79626   1142323.44455    1495916.6706   1142406.77789
   1495663.19783   1142476.22277
#Sta/Elev= 30
 -342.78 1053.18 -313.88    1044 -289.24 1034.25 -231.04 1005.77 -213.05 1002.89
 -199.63 1001.37 -153.92 1001.51 -113.07  998.48 -107.03   999.3  -102.7  997.99
  -93.47 1000.88  -85.58 1000.74  -81.25  999.04  -63.02  997.03  -51.34 1002.19
  -31.01 1002.28  -23.47 1001.81   -9.91  997.13   -7.92  995.48    -.15  993.91
    4.56  995.39    5.07  996.85    27.4  999.39   49.52 1003.52   57.07 1006.06
   63.27 1012.86    71.2 1018.09   79.82 1019.98  163.41 1022.06  258.58 1026.93
#Mann= 5 ,-1,0
 -342.78     .13       0 -213.05     .11       0 -153.92     .14       0
-7.92001     .05       04.559998     .14       0
#XS Ineff= 2 , 0
Permanent Ineff=
       F       F
Bank Sta=-7.92,4.56
XS Rating Curve= 0 ,0
Exp/Cntr=0.3,0.1

Type RM Length L Ch R = 1 ,67801.64,77.53092,62.01023,57.99741
BEGIN DESCRIPTION:
TWE_36USX
END DESCRIPTION:
XS GIS Cut Line= 3
    1496275.6122   1142009.64206   1495775.63156   1142048.13386
   1495616.32251   1142065.45801
#Sta/Elev= 30
 -501.53  1032.9 -479.75 1031.08 -454.17 1027.01 -418.34 1019.56 -393.86 1013.32
 -379.23 1010.71 -360.25 1008.18 -332.69 1006.31 -328.83 1005.58  -312.7 1004.06
 -212.69 1001.28  -83.96  998.76  -38.26  999.09  -14.71  997.76   -9.91  995.63
   -7.92  993.98    -.15  992.41    3.54  993.05    4.56  993.89    5.07  995.35
    6.22  998.69   20.81  999.25   52.26 1001.77   57.21 1001.47   93.56 1005.47
  119.18 1010.04  134.07 1014.42  140.36 1015.46  153.65 1018.99  160.18 1019.91
#Mann= 6 ,-1,0
 -501.53    .135       0 -328.83     .11       0-83.9599     .14       0
-7.92001     .04       05.070007     .14       085.93002      .1       0
#XS Ineff= 2 , 0
Permanent Ineff=
       F       F
Bank Sta=-7.92,5.07
XS Rating Curve= 0 ,0
Exp/Cntr=0.3,0.1

Type RM Length L Ch R = 1 ,67739.63,31.78791,36.5445,34.36387
BEGIN DESCRIPTION:
E. of Midway Rd (TWE_36) - US
END DESCRIPTION:
XS GIS Cut Line= 4
    1496301.3189   1141833.89272   1495892.33169    1141956.3353
   1495785.55807   1141987.40879   1495582.21621   1142019.05479
#Sta/Elev= 30
 -538.45 1012.29 -522.61 1011.18 -372.89 1006.92 -305.46 1005.29 -226.08  1003.4
 -211.26 1001.53 -196.19 1002.62 -154.62 1001.39 -150.36  1000.5 -126.79 1000.98
   -89.9  999.04  -81.14  999.56  -72.64  998.65  -53.14  998.75  -28.64  997.82
  -21.29  996.11  -16.03  993.77   -9.58  993.59   -8.08  992.98   -7.44  991.94
   -2.56  991.72    5.51   992.9    6.63  996.53   12.33   997.4   17.59  999.37
   87.66 1001.18  157.73 1005.76  187.41 1014.63  196.88 1018.11  205.46 1019.97
#Mann= 7 ,-1,0
 -538.45     .14       0 -372.89      .1       0 -305.46    .135       0
  -53.14     .14       0-9.58001     .04       0 5.51001     .14       0
86.16998      .1       0
#XS Ineff= 1 ,-1
          205.46    1000
Permanent Ineff=
       F
Bank Sta=-9.58,5.51
XS Rating Curve= 0 ,0
Exp/Cntr=0.3,0.1

Type RM Length L Ch R = 1 ,67703.08,180.2184,202.094,165.4561
BEGIN DESCRIPTION:
E. of Midway Rd (TWE_36) - DS
END DESCRIPTION:
XS GIS Cut Line= 5
   1496274.38615   1141812.34613   1495885.20899   1141926.81004
   1495789.59777   1141951.72277   1495728.99934   1141961.82251
   1495573.46325   1141990.77559
#Sta/Elev= 30
 -503.05 1013.52 -486.03 1012.22 -462.46 1011.37 -432.55 1009.48 -387.01 1007.84
 -376.08 1007.83 -355.02 1006.49 -292.78 1005.04 -208.27 1002.22 -135.18 1000.83
  -97.39  999.45  -18.43  998.92  -11.04  995.51  -10.05  995.51   -8.08  992.44
   -7.44   991.4   -2.56  991.18    2.63  991.57    5.51  992.36    7.81  993.64
   16.69  995.61   20.69  997.21   22.65  996.87   29.01  998.73  105.15 1000.71
  150.42 1004.13   185.4 1009.21   205.3 1013.21  215.08 1016.11  221.05  1017.4
#Mann= 6 ,-1,0
 -503.05     .14       0 -355.02      .1       0-43.3999     .14       0
-8.07998     .04       0 5.51001     .14       069.27002      .1       0
#XS Ineff= 2 , 0
Permanent Ineff=
       F       F
Bank Sta=-8.08,5.51
XS Rating Curve= 0 ,0
Exp/Cntr=0.3,0.1