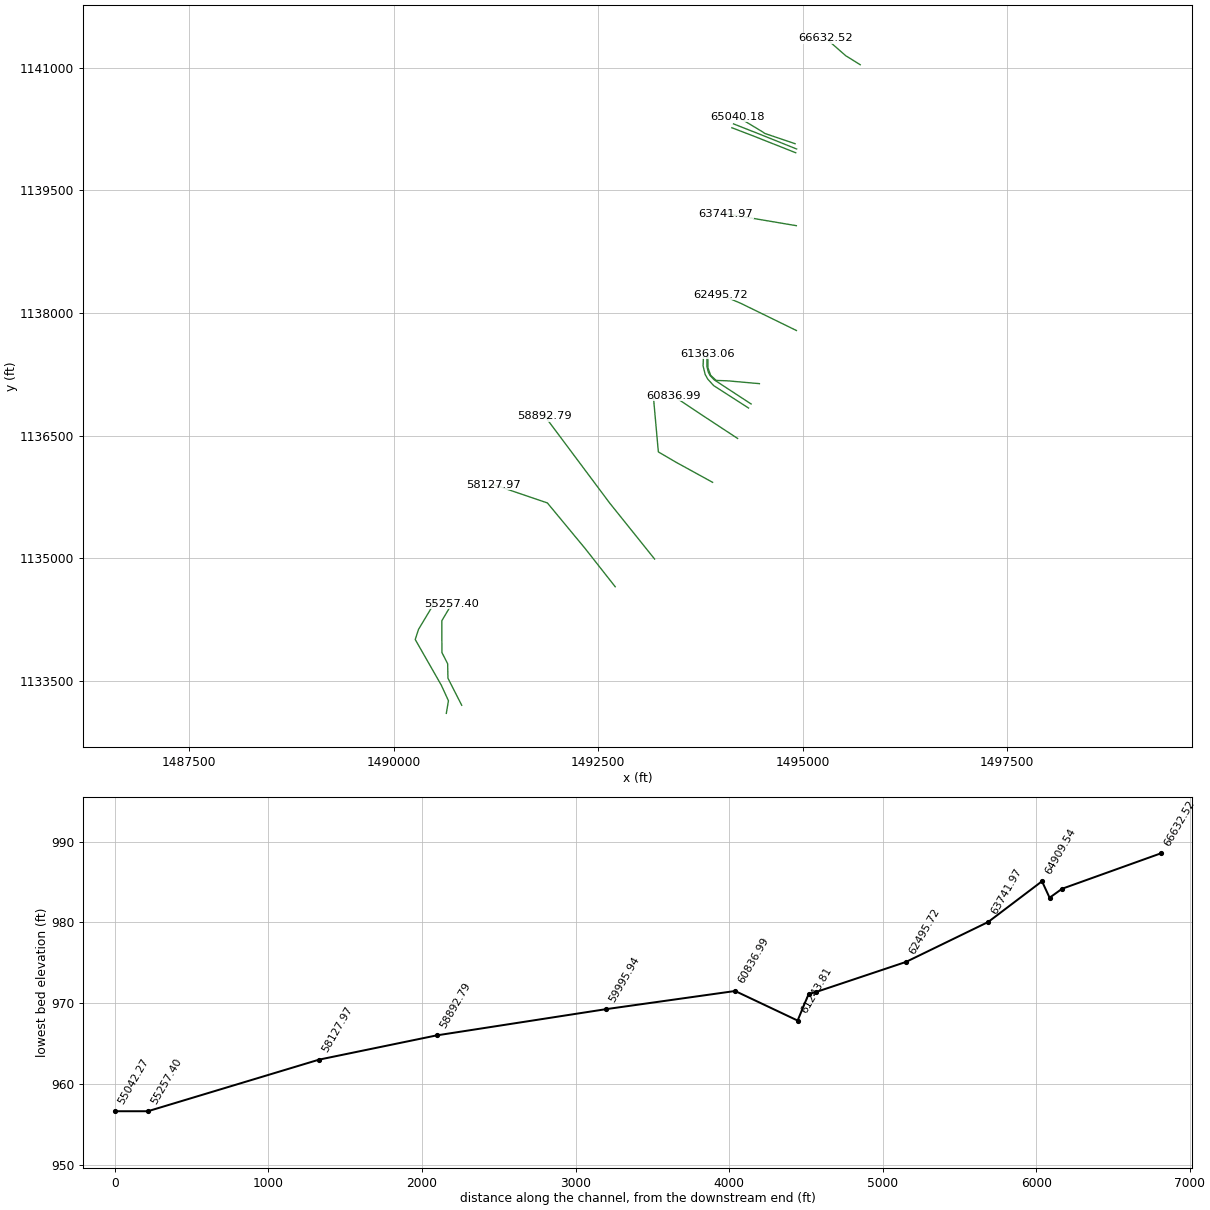
HEC-RAS study 12mile_Combined.prj: 12mile Creek Combined Model

--- 12mile_Combined.g03 (geometry) --- (continued)

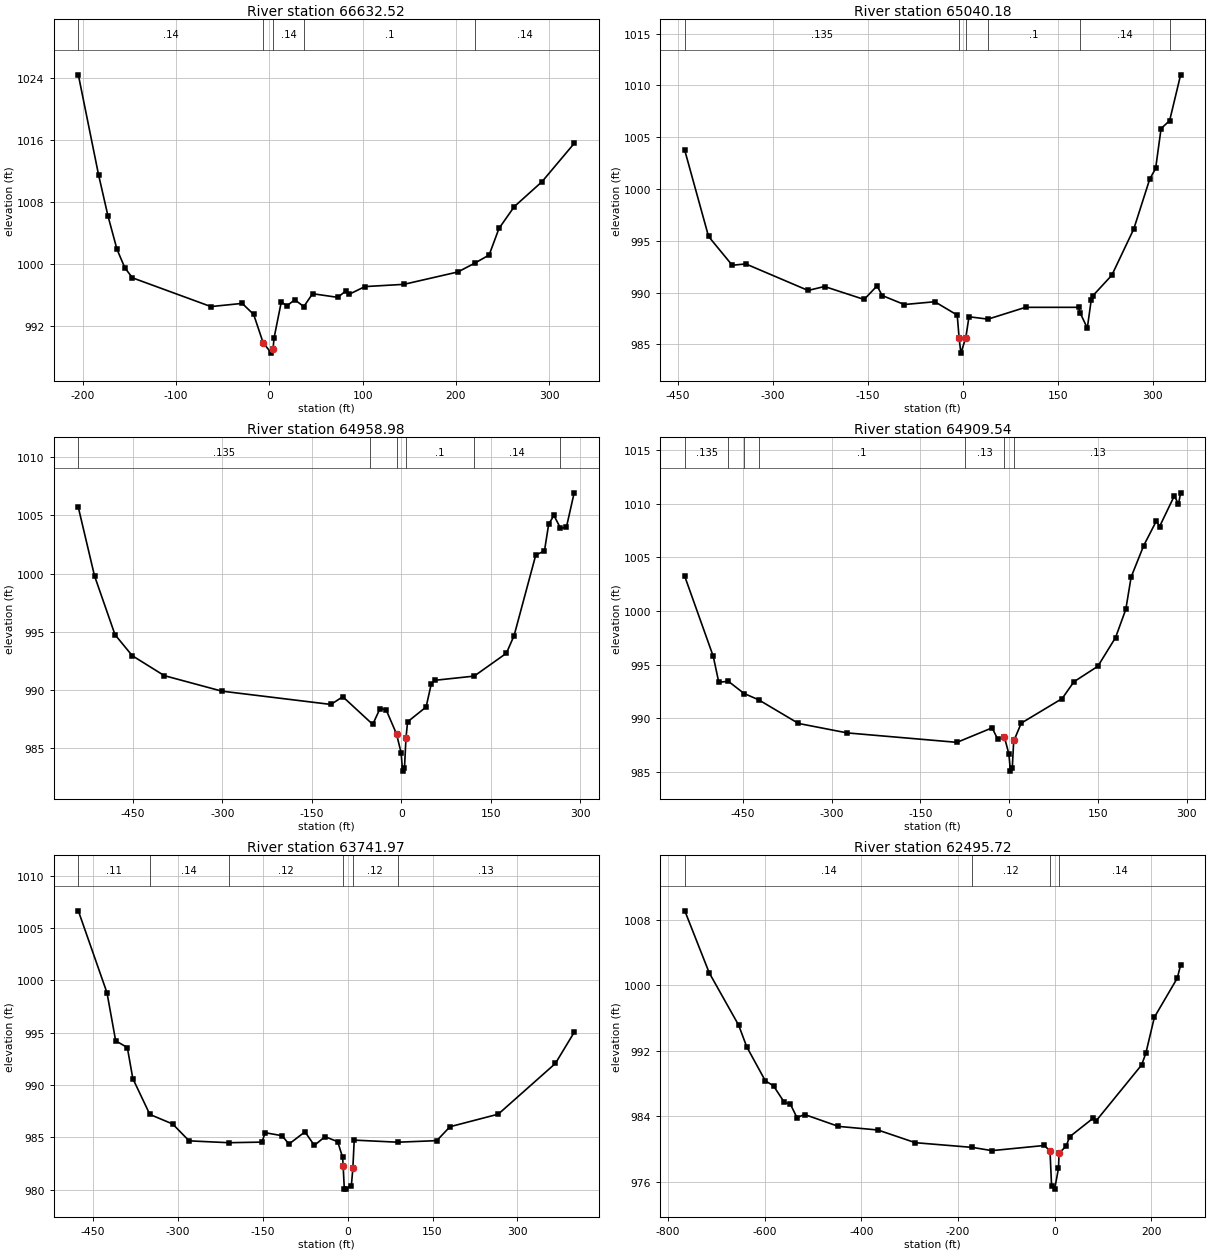
Type RM Length L Ch R = 1 ,66632.52,607.0123,642.0161,582.5013
BEGIN DESCRIPTION:
TWE_35X
END DESCRIPTION:
XS GIS Cut Line= 5
   1495705.55545   1141036.35564    1495595.7372   1141105.04823
   1495544.21752   1141136.68307   1495531.21293   1141143.86713
   1495285.37566      1141359.25
#Sta/Elev= 30
 -204.82 1024.47 -183.14 1011.57 -172.98 1006.22 -163.42 1001.96 -154.94  999.55
 -146.76  998.26  -62.64  994.55  -29.07  994.96   -16.8  993.53   -6.67  989.89
    2.19  988.54    4.01  989.11    5.07   990.5   12.77  995.13   19.04  994.65
   27.19  995.43   36.97  994.55   46.38  996.21   73.38  995.74   81.94  996.56
   85.81  996.15   102.5  997.13  144.28  997.42   202.2  999.02  220.65 1000.18
   235.7 1001.21  246.27 1004.64  262.63 1007.45  292.45 1010.68  326.87 1015.61
#Mann= 5 ,-1,0
 -204.82     .14       0-6.66998     .04       04.009995     .14       0
   36.97      .1       0  220.65     .14       0
#XS Ineff= 2 , 0
Permanent Ineff=
       F       F
Bank Sta=-6.67,4.01
XS Rating Curve= 0 ,0
Exp/Cntr=0.3,0.1

Type RM Length L Ch R = 1 ,65040.18,35.51299,81.20195,61.46384
BEGIN DESCRIPTION:
TWE_34USX
END DESCRIPTION:
XS GIS Cut Line= 4
   1494908.63911   1140071.05282   1494541.28051    1140195.3481
   1494498.83563   1140223.13156   1494204.29757   1140400.56759
#Sta/Elev= 30
 -438.52 1003.72 -401.03  995.42 -363.64  992.64 -342.29  992.77 -244.04  990.21
    -218  990.59 -155.56  989.34 -135.13  990.65 -127.08  989.72  -92.17  988.85
  -44.01  989.12   -8.64  987.83   -5.62  985.59   -2.86  984.16    4.88  985.65
    9.92  987.67   39.94  987.44   99.12  988.58  182.89  988.58  185.38  988.03
  196.63  986.58  202.87  989.31  205.73  989.72  235.33  991.68  269.95  996.14
  295.21 1000.97  304.43 1001.98  313.04 1005.83  326.54  1006.6  343.89 1011.02
#Mann= 6 ,-1,0
 -438.52    .135       0-5.61999     .04       04.880005     .13       0
   39.94      .1       0  185.38     .14       0  326.54      .1       0
#XS Ineff= 2 , 0
Permanent Ineff=
       F       F
Bank Sta=-5.62,4.88
XS Rating Curve= 0 ,0
Exp/Cntr=0.3,0.1

Type RM Length L Ch R = 1 ,64958.98,48.1625,49.4349,49.77205
BEGIN DESCRIPTION:
Tater Hill Mountain Rd (TWE_34) - US
END DESCRIPTION:
XS GIS Cut Line= 3
   1494928.16207   1140005.96654     1494427.646   1140206.32808
   1494156.11417   1140313.08399
#Sta/Elev= 30
 -541.18 1005.67 -514.07   999.8 -479.72  994.75 -450.79  992.95 -397.13  991.24
 -300.71  989.91 -117.99  988.77  -97.96  989.43  -47.82  987.06  -35.63  988.41
  -25.54  988.33   -7.99  986.24    -.26  984.62    2.21  983.05    5.39  983.32
    7.94  985.93   10.58  987.28   41.61  988.55   50.38  990.56    56.2  990.84
  122.18   991.2  176.14  993.16  189.09  994.68  225.34 1001.58  239.97 1001.94
  247.04 1004.24  255.82 1004.98  266.81 1003.89  276.66 1003.95  289.72 1006.92
#Mann= 6 ,-1,0
 -541.18    .135       0-52.2999      .1       0-7.98999     .04       0
7.940002      .1       0  122.18     .14       0  266.81      .1       0
#XS Ineff= 2 , 0
Permanent Ineff=
       F       F
Bank Sta=-7.99,7.94
XS Rating Curve= 0 ,0
Exp/Cntr=0.3,0.1

Type RM Length L Ch R = 1 ,64909.54,244.0514,350.0783,339.4108
BEGIN DESCRIPTION:
Tater Hill Mountain Rd (TWE_34) - DS
END DESCRIPTION:
XS GIS Cut Line= 3
    1494916.5584   1139960.32448    1494408.3061   1140161.45932
   1494136.00066   1140265.89469
#Sta/Elev= 30
 -548.25 1003.22 -500.14  995.78 -490.78  993.36 -474.72  993.46 -448.03  992.32
 -423.28  991.73 -356.03  989.53 -273.79  988.65   -88.1  987.77  -28.72  989.12
   -19.5   988.1   -7.99  988.28    -.26  986.66    2.21  985.09    5.39  985.36
    7.83  987.94    8.73     988   20.54  989.56   89.74  991.85  109.53  993.41
  150.11  994.86  179.98  997.53  197.28 1000.15  206.36 1003.17  227.54 1006.09
  249.09  1008.4  254.35 1007.86  279.38 1010.73   286.4 1009.95     290 1011.01
#Mann= 7 ,-1,0
 -548.25    .135       0 -474.72     .06       0 -448.03     .06       0
 -423.28      .1       0-74.7699     .13       0-7.98999     .04       0
 8.72998     .13       0
#XS Ineff= 2 , 0
Permanent Ineff=
       F       F
Bank Sta=-7.99,8.73
XS Rating Curve= 0 ,0
Exp/Cntr=0.3,0.1

Type RM Length L Ch R = 1 ,63741.97,414.8988,535.5957,451.0252
XS GIS Cut Line= 3
   1494924.26411   1139068.44685   1494457.15322   1139147.25558
   1494060.98097   1139215.58268
#Sta/Elev= 30
 -475.64 1006.63 -425.01   998.8 -409.71  994.22 -389.08  993.57  -379.4  990.61
 -349.35987.1844 -309.01  986.27 -279.99  984.66 -209.88984.4842 -151.29  984.54
 -145.71  985.44 -115.67  985.15 -103.69  984.35  -75.35  985.52  -58.78  984.23
  -39.85  985.06   -17.6  984.58    -8.9   983.1   -7.92  982.27   -5.86  980.06
   -3.59  980.05    6.57  980.38    9.25  982.03   11.61  984.73   88.69984.5318
   157.4  984.68  180.78  986.01  266.03  987.21  366.89  992.05   400.1  995.02
#Mann= 6 ,-1,0
 -475.64     .11       0 -349.35     .14       0 -209.88     .12       0
-7.92001     .04       0    9.25     .12       0   88.69     .13       0
#XS Ineff= 2 , 0
Permanent Ineff=
       F       F
Bank Sta=-7.92,9.25
XS Rating Curve= 0 ,0
Exp/Cntr=0.3,0.1

Type RM Length L Ch R = 1 ,62495.72,535.3537,586.2144,526.637
XS GIS Cut Line= 3
   1494925.29856   1137786.57152   1494243.00558   1138119.90551
   1493998.21325   1138224.07251
#Sta/Elev= 30
 -764.85 1009.08 -714.35 1001.51  -653.5  995.12 -636.71  992.47 -598.27  988.32
 -581.37  987.71  -559.1   985.7 -546.46  985.47 -532.98  983.84 -517.08  984.21
  -447.1  982.76 -365.55  982.32 -288.16  980.77 -170.05980.1938 -129.68   979.8
  -21.24  980.43   -9.61  979.76   -6.34  975.54     .01   975.1    7.93  977.63
    9.21  979.51    23.5  980.32   31.22   981.5   79.59  983.76   85.72  983.43
  179.89  990.26  188.63   991.7   206.3  996.09  253.64 1000.86  260.55 1002.47
#Mann= 4 ,-1,0
 -764.85     .14       0 -170.05     .12       0-9.60998     .04       0
9.210022     .14       0
#XS Ineff= 2 , 0
Permanent Ineff=
       F       F
Bank Sta=-9.61,9.21
XS Rating Curve= 0 ,0
Exp/Cntr=0.3,0.1

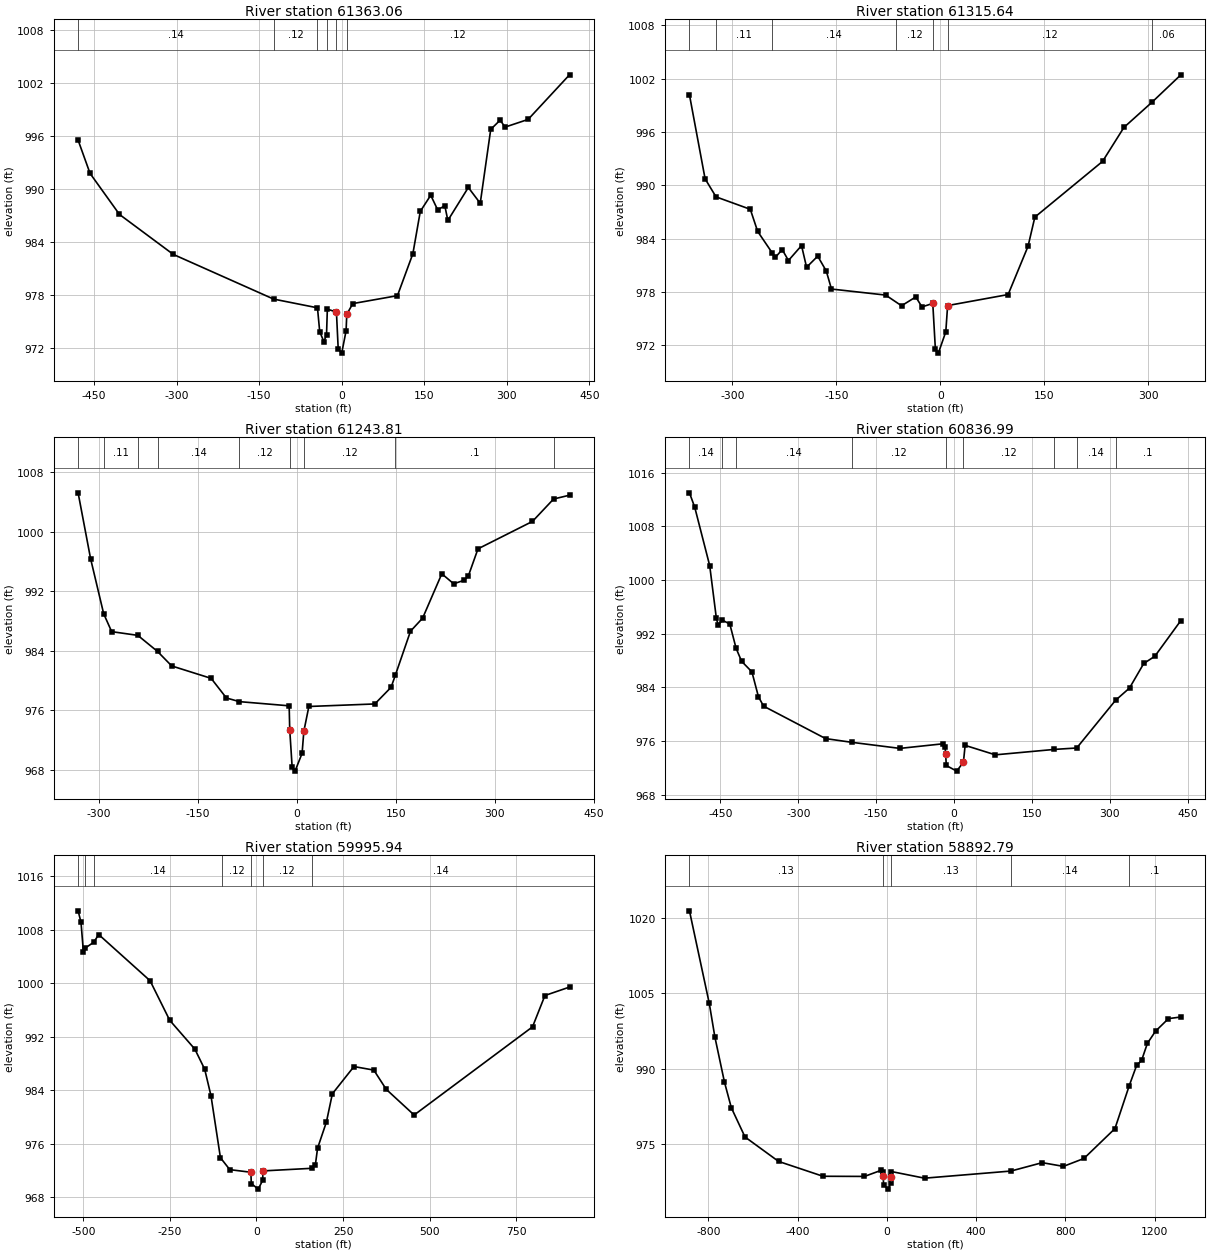
Type RM Length L Ch R = 1 ,61363.06,113.0541,47.42634,15.37912
BEGIN DESCRIPTION:
TWE_32USX
END DESCRIPTION:
XS GIS Cut Line= 6
   1494472.47474   1137136.85072   1494079.67881   1137171.57316
   1493944.05184   1137176.11975   1493876.87697   1137238.33924
   1493843.28904   1137330.29199   1493842.18799   1137503.73556
#Sta/Elev= 30
 -479.03  995.53 -457.36  991.76 -403.83   987.1  -306.1  982.57 -123.74   977.5
  -44.04  976.51     -40  973.81  -32.47  972.68  -27.62  973.43   -26.1  976.36
   -9.61  976.03   -6.34  971.81     .01  971.37    7.93   973.9    9.21  975.78
    20.2  976.99  101.28  977.89  129.32  982.65  142.79  987.45  161.77  989.28
  174.39  987.62  187.34  988.09  192.88  986.42  230.07  990.16  251.72  988.37
  270.79  996.75  287.91   997.8  296.84  997.01  338.71  997.88  413.94 1002.94
#Mann= 6 ,-1,0
 -479.03     .14       0 -123.74     .12       0  -44.04    .045       0
   -26.1     .12       0-9.60998     .04       09.209991     .12       0
Bank Sta=-9.61,9.21
XS Rating Curve= 0 ,0
Exp/Cntr=0.3,0.1

Type RM Length L Ch R = 1 ,61315.64,58.08566,71.82238,65.56407
BEGIN DESCRIPTION:
Ponderosa Rd (TWE_32) - US
END DESCRIPTION:
XS GIS Cut Line= 6
   1494370.79232   1136888.40617   1493919.27428   1137183.82841
   1493869.16831   1137236.13681   1493848.24475   1137276.33169
   1493831.72638   1137341.30413    1493831.7792   1137482.21719
#Sta/Elev= 30
 -361.86 1000.19-339.301  990.74-323.516  988.71 -274.08  987.31-263.472  984.82
-242.854  982.45-238.021   981.9 -228.06  982.78-219.082  981.55-200.193  983.23
-192.927  980.79-176.855  982.04-164.527  980.37-157.023  978.34 -78.827  977.66
 -55.948  976.46 -35.404  977.45 -26.467  976.33 -10.887  976.72  -7.176  971.63
  -2.818  971.13   7.888  973.53  10.526  976.48   97.79  977.72 126.526  983.15
  136.34  986.43 234.015   992.7 264.807  996.52 305.208  999.35 346.935 1002.44
#Mann= 7 ,-1,0
 -361.86     .14       0-323.516     .11       0-242.854     .14       0
-63.4599     .12       0-10.8869     .04       0  10.526     .12       0
 305.208     .06       0
#XS Ineff= 1 ,-1
         346.935   980.5
Permanent Ineff=
       F
Bank Sta=-10.887,10.526
XS Rating Curve= 0 ,0
Skew Angle= 35
Exp/Cntr=0.3,0.1

Type RM Length L Ch R = 1 ,61243.81,387.1822,406.8167,383.6989
BEGIN DESCRIPTION:
Ponderosa Rd (TWE_32) - DS
END DESCRIPTION:
XS GIS Cut Line= 6
   1494339.90584    1136838.5899   1493913.69751   1137112.57776
   1493841.74245    1137191.2897   1493809.85991   1137248.08038
   1493783.95538   1137353.69094   1493788.93701   1137476.23917
#Sta/Elev= 30
 -331.92 1005.25-313.023  996.41 -293.15     989-281.018  986.59-241.363  986.09
-211.472  983.93-189.929  981.98-130.114  980.31-106.908  977.67   -87.1  977.18
 -11.747  976.62 -10.887  973.43  -7.176  968.34  -2.818  967.84   7.888  970.24
  10.526  973.19  18.152  976.53 118.204  976.87 142.901  979.11 149.299  980.72
 172.341  986.65 190.756  988.41 219.844  994.37 237.906  993.02 253.052  993.48
 259.851  994.01 274.719  997.72 357.429 1001.41 389.441 1004.42 413.565 1004.93
#Mann= 9 ,-1,0
 -331.92     .14       0 -293.15     .11       0-241.363     .06       0
-211.472     .14       0   -87.1     .12       0-10.8869     .04       0
  10.526     .12       0 149.299      .1       0 389.441     .14       0
#XS Ineff= 2 , 0
Permanent Ineff=
       F       F
Bank Sta=-10.887,10.526
XS Rating Curve= 0 ,0
Skew Angle= 35
Exp/Cntr=0.3,0.1

Type RM Length L Ch R = 1 ,60836.99,650.8298,841.0577,674.1644
XS GIS Cut Line= 3
   1494205.80315   1136466.79462   1493779.22999   1136747.10105
   1493416.13419   1136988.72146
#Sta/Elev= 30
 -509.67    1013  -499.5 1010.85 -470.69 1002.15  -457.8  994.27 -454.15  993.24
 -446.55  994.02 -431.96  993.44 -419.85  989.82 -409.21  987.88 -389.36   986.3
 -376.77  982.59 -366.88  981.19 -247.38  976.35 -196.38  975.79 -104.25  974.89
  -22.06  975.57   -17.3  975.06  -16.12  974.02  -14.93  972.34    5.12   971.5
   18.08  972.83   21.34  975.34   79.56  973.93  193.47  974.74  236.31  974.95
   311.1  982.06     338  983.89  365.44  987.55  386.81  988.63   436.9  993.95
#Mann= 9 ,-1,0
 -509.67     .14       0 -446.55     .06       0 -419.85     .14       0
 -196.38     .12       0  -16.12     .04       018.07999     .12       0
  193.47     .12       0  236.31     .14       0   311.1      .1       0
#XS Ineff= 2 , 0
Permanent Ineff=
       F       F
Bank Sta=-16.12,18.08
XS Rating Curve= 0 ,0
Exp/Cntr=0.3,0.1

Type RM Length L Ch R = 1 ,59995.94,1016.771,1103.151,955.7007
XS GIS Cut Line= 4
   1493900.16142   1135930.25492   1493450.41831   1136177.14272
   1493236.87631   1136302.14304    1493177.9393   1136958.03281
#Sta/Elev= 30
 -515.04 1010.82 -506.69 1009.11 -499.77  1004.7  -495.1 1005.24  -469.8 1006.13
 -455.61 1007.28 -307.22 1000.38 -250.48  994.47 -177.89  990.16 -149.58  987.17
 -131.42  983.22 -104.04  973.94  -77.03  972.16  -16.12  971.77  -14.93  970.09
    5.12  969.25   18.08  970.58   18.53  971.97  159.77  972.36  170.16   972.9
  176.45  975.36  202.09  979.29  219.16  983.49  281.51  987.56  338.91  987.03
   374.7  984.16  455.34  980.32  797.21  993.49  833.03  998.17  903.98  999.43
#Mann= 7 ,-1,0
 -515.04     .14       0  -495.1     .06       0  -469.8     .14       0
-98.9599     .12       0  -16.12     .04       018.53003     .12       0
  159.77     .14       0
#XS Ineff= 2 , 0
Permanent Ineff=
       F       F
Bank Sta=-16.12,18.53
XS Rating Curve= 0 ,0
Exp/Cntr=0.3,0.1

Type RM Length L Ch R = 1 ,58892.79,585.639,764.8176,605.2095
XS GIS Cut Line= 3
   1493190.86877   1134992.24475   1492643.99278   1135673.66962
   1491849.72047   1136737.04003
#Sta/Elev= 30
 -884.33 1021.41 -795.52 1002.97  -770.5   996.3 -727.55  987.31 -696.76   982.2
 -635.48  976.38 -485.27  971.52 -286.17  968.56  -100.4  968.53  -26.73  969.73
   -16.8  969.48  -16.12  968.52  -14.93  966.84    5.12     966   17.82  967.28
   18.78  968.42   20.36   969.5  168.59  968.18  555.69   969.6   695.7  971.27
  790.66  970.53  882.52   972.1 1021.45  978.05  1085.6  986.61  1118.7  990.65
 1140.68  991.61 1166.86  995.03 1203.34  997.45 1261.21  999.95 1316.67 1000.27
#Mann= 5 ,-1,0
 -884.33     .13       0  -16.12     .04       018.78003     .13       0
  555.69     .14       0  1085.6      .1       0
#XS Ineff= 2 , 0
Permanent Ineff=
       F       F
Bank Sta=-16.12,18.78
XS Rating Curve= 0 ,0
Exp/Cntr=0.3,0.1

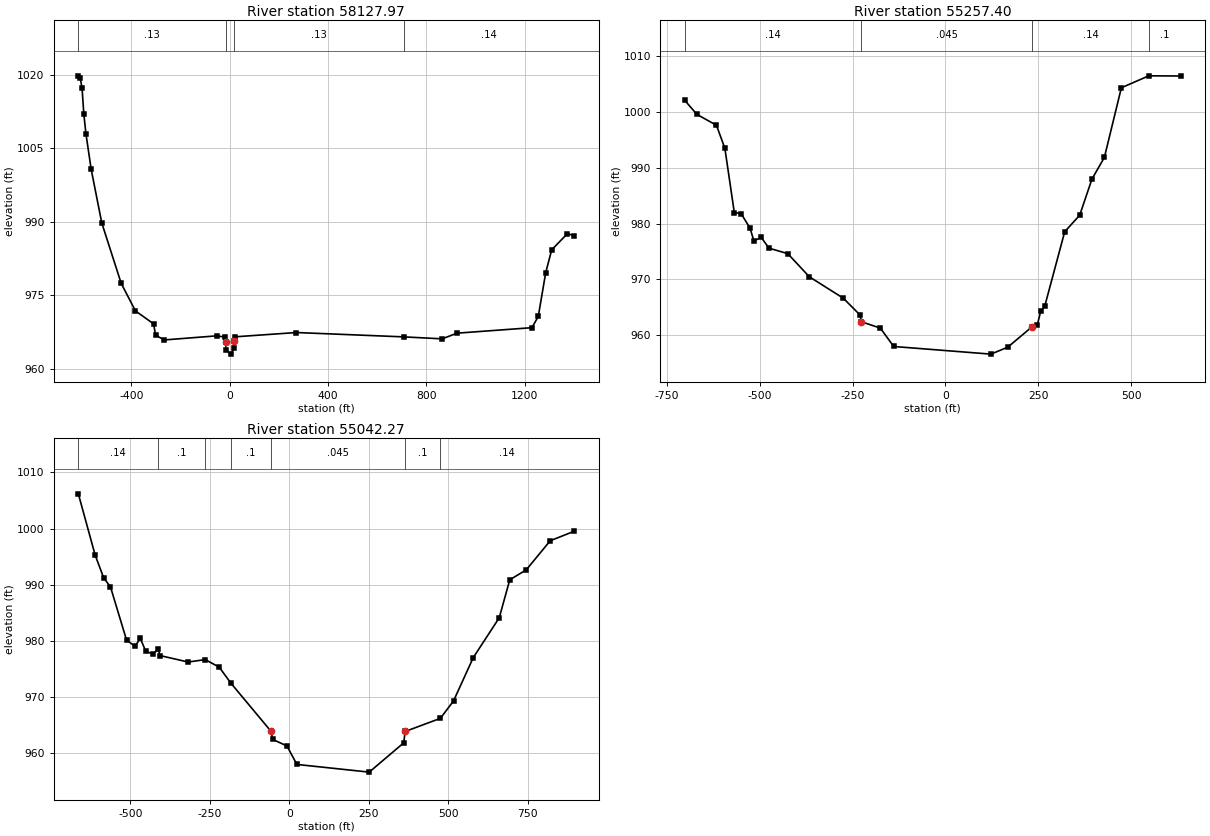
Type RM Length L Ch R = 1 ,58127.97,653.5295,1114.794,595.4461
XS GIS Cut Line= 4
   1492709.09744   1134653.70243    1492340.1729   1135122.45341
   1491880.10269   1135678.00984   1491219.16306   1135902.89304
#Sta/Elev= 30
  -615.5 1019.82 -607.64 1019.29 -600.34 1017.31  -593.2 1012.04 -584.65 1008.02
 -563.25 1000.73 -520.19  989.79 -441.42  977.47 -383.41  971.83 -309.46  969.18
 -301.33  966.85 -265.32   965.9  -53.13  966.73  -18.99  966.48  -16.12  965.52
  -14.93  963.84    5.12     963   17.82  964.28   19.09  965.58   20.34  966.53
  271.28  967.41  708.23  966.52  863.57  966.12  924.56  967.28 1228.79   968.4
 1254.58  970.69 1284.75  979.61 1309.18   984.3  1372.7  987.58 1400.49  987.21
#Mann= 4 ,-1,0
  -615.5     .13       0  -16.12     .04       019.09003     .13       0
  708.23     .14       0
#XS Ineff= 2 , 0
Permanent Ineff=
       F       F
Bank Sta=-16.12,19.09
XS Rating Curve= 0 ,0
Exp/Cntr=0.3,0.1

Type RM Length L Ch R = 1 ,55257.40,187.8023,215.1259,357.8358
BEGIN DESCRIPTION:
TWE_30USX
END DESCRIPTION:
XS GIS Cut Line= 6
   1490832.65846   1133203.58268   1490664.02854   1133534.68504
   1490660.48196   1133711.85991   1490590.27461   1133848.89764
   1490589.26444   1134237.87434   1490712.56529   1134445.36877
#Sta/Elev= 30
 -701.92 1002.12 -669.43  999.62 -616.62  997.66 -593.93  993.51 -568.56     982
 -550.36  981.82 -526.34  979.23 -515.76  976.91 -496.22  977.56 -475.24  975.62
  -424.5  974.63 -366.62  970.49 -275.16  966.65 -230.35  963.66 -226.53  962.42
 -175.28  961.28 -139.19  957.98  122.54  956.61     168  957.86  233.65  961.53
   247.5  961.83  256.66  964.32   267.4  965.17  321.29  978.56   361.7  981.53
  394.69  988.01   428.2   991.9  473.91 1004.39  547.78 1006.53  633.53  1006.5
#Mann= 4 ,-1,0
 -701.92     .14       0 -226.53    .045       0  233.65     .14       0
  547.78      .1       0
Bank Sta=-226.53,233.65
XS Rating Curve= 0 ,0
Exp/Cntr=0.3,0.1

Type RM Length L Ch R = 1 ,55042.27,202.4462,184.575,406.9847
BEGIN DESCRIPTION:
Dam E. of Midway RD (TWE_30) - US
END DESCRIPTION:
XS GIS Cut Line= 6
    1490644.1227   1133104.83136   1490670.16437   1133259.34547
   1490583.35892   1133448.58235   1490263.88944   1134008.10827
   1490304.39633   1134132.39961   1490519.77657   1134490.95932
#Sta/Elev= 30
  -664.1 1006.19  -611.2  995.28 -584.22  991.21 -562.91  989.61 -512.24  980.12
 -485.69  979.05 -468.89  980.42 -452.19  978.18 -430.11  977.64 -412.86  978.46
 -406.47  977.37 -318.23  976.22 -264.67  976.66 -220.53  975.31 -183.53  972.44
  -57.06  963.85  -52.49  962.44 -7.4936  961.28 23.9047  957.98251.6098  956.61
 360.325  961.83  364.59  963.85  475.65  966.19  516.99  969.29  579.03     977
   660.9  984.11  694.12  990.88  745.89  992.64  821.37  997.83  896.76  999.52
#Mann= 7 ,-1,0
  -664.1     .14       0 -412.86      .1       0 -264.67     .14       0
 -183.53      .1       0  -57.06    .045       0  364.59      .1       0
  475.65     .14       0
Bank Sta=-57.06,364.59
XS Rating Curve= 0 ,0
Exp/Cntr=0.3,0.1