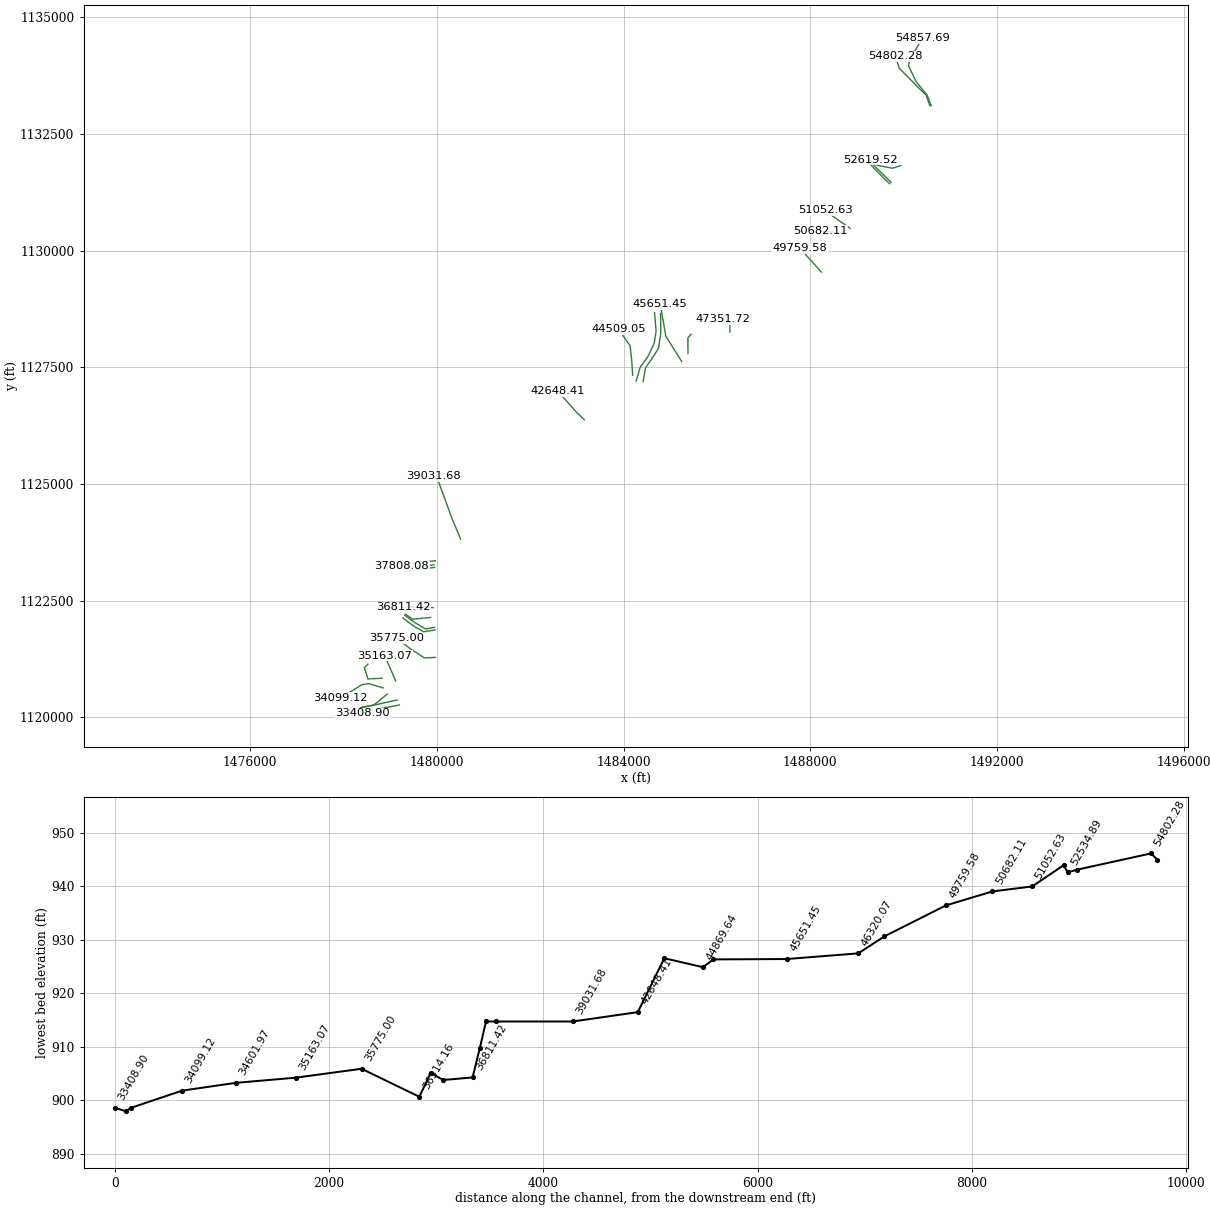
HEC-RAS study 12mile_Combined.prj: 12mile Creek Combined Model

--- 12mile_Combined.g03 (geometry) --- (continued)

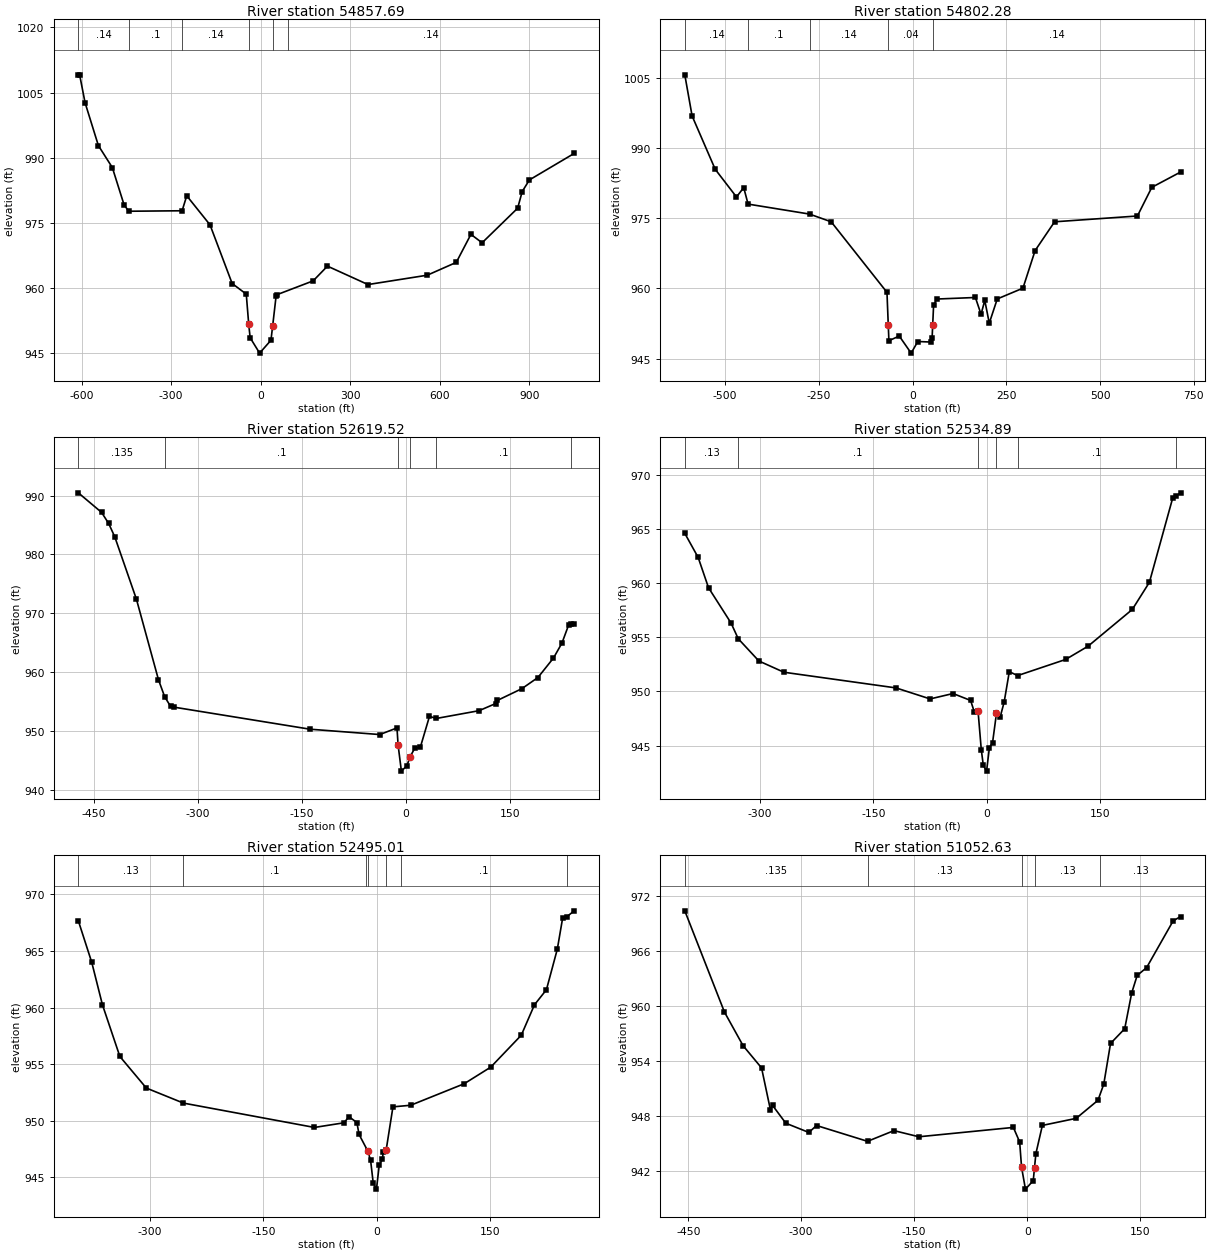
Type RM Length L Ch R = 1 ,54857.69,50.84569,55.41602,71.15096
BEGIN DESCRIPTION:
Dam E. of Midway RD (TWE_30) - DS
END DESCRIPTION:
XS GIS Cut Line= 6
   1490592.03937   1133108.30348   1490503.49738   1133333.99869
   1490269.14436   1133620.46982   1490107.66339        1133959.
   1490126.76083   1134085.73589   1490404.53904   1134547.54265
#Sta/Elev= 30
 -611.27 1008.93  -606.9 1009.08 -588.71 1002.67 -544.08   992.8 -497.29  987.74
 -457.94  979.16 -442.33  977.69 -263.42   977.8 -247.92  981.25 -169.91  974.56
  -95.72  961.06   -48.4  958.62  -40.16  951.66  -35.39  948.58   -3.66  945.04
   34.33     948   40.07   951.3   51.54  958.15   55.29  958.51  175.84  961.67
  223.66  965.06  359.54  960.82  558.15  962.97  655.49  965.92  704.55  972.37
  742.04  970.43  861.17  978.39  876.49  982.23  900.66   984.9  1050.6  990.99
#Mann= 6 ,-1,0
 -611.27     .14       0 -442.33      .1       0 -263.42     .14       0
-40.1599    .045       040.07001     .14       091.90002     .14       0
Bank Sta=-40.16,40.07
XS Rating Curve= 0 ,0
Exp/Cntr=0.3,0.1

Type RM Length L Ch R = 1 ,54802.28,527.0717,693.4466,535.7596
BEGIN DESCRIPTION:
TWE_30DSX
END DESCRIPTION:
XS GIS Cut Line= 6
   1490564.26148   1133103.09514   1490480.92815   1133335.73458
   1490310.07087   1133498.24409   1490226.75427   1133585.52756
   1489909.04528   1133906.70899   1489820.50361   1134158.44554
#Sta/Elev= 30
 -607.24  1005.6 -587.76  996.82 -526.14  985.43 -469.43  979.52 -450.12  981.52
  -438.5     978 -274.69  975.87 -216.89  974.22  -68.13  959.16   -64.6  952.09
  -62.97  948.83  -35.39  949.83   -3.66  946.18   14.12  948.66   48.08  948.55
   52.26  949.45   53.83  952.18   56.22  956.43   65.11  957.73  167.68  958.06
  182.76  954.48   192.7  957.44  204.68  952.58  226.02  957.75  294.47  960.05
  326.94  968.08  378.82  974.22  599.72  975.46  638.16  981.58  714.96  984.85
#Mann= 5 ,-1,0
 -607.24     .14       0  -438.5      .1       0 -274.69     .14       0
-64.5999     .04       053.83002     .14       0
#XS Ineff= 2 , 0
Permanent Ineff=
       F       F
Bank Sta=-64.6,53.83
XS Rating Curve= 0 ,0
Exp/Cntr=0.3,0.1

Type RM Length L Ch R = 1 ,52619.52,161.9004,84.63351,63.53086
BEGIN DESCRIPTION:
TWE_28USX
END DESCRIPTION:
XS GIS Cut Line= 5
   1489938.41207   1131819.97211   1489761.47966   1131763.87139
   1489479.48983   1131817.76739   1489378.52165   1131847.61122
   1489280.30938   1131944.04068
#Sta/Elev= 30
 -472.44  990.46 -438.87  987.13 -428.68  985.25 -419.86  982.98 -388.52  972.34
 -356.74  958.66 -347.82  955.78 -339.28  954.14 -334.91  954.02 -138.03  950.26
  -37.33  949.35  -12.53  950.48  -10.93  947.58   -6.18  943.13    1.74  944.04
    6.37  945.58   13.37  947.07   21.09  947.16   34.36  952.44   44.39  952.09
  105.95  953.41  130.05  954.63  132.29  955.15  167.68  957.15  190.89  959.05
  213.37  962.37  225.55   964.9  235.42  968.05  238.56  968.23  243.19  968.16
#Mann= 6 ,-1,0
 -472.44    .135       0 -347.82      .1       0-10.9299    .045       0
6.369995     .12       044.39001      .1       0  238.56     .06       0
Bank Sta=-10.93,6.37
XS Rating Curve= 0 ,0
Exp/Cntr=0.3,0.1

Type RM Length L Ch R = 1 ,52534.89,49.06389,39.87159,41.53906
BEGIN DESCRIPTION:
SE. of Midway RD (TWE_28) - US
END DESCRIPTION:
XS GIS Cut Line= 5
   1489732.33202   1131463.35663   1489607.83694   1131586.93045
   1489447.63845   1131739.82251   1489351.36909   1131838.56037
    1489265.9603   1131927.27625
#Sta/Elev= 30
-399.155  964.63-381.483   962.4-367.805   959.6-337.999  956.33-328.535  954.88
-301.209  952.82-268.146  951.78-119.992  950.33 -74.854  949.31 -44.639  949.81
 -21.368  949.17 -16.617  948.14 -11.516  948.18  -7.242  944.61  -4.573  943.17
   -.269  942.63   3.447  944.78   7.661  945.27  12.841  947.98  17.762  947.65
  22.962  949.01  29.786  951.83  40.824  951.47 104.192  952.96 133.918  954.19
 192.395  957.59 214.969   960.1 245.931  967.94 249.686  968.06 256.251  968.38
#Mann= 6 ,-1,0
-399.155     .13       0-328.535      .1       0-11.5159    .045       0
  12.841     .12       040.82401      .1       0 249.686     .06       0
#XS Ineff= 2 , 0
Permanent Ineff=
       F       F
Bank Sta=-11.516,12.841
XS Rating Curve= 0 ,0
Skew Angle= 5
Exp/Cntr=0.3,0.1

Type RM Length L Ch R = 1 ,52495.01,266.9324,292.8095,286.3088
BEGIN DESCRIPTION:
SE. of Midway RD (TWE_28) - DS
END DESCRIPTION:
XS GIS Cut Line= 4
   1489706.00197    1131430.4439   1489576.04495    1131552.7021
    1489423.7769   1131709.37828   1489238.64304   1131895.33465
#Sta/Elev= 30
 -395.19  967.67-377.388  963.99-363.312  960.26-340.171  955.68-305.115  952.89
-255.903  951.56 -82.435  949.41 -43.414  949.82  -36.62  950.36  -26.21  949.84
 -23.311  948.79 -11.665  947.31  -8.019  946.49  -4.573   944.5   -.269  943.96
   3.447  946.11   7.661   946.6   8.567  947.22  12.602  947.43  21.568  951.23
  45.038  951.37 115.887  953.27 151.113  954.74 191.558  957.56 209.051  960.25
 224.871  961.58 239.276  965.16 246.439  967.95 251.798  968.02 261.601  968.55
#Mann= 7 ,-1,0
 -395.19     .13       0-255.903      .1       0-14.7139     .12       0
 -11.665    .045       012.60199     .12       031.79901      .1       0
 251.798     .06       0
#XS Ineff= 2 , 0
Permanent Ineff=
       F       F
Bank Sta=-11.665,12.602
XS Rating Curve= 0 ,0
Skew Angle= 5
Exp/Cntr=0.3,0.1

Type RM Length L Ch R = 1 ,51052.63,267.2786,370.5237,365.7625
XS GIS Cut Line= 3
    1488853.0023   1130477.57677   1488484.07808   1130735.82415
   1488316.97703   1130859.52231
#Sta/Elev= 30
 -454.55   970.4  -401.9  959.34 -377.18  955.67 -352.64  953.24 -340.88  948.66
 -338.07  949.15 -320.45   947.2 -289.82  946.19 -279.69  946.95 -211.96945.2222
 -176.86  946.39 -143.77  945.72  -18.37  946.74   -9.99  945.15   -7.49   942.4
   -2.33     940    8.04  940.929.719999  942.36   11.54  943.88   20.15  946.96
      65  947.73   93.92   949.7  101.64  951.46  110.64  955.91  129.46  957.52
   138.7  961.42     146  963.34  158.57   964.2  193.76   969.3  203.69  969.78
#Mann= 5 ,-1,0
 -454.55    .135       0 -211.96     .13       0-7.48999     .04       0
9.720001     .13       097.07001     .13       0
#XS Ineff= 2 , 0
Permanent Ineff=
       F       F
Bank Sta=-7.49,9.719999
XS Rating Curve= 0 ,0
Exp/Cntr=0.3,0.1

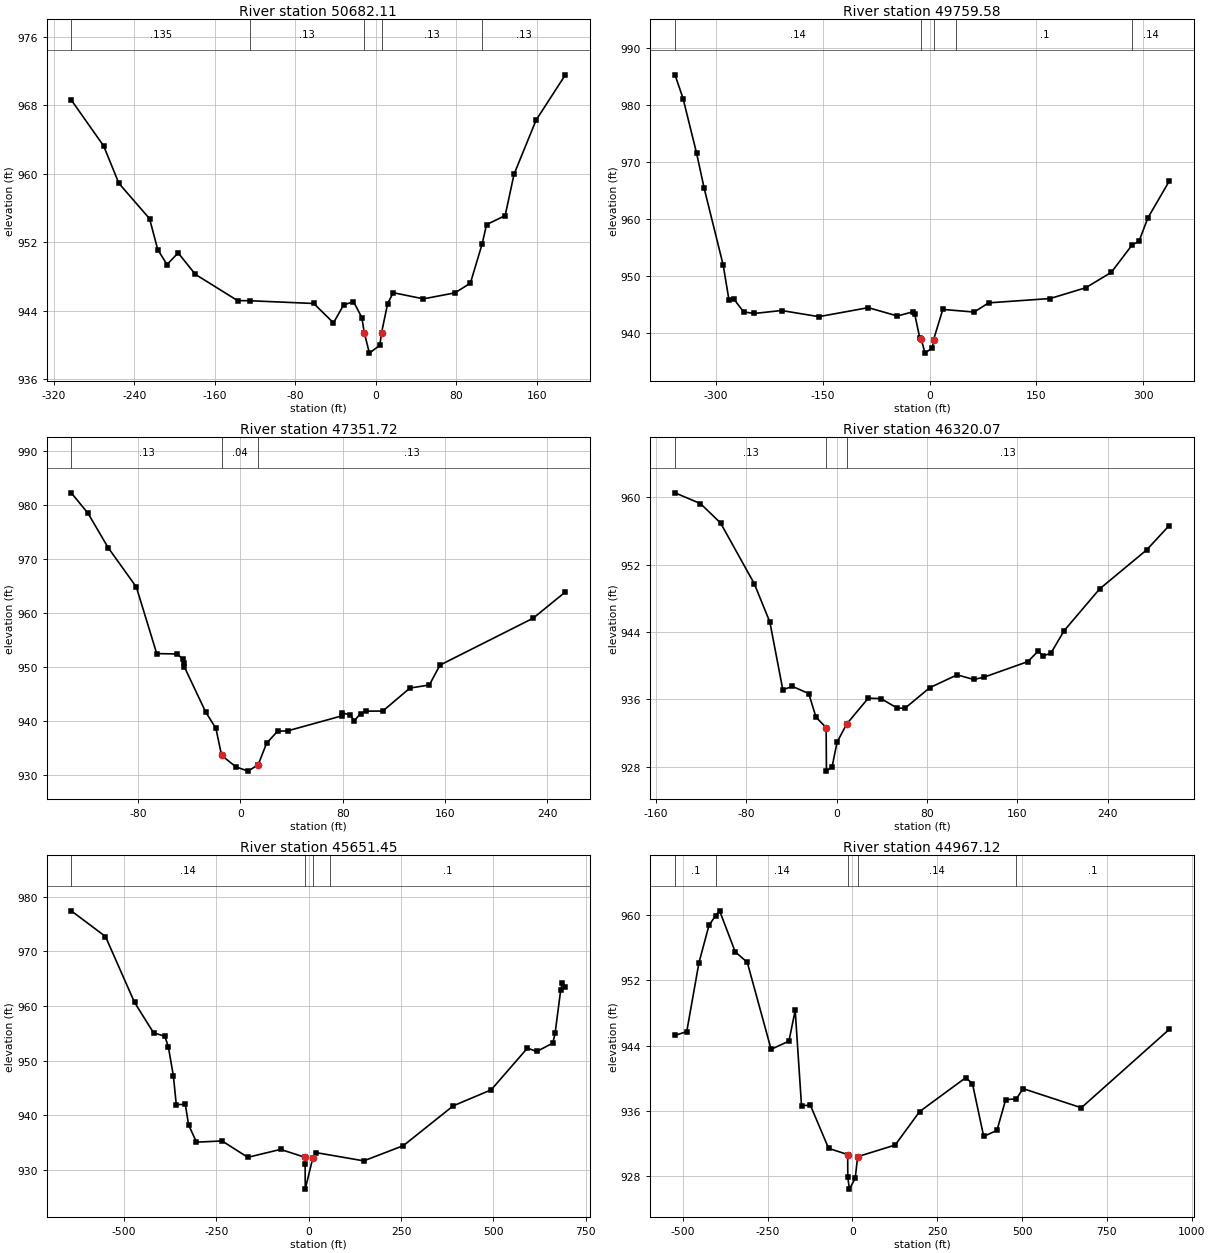
Type RM Length L Ch R = 1 ,50682.11,326.1364,434.0806,224.7923
BEGIN DESCRIPTION:
TWE_27X
END DESCRIPTION:
XS GIS Cut Line= 3
   1488695.59252   1130367.49869   1488395.77428    1130407.1332
   1488208.02362   1130428.22802
#Sta/Elev= 30
 -302.81   968.6 -270.56  963.23 -255.47  958.88 -224.94  954.75 -216.81  951.15
 -207.62   949.4 -196.52  950.76 -179.41  948.26 -137.45   945.2    -125  945.18
  -61.69  944.86  -42.05   942.6  -32.04  944.67  -22.21  945.09  -13.84  943.22
  -11.49  941.47   -6.33  939.07    4.04  939.99    5.72  941.43   11.81  944.85
   17.33  946.12   47.41   945.4   78.71   946.1   94.08  947.23  105.84  951.84
  110.16  954.06  128.65  955.11  137.51  959.94  159.47  966.26  188.55  971.53
#Mann= 5 ,-1,0
 -302.81    .135       0    -125     .13       0-11.4899     .04       0
5.720001     .13       0  105.84     .13       0
#XS Ineff= 2 , 0
Permanent Ineff=
       F       F
Bank Sta=-11.49,5.72
XS Rating Curve= 0 ,0
Exp/Cntr=0.3,0.1

Type RM Length L Ch R = 1 ,49759.58,514.6816,574.8795,496.1618
XS GIS Cut Line= 3
   1488239.93701   1129537.90518   1488001.17782   1129804.57218
   1487777.69619   1130054.39895
#Sta/Elev= 30
 -356.99  985.24 -345.69  981.09 -326.82  971.56 -316.05  965.34 -289.38  951.88
 -281.36  945.83 -274.06  945.88 -260.83  943.69    -246  943.41 -207.57  943.93
 -155.19  942.85  -85.92  944.43  -44.97  942.97  -23.02  943.71  -20.88  943.36
  -13.68  939.14  -11.49  938.86   -6.33  936.46    4.04  937.38    5.72  938.82
   18.66  944.12   62.69  943.66   82.85  945.27  169.22  946.03  219.15  947.92
  255.02  950.62  284.33955.4391  293.79  956.05  306.26  960.15  336.14  966.58
#Mann= 5 ,-1,0
 -356.99     .14       0-11.4899     .04       05.720001     .14       0
37.85999      .1       0  284.33     .14       0
#XS Ineff= 2 , 0
Permanent Ineff=
       F       F
Bank Sta=-11.49,5.72
XS Rating Curve= 0 ,0
Exp/Cntr=0.3,0.1

Type RM Length L Ch R = 1 ,47351.72,223.5139,243.5831,252.1278
BEGIN DESCRIPTION:
TWE_26X
END DESCRIPTION:
XS GIS Cut Line= 4
   1486278.34449   1128257.52034   1486278.29724   1128391.04462
   1486275.74016     1128478.875   1486118.18766   1128528.35433
#Sta/Elev= 30
 -132.37  982.22 -119.24  978.42 -103.55  972.08  -81.43  964.76  -65.51  952.44
  -49.39  952.37  -45.33  951.45  -44.01  950.76   -43.9  949.98  -27.24  941.63
   -19.2  938.58  -14.77  933.59    -3.6  931.46    6.06  930.67   13.93  931.89
   20.38  935.81   29.03  938.07   36.87  938.13   79.22   940.9   79.64  941.45
   85.77   941.1   89.02  939.98   93.93  941.34   98.42  941.78  111.37   941.8
  132.57  946.06  147.72  946.62  156.08  950.31  228.95     959  254.16  963.86
#Mann= 3 ,-1,0
 -132.37     .13       0  -14.77     .04       013.92999     .13       0
#XS Ineff= 2 , 0
Permanent Ineff=
       F       F
Bank Sta=-14.77,13.93
XS Rating Curve= 0 ,0
Exp/Cntr=0.3,0.1

Type RM Length L Ch R = 1 ,46320.07,355.7927,668.618,610.6862
XS GIS Cut Line= 4
   1485380.84941   1127792.95899   1485379.57185   1127937.06726
   1485379.11319    1128128.0292   1485444.48228   1128207.20899
#Sta/Elev= 30
 -143.32  960.53 -120.76  959.25 -102.96  956.95  -73.09  949.74  -59.27  945.18
  -47.81  937.15  -39.37  937.55  -24.83   936.7  -18.44   933.9   -9.43  932.66
   -9.17  927.49   -4.18     928     .28  930.94     8.8  933.09   27.88  936.15
    39.2   936.1   53.54  934.97   60.45  934.96   82.32  937.39  106.58  938.92
  121.29  938.37  130.33  938.64  169.23  940.49  178.52  941.76  182.38  941.17
  189.58  941.47  201.39  944.16  232.91  949.13  274.41  953.74  294.43  956.64
#Mann= 3 ,-1,0
 -143.32     .13       0-9.42999     .04       08.800003     .13       0
#XS Ineff= 2 , 0
Permanent Ineff=
       F       F
Bank Sta=-9.43,8.8
XS Rating Curve= 0 ,0
Exp/Cntr=0.3,0.1

Type RM Length L Ch R = 1 ,45651.45,594.5614,684.3304,641.0182
XS GIS Cut Line= 3
   1485248.56266    1127619.9101    1484906.6145   1128163.62927
   1484787.67585   1128847.52559
#Sta/Elev= 30
    -642  977.44 -549.45  972.73 -470.79  960.65 -419.48  955.09 -388.91  954.45
 -379.49  952.55 -365.67  947.16 -357.98  941.92 -333.47  941.96 -324.59   938.2
 -303.25  935.04 -234.06  935.26 -164.41  932.26     -76  933.71   -9.89  932.27
   -9.43   931.1   -9.17  926.43   11.24  932.12    19.5  933.13  149.23  931.61
  256.22   934.4  391.24   941.7  493.77  944.63  591.71  952.27  617.05  951.66
  660.24  953.19  666.64  954.99  681.75  962.92  686.42   964.3  694.47  963.51
#Mann= 4 ,-1,0
    -642     .14       0-9.89001    .045       011.23999     .14       0
59.15997      .1       0
#XS Ineff= 2 , 0
Permanent Ineff=
       F       F
Bank Sta=-9.89,11.24
XS Rating Curve= 0 ,0
Exp/Cntr=0.3,0.1

Type RM Length L Ch R = 1 ,44967.12,106.6229,97.47809,96.2407
BEGIN DESCRIPTION:
SC Hwy 178 (TWE_25) - US
END DESCRIPTION:
XS GIS Cut Line= 6
   1484418.68406   1127191.89534   1484472.19357   1127488.53675
   1484670.55512    1127777.4416   1484750.20636    1127913.0643
    1484797.5666   1128227.36483   1484793.26115   1128649.30217
#Sta/Elev= 30
-522.704  945.26-488.133  945.71-452.274  954.15-422.392  958.81-402.527  959.98
-391.194  960.56-345.281  955.52-309.741  954.24-239.452  943.54-186.905  944.55
-168.459  948.33-149.881  936.63-123.598  936.66 -69.979  931.37  -13.86  930.61
 -13.409   927.8  -8.664  926.36   8.382  927.69  15.608  930.35  126.22  931.78
   198.2  935.89 333.929  940.05 353.879  939.34 387.059  932.84 426.207  933.58
  451.87  937.36 483.378  937.45 502.999  938.71 674.812  936.36 933.632  945.98
#Mann= 5 ,-1,0
-522.704      .1       0-402.527     .14       0-13.8598    .045       0
15.60797     .14       0 483.378      .1       0
#XS Ineff= 1 ,-1
          866.36  940.56
Permanent Ineff=
       F
Bank Sta=-13.86,15.608
XS Rating Curve= 0 ,0
Skew Angle= 20
Exp/Cntr=0.3,0.1

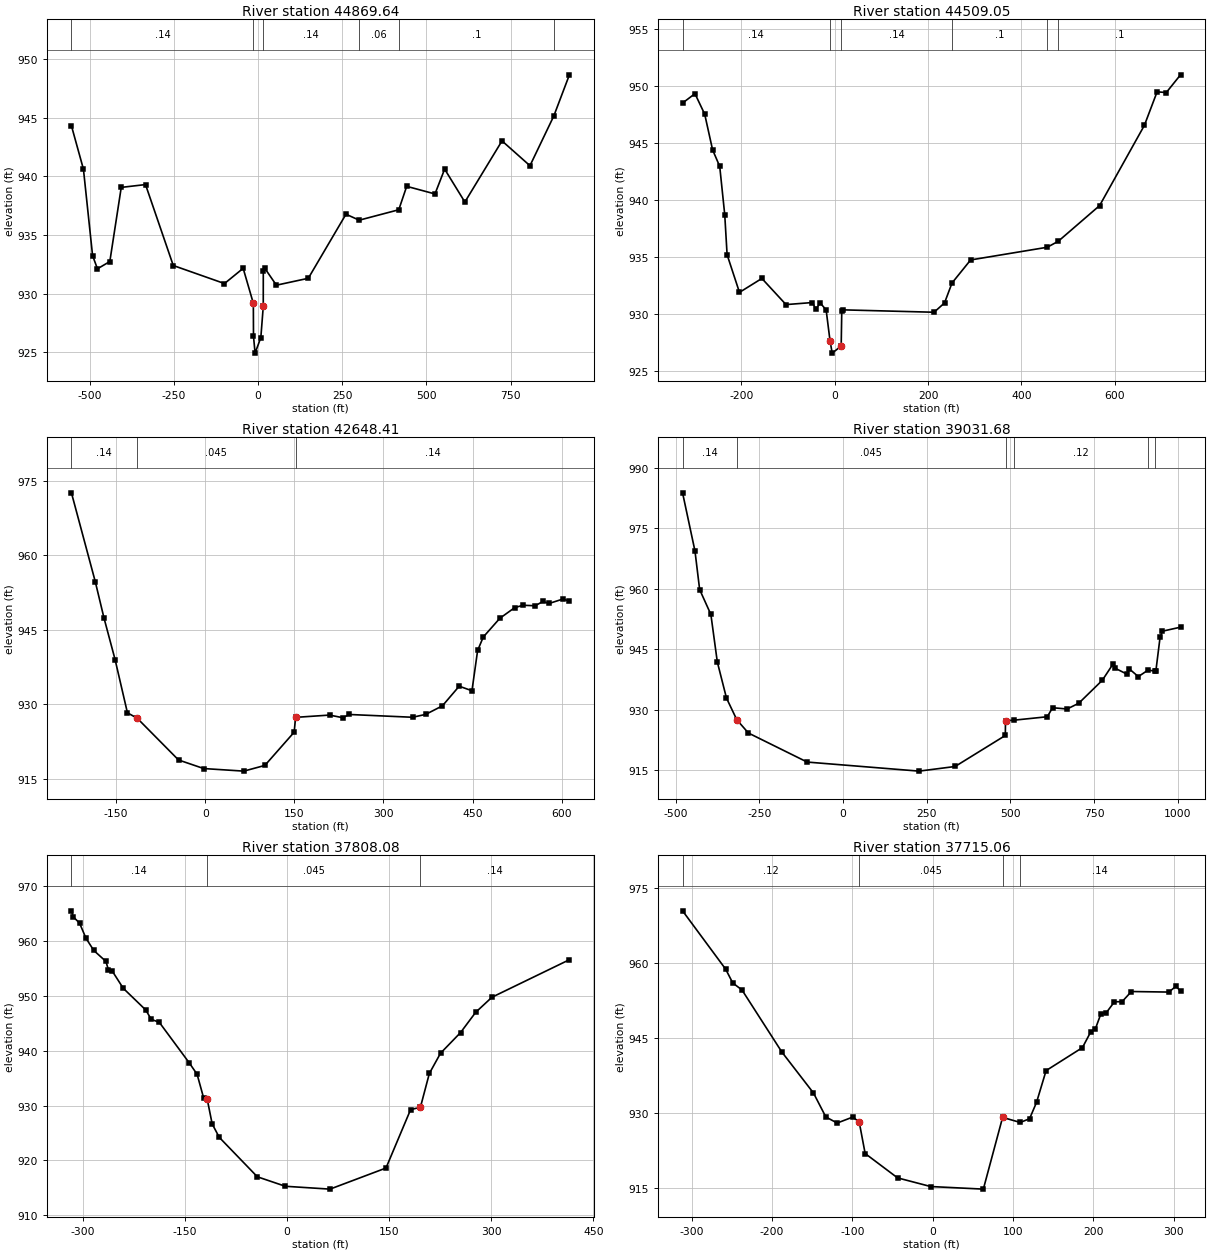
Type RM Length L Ch R = 1 ,44869.64,347.6826,360.594,387.4614
BEGIN DESCRIPTION:
SC Hwy 178 (TWE_25) - DS
END DESCRIPTION:
XS GIS Cut Line= 6
   1484269.63222   1127201.15223   1484356.43832       1127501.5
     1484520.396   1127724.93077   1484657.63845   1128012.09022
   1484697.35728   1128274.56496   1484664.09678    1128670.8294
#Sta/Elev= 30
-553.855  944.32-518.212  940.61-491.121  933.24-476.659  932.11-439.917  932.73
-406.004  939.06-333.939   939.3-251.556  932.39 -99.532  930.85 -44.043  932.15
  -13.86  929.16 -13.409  926.35  -8.664  924.91   8.382  926.24  15.608   928.9
  15.665  931.88  20.504  932.14  54.549  930.71 149.289   931.3 261.141  936.77
  300.41  936.26 417.853  937.15 441.402  939.15 525.354   938.5 554.024  940.62
  614.07  937.81 724.306  943.03 807.337  940.91 878.152  945.16 924.385  948.67
#Mann= 6 ,-1,0
-553.855     .14       0-13.8599    .045       015.60797     .14       0
  300.41     .06       0 417.853      .1       0 878.152     .06       0
#XS Ineff= 1 ,-1
             300   935.4
Permanent Ineff=
       F
Bank Sta=-13.86,15.608
XS Rating Curve= 0 ,0
Skew Angle= 20
Exp/Cntr=0.3,0.1

Type RM Length L Ch R = 1 ,44509.05,237.2591,247.1265,233.693
XS GIS Cut Line= 4
   1484195.95112    1127330.7185   1484175.11778   1127648.42749
   1484141.26345   1127960.92815   1483891.26312   1128315.09547
#Sta/Elev= 30
 -325.68  948.48 -299.13   949.3 -278.32  947.51 -261.44  944.39 -246.11  942.93
 -235.34  938.69 -230.32   935.2 -203.83   931.9 -155.84  933.12 -104.17  930.83
  -47.69  931.01  -40.38  930.44  -30.83  930.97  -18.23  930.36    -9.9  927.65
   -5.26  926.58   13.97   927.2   15.23  930.29   17.12  930.37  212.89  930.16
  235.29  930.98  251.25  932.72  291.13  934.74  455.08  935.85  478.61  936.37
  567.32   939.5  663.24  946.53  690.39  949.46  710.08   949.4  740.55  950.95
#Mann= 6 ,-1,0
 -325.68     .14       0-9.89999     .04       0   13.97     .14       0
  251.25      .1       0  455.08     .06       0  478.61      .1       0
#XS Ineff= 2 , 0
Permanent Ineff=
       F       F
Bank Sta=-9.9,13.97
XS Rating Curve= 0 ,0
Exp/Cntr=0.3,0.1

Type RM Length L Ch R = 1 ,42648.41,585.2552,608.7328,625.9509
XS GIS Cut Line= 3
   1483157.75459   1126375.42159   1482994.55971   1126531.67192
   1482588.30906   1126990.00623
#Sta/Elev= 30
 -225.36  972.56 -185.22  954.66  -170.6  947.37 -151.85  938.96  -131.1  928.25
 -114.65  927.16-45.0831  918.75 -2.6883  917.02 64.8694   916.5100.3117  917.65
 149.659  924.35  152.03  927.33  209.18  927.79  231.65  927.26  242.35  927.91
  349.03  927.35   371.1  927.93  399.21  929.65  427.52  933.61  448.97  932.69
  458.51   940.8  468.07  943.52  495.96  947.29     521  949.44  534.97  949.91
  555.54  949.81  568.21  950.67  579.03  950.28  602.26  951.17  613.04  950.72
#Mann= 3 ,-1,0
 -225.36     .14       0 -114.65    .045       0  152.03     .14       0
#XS Ineff= 2 , 0
Permanent Ineff=
       F       F
Bank Sta=-114.65,152.03
XS Rating Curve= 0 ,0
Exp/Cntr=0.3,0.1

Type RM Length L Ch R = 1 ,39031.68,611.2044,715.2979,1057.36
XS GIS Cut Line= 4
    1480509.8645   1123816.19882   1480325.40256   1124254.56759
   1480039.26969   1125040.27362   1479921.75591   1125170.36811
#Sta/Elev= 30
  -479.1  983.83 -442.03  969.38 -428.07  959.82 -394.54  953.64  -375.3  941.84
 -347.92  932.88  -317.1   927.5  -282.5  924.21    -107     917  227.13  914.75
  334.83   915.9  484.79   923.6  485.34  927.28  510.95   927.4  610.09  928.25
  625.97  930.49   669.3  930.17  704.09   931.6  774.34  937.29  807.23  941.44
  812.52   940.3  848.35  938.81  854.47  940.17  881.96  938.21  911.23  939.84
  930.77  939.57  934.26  939.53  946.86  947.92  953.72  949.48    1008  950.48
#Mann= 6 ,-1,0
  -479.1     .14       0  -317.1    .045       0  485.34     .12       0
  510.95     .12       0  911.23     .06       0  930.77     .14       0
#XS Ineff= 2 , 0
Permanent Ineff=
       F       F
Bank Sta=-317.1,485.34
XS Rating Curve= 0 ,0
Exp/Cntr=0.3,0.1

Type RM Length L Ch R = 1 ,37808.08,94.4441,93.02459,116.6445
BEGIN DESCRIPTION:
TWE_23USX
END DESCRIPTION:
XS GIS Cut Line= 4
   1479966.13451   1123355.31037   1479652.45768   1123315.19062
   1479398.33268   1123286.39469   1479247.14206      1123234.25
#Sta/Elev= 30
 -317.04  965.54 -314.47  964.45 -305.15  963.31 -295.64  960.53 -284.13   958.3
 -266.39  956.31 -262.58  954.73 -257.28  954.59 -240.85   951.4 -207.77  947.44
  -199.7  945.73 -187.95   945.2 -143.68  937.76 -132.31   935.7  -122.7  931.37
 -117.55  931.21 -110.22  926.67  -99.84  924.21  -43.77     917   -2.61  915.27
   62.98  914.75   145.3   918.6  181.46  929.26   195.9  929.69  209.03  935.86
  225.46  939.55  254.95  943.33  277.13  947.02  301.04  949.77  414.88  956.62
#Mann= 3 ,-1,0
 -317.04     .14       0 -117.55    .045       0   195.9     .14       0
Bank Sta=-117.55,195.9
XS Rating Curve= 0 ,0
Exp/Cntr=0.3,0.1

Type RM Length L Ch R = 1 ,37715.06,56.72282,56.84711,65.36195
BEGIN DESCRIPTION:
Weir N.of Gravley Rd (TWE_23) - US
END DESCRIPTION:
XS GIS Cut Line= 3
   1479937.71161   1123266.88353    1479628.2185   1123225.82841
   1479321.88353   1123200.56365
#Sta/Elev= 30
 -311.27  970.38 -257.65  958.72 -248.81  955.96 -237.32  954.56 -187.78  942.17
 -148.36  933.96 -133.01  929.18 -118.94  927.96  -99.42  929.16  -91.48  928.17
  -84.09  921.87  -43.77     917   -2.61  915.27   62.98  914.75   86.94  929.09
  108.87  928.08  120.48  928.82  129.18   932.1  141.05  938.44  186.27  943.04
  196.37  946.11   202.5  946.84  209.33  949.83  216.05  950.04  226.12   952.2
  235.59  952.22  247.21  954.25  293.74  954.14   302.8  955.31  308.31  954.29
#Mann= 4 ,-1,0
 -311.27     .12       0  -91.48    .045       0   86.94     .11       0
  108.87     .14       0
Bank Sta=-91.48,86.94
XS Rating Curve= 0 ,0
Exp/Cntr=0.3,0.1

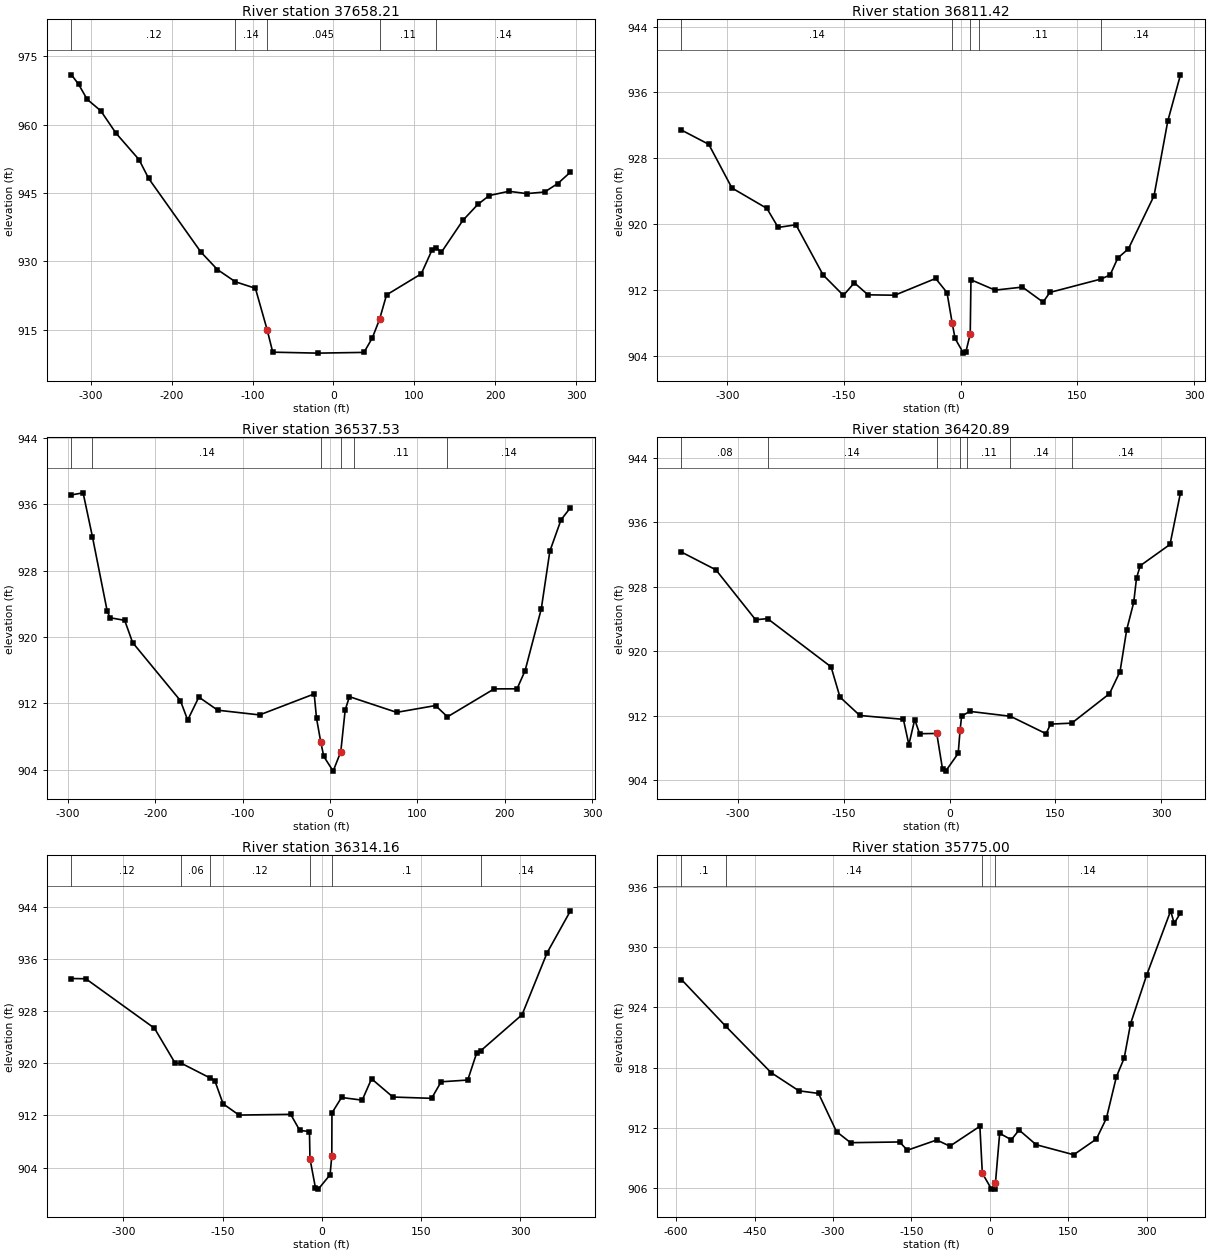
Type RM Length L Ch R = 1 ,37658.21,72.11755,68.54593,67.13055
BEGIN DESCRIPTION:
Weir N.of Gravley Rd (TWE_23) - DS
END DESCRIPTION:
XS GIS Cut Line= 3
   1479950.34383   1123211.09088    1479628.2185   1123168.98294
   1479338.72671   1123130.03314
#Sta/Elev= 30
 -323.93  970.93 -315.26  968.88 -304.53  965.55 -287.73  963.03 -269.03  958.15
  -240.4  952.31 -228.56   948.2 -163.91  932.03 -143.51  928.19 -121.31  925.51
  -96.52  924.08     -82  914.97   -75.1  910.06  -19.64  909.85   37.72  910.01
   47.97  913.16      57  917.28   65.62  922.63  108.53  927.25  121.82  932.47
  127.39  932.94  133.52  932.01  160.02  938.99  178.43  942.48  192.55  944.43
  216.85  945.37  238.94  944.86  261.01  945.21  277.35  947.07  293.03  949.58
#Mann= 5 ,-1,0
 -323.93     .12       0 -121.31     .14       0     -82    .045       0
      57     .11       0  127.39     .14       0
Bank Sta=-82,57
XS Rating Curve= 0 ,0
Exp/Cntr=0.3,0.1

Type RM Length L Ch R = 1 ,36811.42,230.7124,273.8848,256.8954
XS GIS Cut Line= 3
   1479918.38189   1122349.48031   1479561.39304   1122355.99081
   1479277.10466   1122359.24606
#Sta/Elev= 30
 -358.87  931.41 -323.82  929.68 -294.05  924.37 -249.12  921.89 -234.63  919.57
 -211.79   919.9 -176.88   913.8 -150.77  911.31  -136.7  912.84 -119.13  911.38
  -84.77  911.33  -32.19  913.37  -17.61  911.65  -10.93  907.95   -7.23  906.07
    3.52  904.29    6.77  904.48   12.26  906.63   13.19  913.21   44.19  911.95
   79.36  912.32   105.9  910.49  114.64  911.67  180.43   913.3  192.06   913.8
  201.97  915.86  215.55  916.97   248.5  923.42  266.22  932.53  282.48  938.13
#Mann= 5 ,-1,0
 -358.87     .14       0-10.9299    .045       012.26001     .14       0
23.39999     .11       0  180.43     .14       0
#XS Ineff= 2 , 0
Permanent Ineff=
       F       F
Bank Sta=-10.93,12.26
XS Rating Curve= 0 ,0
Exp/Cntr=0.3,0.1

Type RM Length L Ch R = 1 ,36537.53,214.562,116.6427,97.99628
BEGIN DESCRIPTION:
TWE_21USX
END DESCRIPTION:
XS GIS Cut Line= 4
   1479866.29823    1122137.8914   1479571.85728   1122109.14698
   1479478.92782   1122099.91371   1479331.35794   1122206.25098
#Sta/Elev= 30
 -295.97  937.13 -282.68  937.38 -272.03   932.1 -255.04  923.08 -251.77  922.31
 -235.09     922 -226.01  919.32 -171.35  912.32 -162.97  909.97 -150.18  912.74
 -128.64  911.16  -80.69  910.59  -18.18  913.12  -15.48  910.16  -10.75  907.38
   -7.23  905.59    3.52  903.81   12.26  906.15   17.29  911.18   22.15  912.79
   76.22   910.9  120.69  911.72  134.37  910.36  187.82  913.73     214  913.74
  223.19  915.92  241.75  923.38  251.56  930.34  264.37  934.13  275.15  935.59
#Mann= 6 ,-1,0
 -295.97     .08       0 -272.03     .14       0  -10.75    .045       0
12.26001     .14       026.88998     .11       0  134.37     .14       0
Bank Sta=-10.75,12.26
XS Rating Curve= 0 ,0
Exp/Cntr=0.3,0.1

Type RM Length L Ch R = 1 ,36420.89,77.48199,106.7328,110.8034
BEGIN DESCRIPTION:
Gravley Rd (TWE_21) - US
END DESCRIPTION:
XS GIS Cut Line= 5
   1479945.50066   1121926.00558    1479760.8773   1121890.45833
    1479585.5502   1121992.59678   1479453.26837   1122080.78445
   1479308.38845   1122189.66962
#Sta/Elev= 30
-379.338  932.29-330.627  930.09-274.468   923.9-257.535  924.04-167.636  918.06
-155.041  914.31-126.913  912.03 -65.277  911.55 -57.531  908.42 -49.243  911.52
 -42.317  909.77 -18.063   909.8  -9.823  905.35  -5.457  905.13  12.306  907.33
  14.933   910.2  17.145  911.94  28.553  912.54  86.276  911.93  136.65  909.77
 142.957  910.96 173.007  911.08 226.413  914.73 241.346  917.48 250.861  922.69
 260.713  926.05 264.712  929.08 269.918   930.6 312.091  933.24 326.889  939.64
#Mann= 7 ,-1,0
-379.338     .08       0-257.535     .14       0-18.0629     .04       0
14.93301     .14       024.90201     .11       0  86.276     .14       0
 173.007     .14       0
#XS Ineff= 2 , 0
Permanent Ineff=
       F       F
Bank Sta=-18.063,14.933
XS Rating Curve= 0 ,0
Skew Angle= 15
Exp/Cntr=0.3,0.1

Type RM Length L Ch R = 1 ,36314.16,482.54,539.155,447.0775
BEGIN DESCRIPTION:
Gravley Rd (TWE_21) - DS
END DESCRIPTION:
XS GIS Cut Line= 6
   1479960.79856   1121870.21358   1479718.73163   1121830.61909
   1479588.65486   1121904.39829   1479543.20013   1121929.10531
   1479368.80741   1122048.68471    1479274.0351   1122127.02953
#Sta/Elev= 30
-378.604  933.04-356.919     933 -253.15   925.4 -221.68     920-212.591  920.02
-169.269  917.77-162.005  917.37-149.438  913.79-125.368  912.06 -47.214  912.17
 -33.489   909.7 -18.836  909.53 -18.063  905.35  -9.823   900.9  -5.457  900.68
  12.306  902.88  14.933  905.75  15.175  912.39  29.673  914.76  60.892  914.35
  75.033  917.63 107.324  914.83 165.849  914.63 180.213  917.17 220.453  917.44
 233.822  921.56 240.342  921.96 302.625  927.48 340.383  936.98 375.755  943.44
#Mann= 6 ,-1,0
-378.604     .12       0-212.591     .06       0-169.269     .12       0
-18.0629     .04       014.93301      .1       0 240.342     .14       0
#XS Ineff= 2 , 0
Permanent Ineff=
       F       F
Bank Sta=-18.063,14.933
XS Rating Curve= 0 ,0
Skew Angle= 15
Exp/Cntr=0.3,0.1

Type RM Length L Ch R = 1 ,35775.00,702.2434,611.939,557.5637
XS GIS Cut Line= 4
   1479964.17192   1121281.66142   1479733.26837   1121271.24475
   1479429.44882   1121469.16175   1479144.72572   1121689.64829
#Sta/Elev= 30
 -589.61  926.75 -505.34922.1296 -418.39   917.5 -365.26  915.69 -327.67  915.43
 -293.29  911.63  -266.4  910.53 -172.75   910.6 -157.79  909.78 -101.66   910.8
   -76.6  910.18  -19.22  912.16  -14.51  907.49    2.99  905.91    9.86  905.97
   10.62  906.56    18.6  911.46   40.86  910.82   55.76  911.79   88.32  910.33
  160.14  909.33  203.49  910.89  222.65  912.96  241.72  917.08  256.64  918.94
   268.9  922.37  299.51  927.18  345.48  933.59  352.24  932.34  364.24  933.38
#Mann= 4 ,-1,0
 -589.61      .1       0 -505.34     .14       0  -14.51     .04       0
   10.62     .14       0
#XS Ineff= 2 , 0
Permanent Ineff=
       F       F
Bank Sta=-14.51,10.62
XS Rating Curve= 0 ,0
Exp/Cntr=0.3,0.1

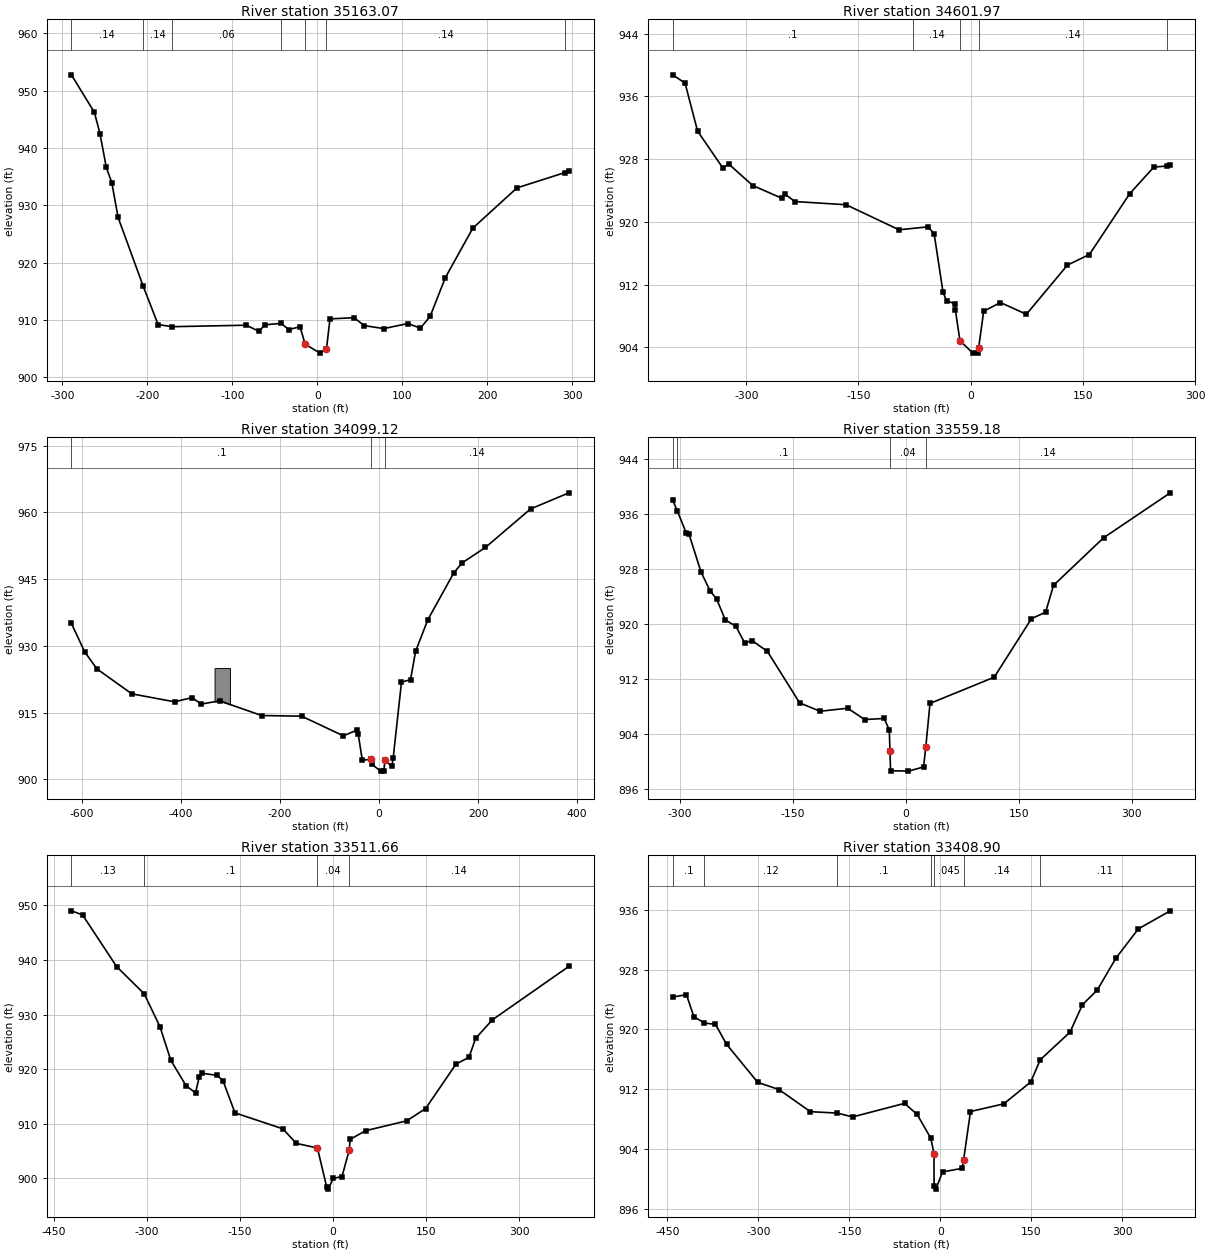
Type RM Length L Ch R = 1 ,35163.07,561.3027,561.0966,515.2526
XS GIS Cut Line= 3
   1479116.94816   1120778.18799   1479005.83661   1121036.86942
   1478882.57251   1121314.64764
#Sta/Elev= 30
 -289.45  952.79 -262.38  946.23  -255.9  942.55  -248.4  936.65 -241.98  934.01
 -234.51  927.91 -205.06915.9555 -187.43  909.23 -171.03908.8605  -83.58  909.12
  -68.78  908.05  -61.79  909.19  -42.58909.4362  -33.61  908.35  -20.41  908.86
  -14.51  905.83    2.99  904.25   10.62   904.9   14.81  910.22    43.1  910.43
   55.17  909.05   78.14  908.53   106.4  909.41  121.24  908.61  132.67  910.66
  150.63  917.44  182.97  926.06  234.86  933.07  291.35935.7462  295.99  935.94
#Mann= 7 ,-1,0
 -289.45     .14       0 -205.06     .14       0 -171.03     .06       0
  -42.58     .14       0  -14.51     .04       0   10.62     .14       0
  291.35      .1       0
#XS Ineff= 2 , 0
Permanent Ineff=
       F       F
Bank Sta=-14.51,10.62
XS Rating Curve= 0 ,0
Exp/Cntr=0.3,0.1

Type RM Length L Ch R = 1 ,34601.97,289.236,502.8473,547.3459
BEGIN DESCRIPTION:
TWE_20X
END DESCRIPTION:
XS GIS Cut Line= 5
   1478823.84186   1120835.94324   1478521.75853   1120820.31824
   1478495.97178   1120910.65584   1478445.07185   1121062.91109
   1478523.19685   1121137.56365
#Sta/Elev= 30
 -398.24  938.75 -381.77  937.69 -365.05  931.58 -331.51  926.91 -323.28  927.37
 -291.28  924.64 -251.56  922.99 -248.45  923.55 -234.73   922.6 -166.45  922.19
  -95.76     919  -56.71  919.38  -48.76  918.47  -36.92  911.02  -32.08  909.92
   -20.8  909.59  -20.53  908.82   -14.3  904.85    2.99  903.28    9.86  903.34
   10.62  903.93   17.39  908.61   39.74  909.73   74.49  908.23  129.34   914.5
  158.73  915.85  212.74  923.62  244.89  926.99   262.5  927.13  266.78  927.22
#Mann= 5 ,-1,0
 -398.24      .1       0-76.7399     .14       0-14.2999     .04       0
   10.62     .14       0   262.5      .1       0
#XS Ineff= 2 , 0
Permanent Ineff=
       F       F
Bank Sta=-14.3,10.62
XS Rating Curve= 0 ,0
Exp/Cntr=0.3,0.1

Type RM Length L Ch R = 1 ,34099.12,423.6966,477.193,491.4279
XS GIS Cut Line= 5
   1478848.58169   1120628.91207   1478540.55774   1120720.89633
   1478388.55709   1120695.70276   1478264.29429   1120615.93602
    1477939.4895   1120416.51181
#Sta/Elev= 30
 -620.98  935.04 -594.28  928.66 -569.64  924.82 -499.08   919.2 -412.66   917.4
 -377.43  918.36 -358.97  916.89 -321.91  917.63 -236.84  914.32 -156.29  914.18
  -72.03  909.76  -44.53  911.04  -42.06   910.2  -33.72  904.25  -15.35  904.52
  -14.51   903.4    2.99  901.82    9.86  901.88   11.71   904.3    25.8  902.88
   28.61   904.8   45.34  921.84   63.55  922.38   73.83  928.77   98.55  935.87
  150.67  946.35  167.57  948.64   214.8  952.12  305.81  960.77  383.36   964.4
#Mann= 3 ,-1,0
 -620.98      .1       0-15.3499     .04       011.71002     .14       0
#XS Ineff= 2 , 0
Permanent Ineff=
       F       F
#Block Obstruct= 1 ,-1
    -332    -301     925
Bank Sta=-15.35,11.71
XS Rating Curve= 0 ,0
Exp/Cntr=0.3,0.1

Type RM Length L Ch R = 1 ,33559.18,63.0086,47.51963,28.5916
BEGIN DESCRIPTION:
Pipeline Crossing
END DESCRIPTION:
XS GIS Cut Line= 4
   1478935.83169   1120495.33924   1478696.24836    1120300.0269
   1478646.76936   1120264.43668   1478362.91503   1120205.40879
#Sta/Elev= 30
 -309.19  938.03 -303.33  936.55  -291.4  933.31  -287.5  933.08 -271.67   927.6
 -259.58  924.83 -251.08   923.7 -239.51  920.64 -225.43  919.69 -213.76  917.27
 -203.96  917.61 -183.64  916.04 -140.84  908.54 -113.78  907.32  -77.12  907.76
  -54.47  906.11   -28.8  906.27  -21.92  904.62  -21.03  901.56  -20.22  898.66
     3.5   898.6   23.59  899.21   26.52  902.16    32.1  908.46  117.29  912.28
  166.65   920.8  185.42  921.74  195.94  925.66  262.34  932.58  350.79  939.13
#Mann= 4 ,-1,0
 -309.19     .14       0 -303.33      .1       0  -21.03     .04       0
26.51999     .14       0
#XS Ineff= 2 , 0
Permanent Ineff=
       F       F
#XS Lid=2
     -26  905.73  904.73      34  908.46  907.46
Bank Sta=-21.03,26.52
XS Rating Curve= 0 ,0
Exp/Cntr=0.3,0.1

Type RM Length L Ch R = 1 ,33511.66,107.9683,102.7682,116.1268
BEGIN DESCRIPTION:
Red Hill Rd (TWE_19) - US
END DESCRIPTION:
XS GIS Cut Line= 4
   1479149.44029   1120369.55676   1478796.78642   1120292.44554
   1478725.84416   1120274.96719   1478365.99311   1120200.94094
#Sta/Elev= 30
 -421.52  949.02 -403.54  948.27  -348.7  938.79 -304.21  933.79 -278.88  927.76
  -261.3  921.58 -236.68  916.92 -221.52  915.63 -215.57   918.6 -211.48  919.24
  -186.6  918.83 -177.27  917.83 -158.06  911.96  -80.87  909.03  -59.35  906.37
  -25.22  905.51  -10.31  898.37    -7.4  897.97    -.01  899.94   14.34  900.27
   25.92   905.1   27.52  907.11   52.71   908.7  118.42  910.49  148.99  912.74
  198.08  920.92  218.85  922.14  229.67  925.63  256.56  929.02  379.92  938.84
#Mann= 4 ,-1,0
 -421.52     .13       0 -304.21      .1       0  -25.22     .04       0
25.92001     .14       0
#XS Ineff= 2 , 0
Permanent Ineff=
       F       F
Bank Sta=-25.22,25.92
XS Rating Curve= 0 ,0
Exp/Cntr=0.3,0.1

Type RM Length L Ch R = 1 ,33408.90,429.2785,439.0403,382.9909
BEGIN DESCRIPTION:
Red Hill Rd (TWE_19) - DS
END DESCRIPTION:
XS GIS Cut Line= 4
   1479196.73491   1120262.62959    1478751.5479   1120177.29364
   1478683.69029    1120155.7021    1478396.8376   1120082.70407
#Sta/Elev= 30
 -441.35  924.32  -418.8  924.65 -406.53  921.71 -389.49  920.85 -370.85  920.67
 -352.57     918 -301.24  912.91 -266.13  911.94 -214.34  908.98 -170.13  908.79
  -144.6  908.28   -59.1  910.09  -38.37  908.62   -15.7  905.42  -10.55  903.38
  -10.31  899.01    -7.4  898.61    3.59  900.91   35.77  901.39   38.33  902.52
   49.71     909  104.67  910.03  148.98  912.95  164.79  915.93  213.77  919.62
   234.4  923.31   258.7  925.25  289.41  929.52  326.65  933.46  379.15  935.87
#Mann= 7 ,-1,0
 -441.35      .1       0 -389.49     .12       0 -170.13      .1       0
   -15.7     .14       0-10.5499    .045       038.32999     .14       0
  164.79     .11       0
#XS Ineff= 2 , 0
Permanent Ineff=
       F       F
Bank Sta=-10.55,38.33
XS Rating Curve= 0 ,0
Exp/Cntr=0.3,0.1