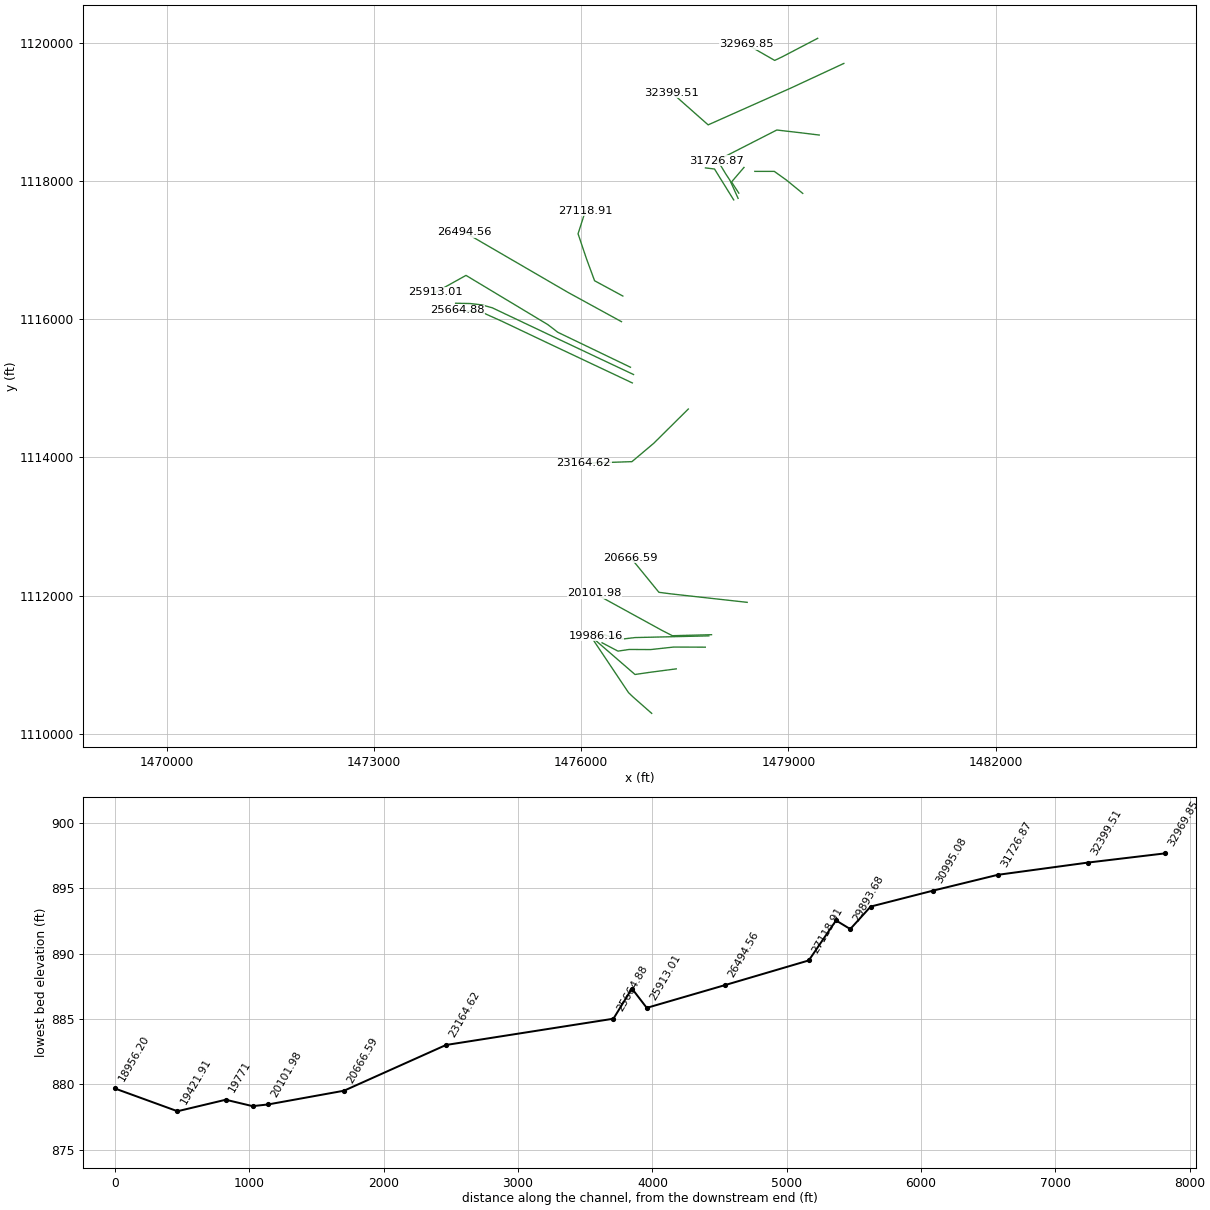
HEC-RAS study 12mile_Combined.prj: 12mile Creek Combined Model

--- 12mile_Combined.g03 (geometry) --- (continued)

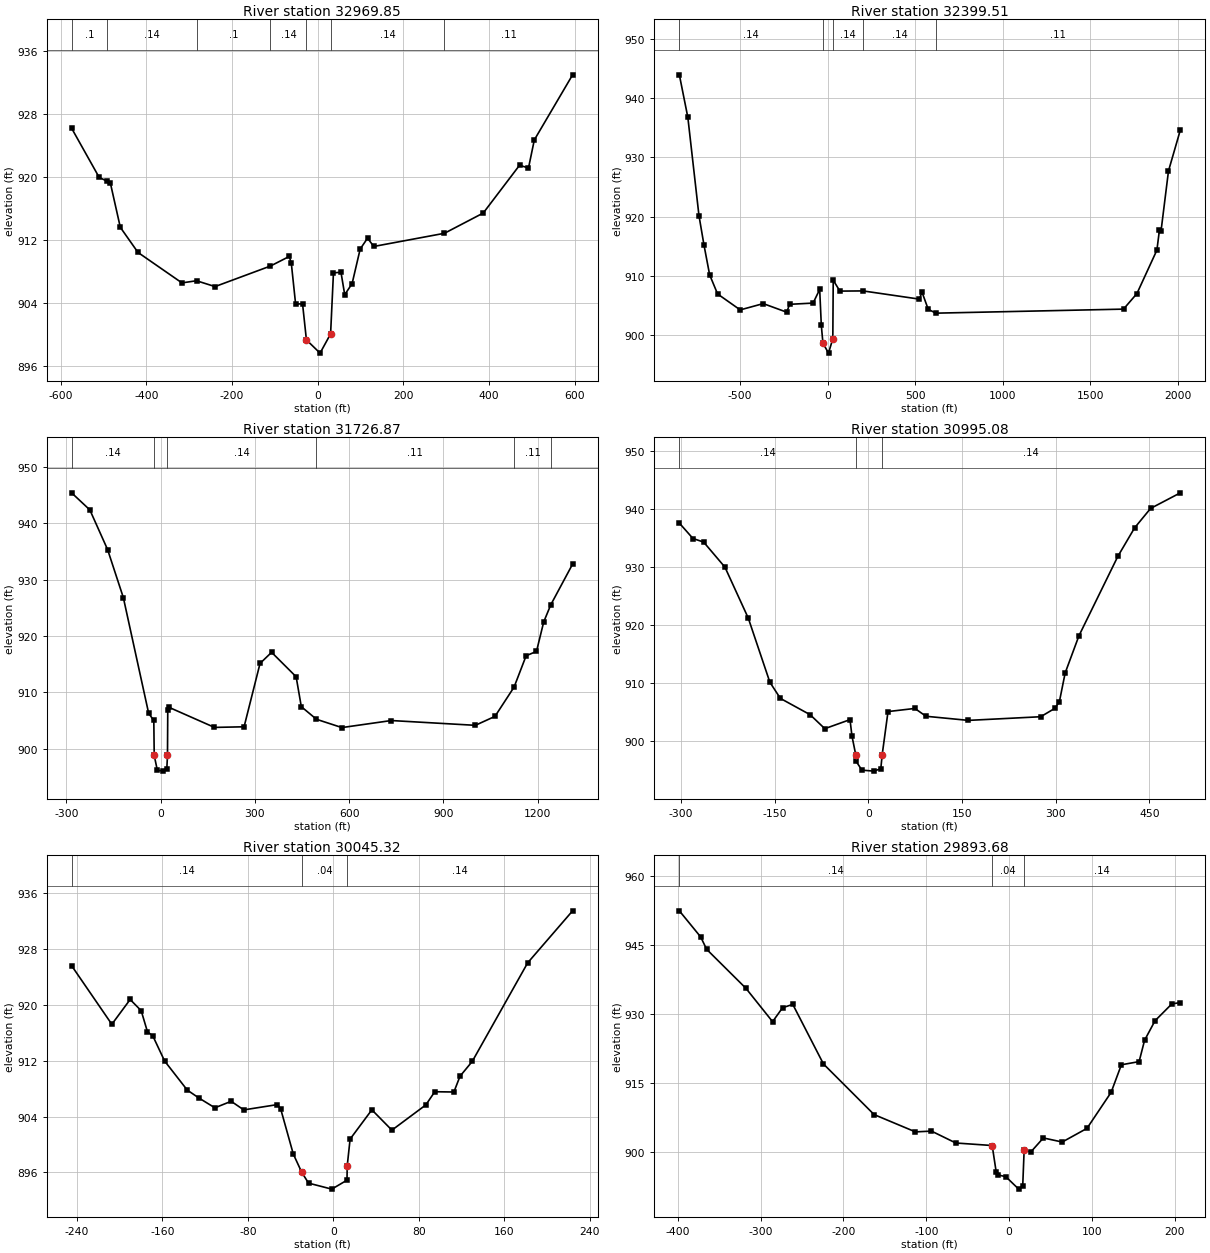
Type RM Length L Ch R = 1 ,32969.85,484.9809,570.3428,730.3533
BEGIN DESCRIPTION:
TWE_18X
END DESCRIPTION:
XS GIS Cut Line= 4
   1479424.24049   1120064.64501   1478916.31004   1119799.55643
   1478802.59646   1119744.93504   1478394.60925   1119979.31037
#Sta/Elev= 30
 -574.55  926.21 -510.05  919.96 -491.04  919.48 -483.93  919.23 -460.83  913.64
 -419.51  910.45 -316.93  906.59  -282.9  906.86 -239.66  906.12  -110.2  908.73
   -66.5  909.94  -61.66  909.11  -51.57   903.9  -35.39  903.94  -26.34  899.36
    5.51  897.68   30.09  900.12   36.77  907.86   54.33  907.94   63.08  905.09
   80.32   906.5   99.14  910.88   116.4  912.26  130.95  911.21  295.85  912.88
  386.46  915.45  471.21  921.51   492.1  921.16  505.67  924.72  595.07  932.98
#Mann= 7 ,-1,0
 -574.55      .1       0 -491.04     .14       0  -282.9      .1       0
  -110.2     .14       0  -26.34    .045       030.09003     .14       0
  295.85     .11       0
#XS Ineff= 2 , 0
Permanent Ineff=
       F       F
Bank Sta=-26.34,30.09
XS Rating Curve= 0 ,0
Exp/Cntr=0.3,0.1

Type RM Length L Ch R = 1 ,32399.51,860.4338,672.6442,491.1495
XS GIS Cut Line= 4
   1479803.44718   1119701.43241   1479038.20407   1119345.88878
   1477839.47474   1118812.22146   1477310.60564   1119279.52165
#Sta/Elev= 30
 -846.45  943.91 -797.99  936.74 -734.41  920.17 -705.66  915.19 -673.51  910.19
 -628.11  906.96 -498.89  904.27  -367.3  905.33 -232.78  903.88 -217.24  905.21
  -82.52  905.42  -44.92  907.72  -35.56  901.66  -26.34  898.66    5.51  896.98
   30.09  899.42   32.44  909.28   70.56  907.44  202.93  907.47  523.88  906.09
  539.76  907.25  575.06  904.37  618.87  903.72 1690.45   904.4 1767.02  907.02
 1881.24  914.35 1895.79  917.75    1905  917.61 1947.41   927.7 2015.25  934.62
#Mann= 5 ,-1,0
 -846.45     .14       0  -26.34     .04       030.09003     .14       0
  202.93     .14       0620.9899     .11       0
#XS Ineff= 2 , 0
Permanent Ineff=
       F       F
Bank Sta=-26.34,30.09
XS Rating Curve= 0 ,0
Exp/Cntr=0.3,0.1

Type RM Length L Ch R = 1 ,31726.87,456.2632,481.3701,514.452
XS GIS Cut Line= 4
   1479447.31332   1118664.81759   1479171.27165   1118698.67192
   1478832.72999   1118737.73425   1477964.48294   1118293.91273
#Sta/Elev= 30
 -282.94  945.44 -224.86  942.41 -168.33  935.36 -118.29  926.84  -37.69  906.29
  -21.37  905.03  -20.05  898.82  -10.23  896.21    8.91  896.04   20.01  896.46
   22.16  898.82   23.04  906.92   26.77  907.37  171.64   903.8  265.84  903.91
  316.62  915.16  353.44  917.13  431.47  912.79  447.93  907.48  496.22905.2398
  577.02  903.77  734.25  905.02 1001.59  904.17 1064.16  905.76 1124.92 910.963
 1163.22  916.52 1196.18  917.29 1219.13  922.52 1241.71925.5745 1311.07  932.79
#Mann= 6 ,-1,0
 -282.94     .14       0-20.0499     .04       0   22.16     .14       0
  496.22     .11       0 1124.92     .11       0 1241.71     .14       0
#XS Ineff= 2 , 0
Permanent Ineff=
       F       F
Bank Sta=-20.05,22.16
XS Rating Curve= 0 ,0
Exp/Cntr=0.3,0.1

Type RM Length L Ch R = 1 ,30995.08,457.8576,464.3595,353.1964
BEGIN DESCRIPTION:
TWE_17X
END DESCRIPTION:
XS GIS Cut Line= 4
   1479208.09285   1117820.67388   1478974.16339   1118011.68602
   1478796.23425   1118139.20538    1478515.0351   1118139.11155
#Sta/Elev= 30
 -302.51   937.6  -280.7  934.94 -263.64  934.33 -229.52     930 -192.14  921.21
  -157.6  910.16 -140.75  907.37  -93.15  904.56  -69.63  902.15  -29.29  903.71
   -26.2   900.9  -20.05  897.61  -19.93  896.59  -10.23     895    8.91  894.83
   20.01  895.25   22.16  897.61   31.55   905.1   74.58  905.64   92.34  904.29
  160.27  903.58  275.99  904.21  298.57  905.65  305.91   906.8  315.14  911.75
  337.22  918.17  399.48  931.86  426.34  936.78  451.92  940.13   499.6  942.82
#Mann= 3 ,-1,0
 -302.51     .14       0-20.0499     .04       0   22.16     .14       0
#XS Ineff= 2 , 0
Permanent Ineff=
       F       F
Bank Sta=-20.05,22.16
XS Rating Curve= 0 ,0
Exp/Cntr=0.3,0.1

Type RM Length L Ch R = 1 ,30045.32,97.19073,151.6482,202.5759
BEGIN DESCRIPTION:
TWE_16USX
END DESCRIPTION:
XS GIS Cut Line= 4
   1478282.83957   1117824.84547   1478178.07054     1117985.479
   1478212.42881   1118026.38156        1478358.   1118196.01345
#Sta/Elev= 30
 -244.99  925.59 -207.34   917.2  -190.2  920.75 -179.89  919.15 -173.99  916.12
 -169.03  915.55 -157.98  911.95  -136.8  907.79 -125.96  906.66 -110.93  905.25
   -95.7  906.18  -83.89  904.95  -52.41  905.71  -49.39   905.1  -37.59  898.64
  -29.78  896.05  -23.32  894.47   -1.57  893.61   12.66  894.89   12.87  896.92
   15.57  900.77   35.94  904.96   54.69  902.05   86.41  905.66    94.8  907.55
  112.69  907.51  118.41  909.77  129.86  911.89  181.72     926  223.74  933.44
#Mann= 3 ,-1,0
 -244.99     .14       0  -29.78     .04       012.87001     .14       0
#XS Ineff= 2 , 0
Permanent Ineff=
       F       F
Bank Sta=-29.78,12.87
XS Rating Curve= 0 ,0
Exp/Cntr=0.3,0.1

Type RM Length L Ch R = 1 ,29893.68,109.4181,105.9196,106.1071
BEGIN DESCRIPTION:
Reece Mill Rd (TWE_16) - US
END DESCRIPTION:
XS GIS Cut Line= 4
   1478272.65551   1117748.29692   1478155.16437   1118008.97999
   1478091.17356   1118107.06398   1477982.04626   1118287.61352
#Sta/Elev= 30
 -398.03  952.52-372.287  946.83-365.108  944.14-317.729  935.65-285.496  928.37
-273.461  931.41-261.132  932.14-224.123  919.16-162.976  908.13-113.085  904.36
 -93.714  904.53 -64.357  901.94 -20.464  901.39  -15.58  895.57 -13.777     895
  -4.018   894.6  11.562  891.89  16.377  892.52   18.12  900.43  26.344  900.02
  41.303  903.04  64.081  902.15  93.961  905.13 123.071  912.97  135.46  918.98
  156.87  919.67 163.468  924.32 176.074  928.57 196.371  932.24 206.662  932.54
#Mann= 3 ,-1,0
 -398.03     .14       0-20.4639     .04       0   18.12     .14       0
#XS Ineff= 2 , 0
Permanent Ineff=
       F       F
Bank Sta=-20.464,18.12
XS Rating Curve= 0 ,0
Skew Angle= 10
Exp/Cntr=0.3,0.1

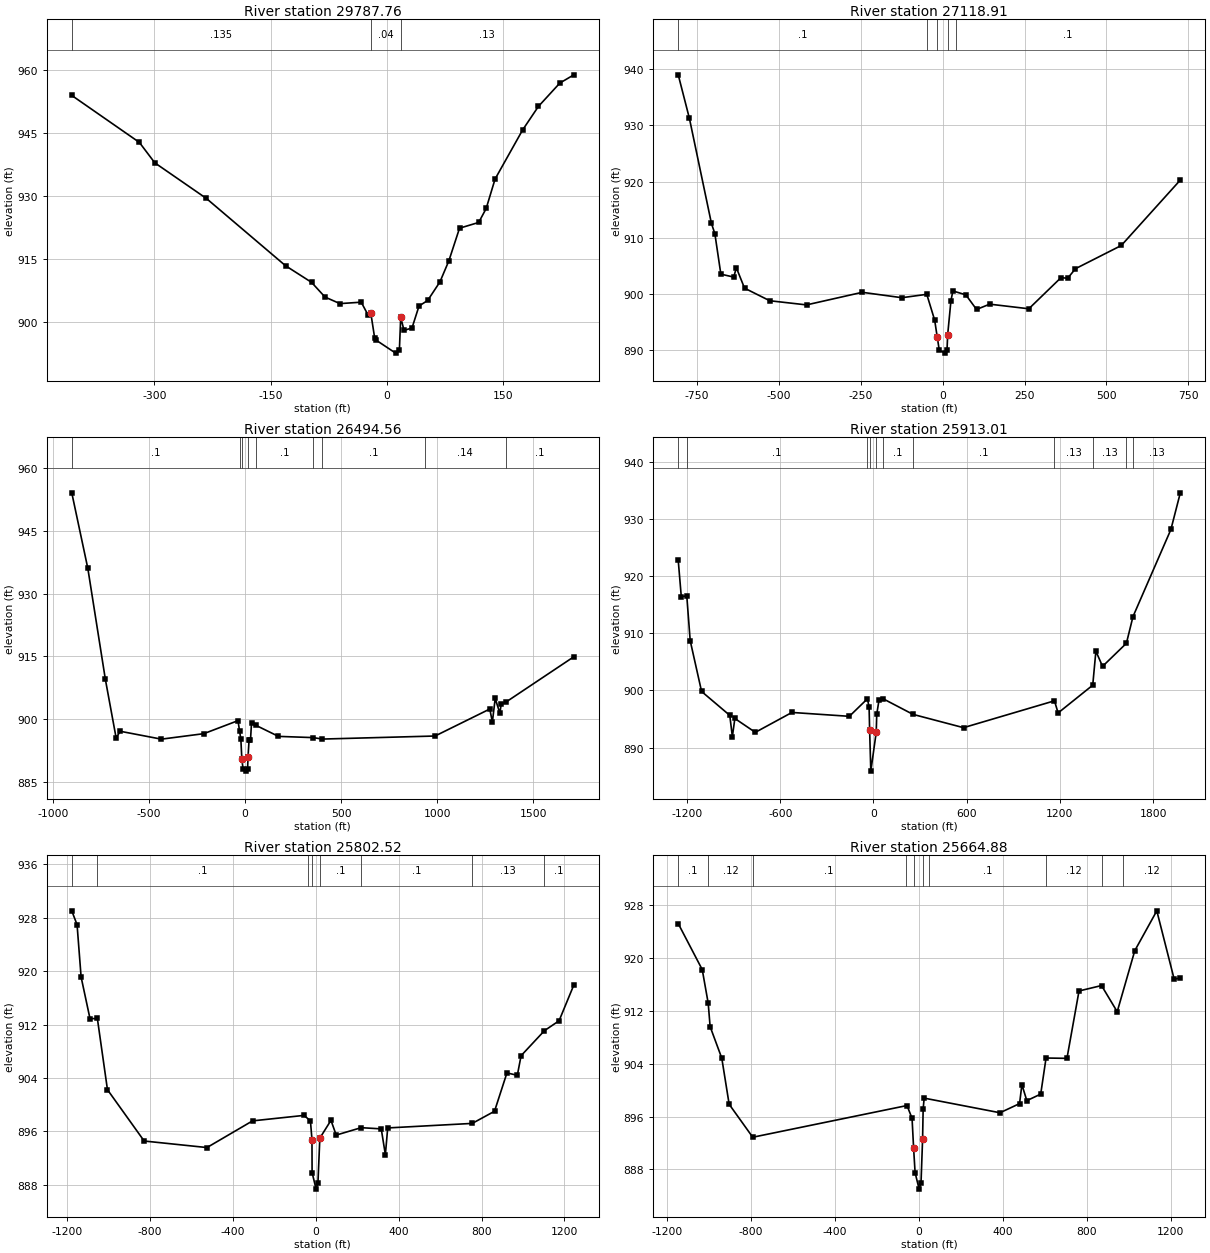
Type RM Length L Ch R = 1 ,29787.76,135.3192,202.6774,209.5373
BEGIN DESCRIPTION:
Reece Mill Rd (TWE_16) - DS
END DESCRIPTION:
XS GIS Cut Line= 4
   1478209.16765   1117726.30545   1477987.82644   1118081.65387
    1477932.0479   1118173.25098   1477800.65157   1118189.38812
#Sta/Elev= 30
-406.617  953.96-319.353  942.77-299.401   937.9 -232.72   929.4-130.625  913.38
 -97.023  909.42 -79.622  905.91 -60.369  904.35 -32.873  904.69 -24.128  901.66
 -20.464  902.05  -15.58  896.23 -13.777  895.66  11.562  892.55  16.377  893.18
   18.12  901.09  22.365  897.97  32.686  898.54  41.746  903.78  52.924   905.1
   68.74  909.52  80.301  914.56  94.049  922.32 118.788  923.69 128.468  927.02
 139.941  934.03 175.542  945.74 195.908  951.34 223.601  956.91 241.662  958.87
#Mann= 3 ,0,0
-406.617    .135       0 -20.464     .04       0   18.12     .13       0
#XS Ineff= 2 , 0
Permanent Ineff=
       F       F
Bank Sta=-20.464,18.12
XS Rating Curve= 0 ,0
Skew Angle= 10
Exp/Cntr=0.3,0.1

Type RM Length L Ch R = 1 ,27118.91,335.1646,624.3409,764.4692
BEGIN DESCRIPTION:
TWE_15X
END DESCRIPTION:
XS GIS Cut Line= 5
   1476604.37927   1116334.87041   1476195.52428   1116556.22539
   1476077.06693    1116877.9626   1475956.37434   1117235.91404
   1476062.71161   1117566.64403
#Sta/Elev= 30
 -807.49     939 -773.33  931.24 -706.15  912.57 -695.71  910.75 -677.36  903.54
 -638.16  903.02 -629.96  904.67 -605.11  901.05 -528.12  898.81 -415.78  898.07
 -245.71  900.31 -124.73  899.35  -48.63  899.95  -24.53  895.35  -16.84  892.39
  -10.51  890.01    6.95  889.49   13.06  889.96   15.18  892.78   25.14  898.82
   31.07  900.55   70.61  899.86   103.3  897.26  143.47   898.2  262.92  897.38
  361.15  902.92  381.55  902.81  405.36  904.51  545.26  908.64  725.44  920.28
#Mann= 5 ,-1,0
 -807.49      .1       0  -48.63     .12       0  -16.84    .045       0
15.17999     .12       039.66998      .1       0
#XS Ineff= 2 , 0
Permanent Ineff=
       F       F
Bank Sta=-16.84,15.18
XS Rating Curve= 0 ,0
Exp/Cntr=0.3,0.1

Type RM Length L Ch R = 1 ,26494.56,575.6857,581.5507,592.2119
XS GIS Cut Line= 3
   1476584.84777   1115963.77625   1475807.93701   1116389.12434
   1474314.87795   1117257.18143
#Sta/Elev= 30
 -901.87   954.1 -818.26  936.03 -727.05  909.53 -671.11  895.56 -649.38  897.12
 -435.53  895.24 -214.75  896.55  -36.95  899.66  -28.71  897.23  -21.88  895.16
  -16.84   890.5  -10.51  888.12    6.95   887.6   13.06  888.07   15.18  890.89
   20.89  895.07   28.15  894.97   33.45  899.07   56.12  898.55  173.89   895.9
  354.96  895.61  401.79  895.26  988.69  895.99 1273.45  902.44 1286.94  899.35
 1301.65  904.96 1325.94  901.46 1332.65  903.54 1356.64  904.07 1710.92  914.93
#Mann= 9 ,-1,0
 -901.87      .1       0  -28.71     .12       0  -16.84    .045       0
15.17999     .12       0   56.12      .1       0  354.96     .14       0
  401.79      .1       0935.7001     .14       0 1356.64      .1       0
#XS Ineff= 2 , 0
Permanent Ineff=
       F       F
Bank Sta=-16.84,15.18
XS Rating Curve= 0 ,0
Exp/Cntr=0.3,0.1

Type RM Length L Ch R = 1 ,25913.01,85.88181,110.4947,145.8901
BEGIN DESCRIPTION:
TWE_14USX
END DESCRIPTION:
XS GIS Cut Line= 6
   1476715.05643   1115304.05249   1475660.69915    1115811.4416
   1475593.04396   1115864.89698    1475514.5315   1115923.92126
   1474334.68832   1116633.46621   1473897.18734   1116390.41043
#Sta/Elev= 30
-1256.71   922.8-1237.02  916.43-1201.79  916.62 -1179.8  908.75 -1106.5  899.83
 -925.01  895.64  -908.3  891.91 -892.27  895.09 -760.54  892.66  -524.8  896.15
 -155.33  895.47  -39.15  898.54  -28.22  897.12  -24.72  893.03  -17.13  885.86
   17.58  892.64   21.18  895.85   35.94  898.36   63.37  898.53  254.61  895.81
  579.62  893.48 1165.01  898.19 1188.41  896.06 1411.34  900.93 1431.63  906.89
 1474.59  904.23 1628.11  908.28 1670.38  912.95 1914.45  928.23 1975.08  934.66
#Mann= 11 ,-1,0
-1256.71     .12       0-1201.79      .1       0  -39.15     .12       0
-24.7198    .045       017.57996     .12       0   63.37      .1       0
  254.61      .1       0 1165.01     .13       0 1411.34     .13       0
 1628.11      .1       0 1670.38     .13       0
#XS Ineff= 2 , 0
Permanent Ineff=
       F       F
Bank Sta=-24.72,17.58
XS Rating Curve= 0 ,0
Exp/Cntr=0.3,0.1

Type RM Length L Ch R = 1 ,25802.52,124.8866,137.6429,124.5588
BEGIN DESCRIPTION:
Shady Grove RD (TWE_14) - US
END DESCRIPTION:
XS GIS Cut Line= 6
   1476759.38911   1115198.56726   1475535.42848   1115775.82579
    1474715.1145   1116164.28117   1474564.28937   1116206.59875
   1474397.18832   1116226.13058   1474184.51444    1116230.4708
#Sta/Elev= 30
-1178.08  929.05-1152.49  926.97-1133.01  919.13-1089.97  912.87-1054.58  912.93
-1005.82  902.24-828.613  894.55-525.582  893.57 -305.43  897.57 -57.192  898.39
 -26.041  897.58 -18.628  894.76 -18.022  889.83    1.29  887.34  10.262  888.32
  19.347  894.98  73.058  897.65  98.406  895.44 218.723  896.55 315.788  896.37
 335.697   892.5 346.956  896.51 755.001  897.19 862.535  899.01 922.508  904.76
  972.59   904.4 990.889  907.341103.585  911.091174.097  912.571245.483  917.94
#Mann= 8 ,-1,0
-1178.08     .12       0-1054.58      .1       0-38.2088     .12       0
 -18.628    .045       019.34705      .1       0 218.723      .1       0
 755.001     .13       01103.585      .1       0
#XS Ineff= 2 , 0
Permanent Ineff=
       F       F
Bank Sta=-18.628,19.347
XS Rating Curve= 0 ,0
Skew Angle= 30
Exp/Cntr=0.3,0.1

Type RM Length L Ch R = 1 ,25664.88,778.3932,1245.781,1447.994
BEGIN DESCRIPTION:
Shady Grove RD (TWE_14) - DS
END DESCRIPTION:
XS GIS Cut Line= 5
   1476742.02822    1115077.0397    1475546.2792   1115641.27657
   1474856.17388    1115968.9685    1474556.6939   1116103.51739
   1474207.30085   1116127.38878
#Sta/Elev= 30
-1147.51  925.15-1033.05   918.2 -1004.6  913.12-995.505  909.59-939.854  904.82
-904.702  897.85-792.197  892.87 -56.603  897.66 -32.485  895.73 -25.141  891.26
 -18.022  887.52    1.29  885.03  10.262  886.01   17.71  892.54   20.43  897.14
  25.279  898.78 386.871  896.57 480.159  897.95 491.288  900.82 514.869   898.4
 581.042  899.39 606.495  904.84 706.174  904.79 763.713  914.97 870.996  915.79
  945.83  911.841029.635  921.061134.658  927.081217.554  916.741246.747  916.95
#Mann= 10 ,-1,0
-1147.51      .1       0 -1004.6     .12       0-792.197      .1       0
-63.5318     .14       0-25.1408    .045       017.70996     .14       0
46.62695      .1       0 606.495     .12       0 870.996     .06       0
971.6631     .12       0
#XS Ineff= 2 , 0
Permanent Ineff=
       F       F
Bank Sta=-25.141,17.71
XS Rating Curve= 0 ,0
Skew Angle= 30
Exp/Cntr=0.3,0.1

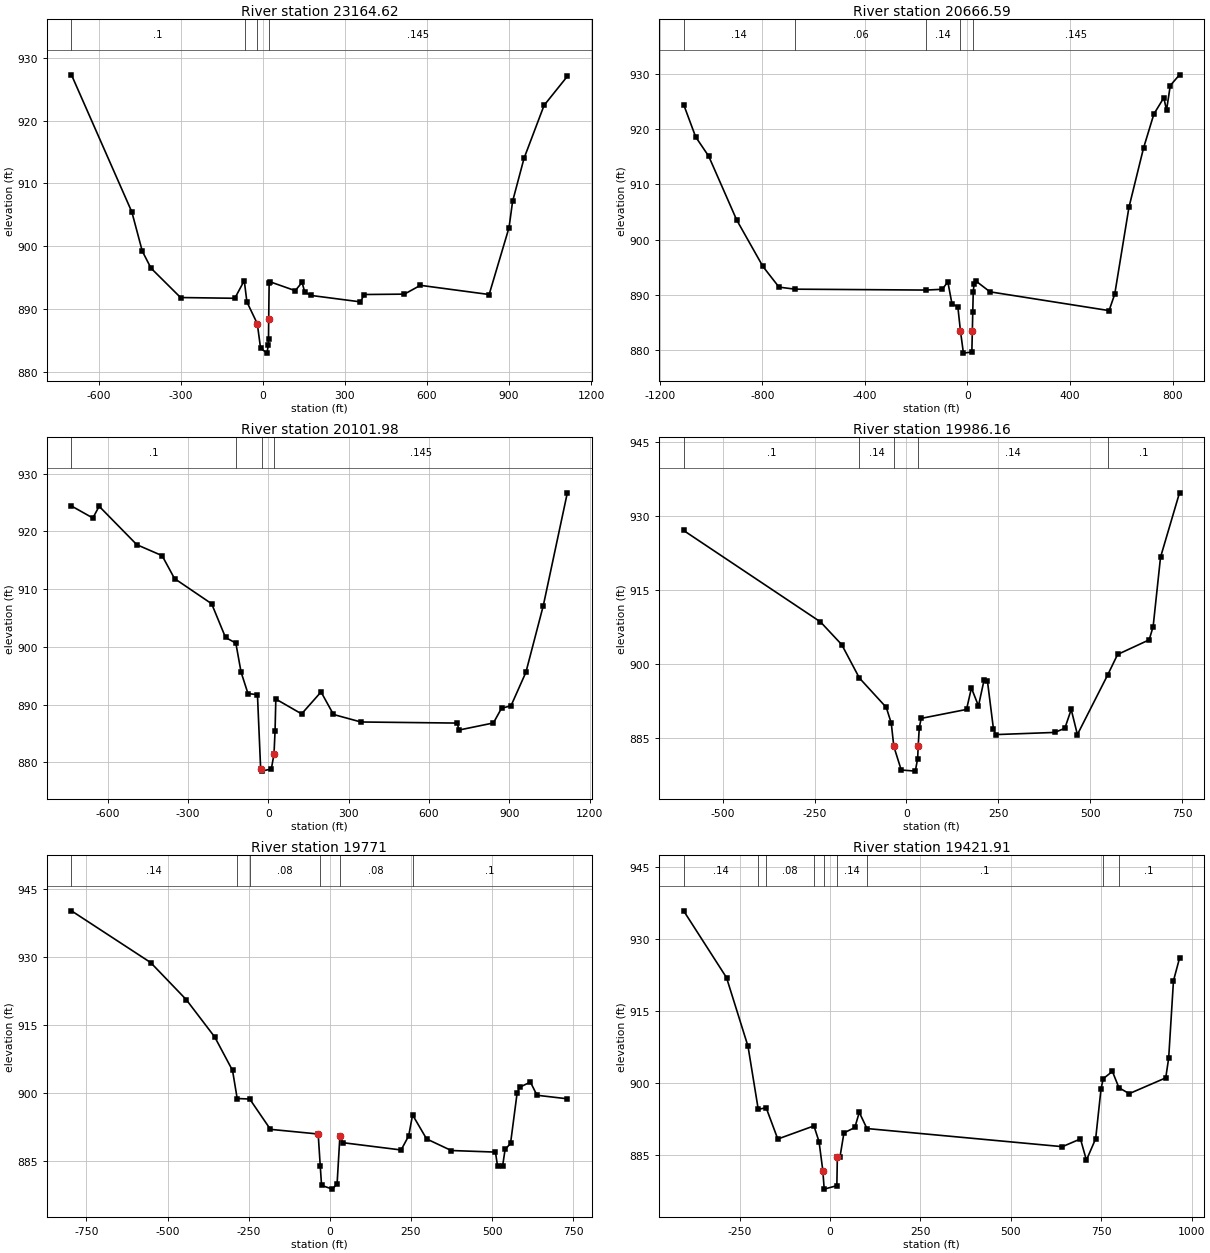
Type RM Length L Ch R = 1 ,23164.62,718.7921,759.3404,449.3556
XS GIS Cut Line= 4
   1477552.30676   1114699.58563   1477051.00361    1114202.6227
   1476736.33301   1113937.86549   1476039.71686   1113913.99377
#Sta/Elev= 30
  -700.6  927.27 -479.65  905.46 -441.53  899.24 -409.61  896.53 -301.46  891.86
 -102.98  891.74  -68.39  894.55  -58.74  891.16  -20.73   887.7   -8.79  883.82
    14.5  883.02   19.54  884.25   20.29   885.2   20.95  888.41   22.67  894.19
   24.63  894.38  118.11  892.95  143.03  894.28  152.96  892.71  176.29  892.19
  356.84  891.17  370.04  892.34  517.34   892.4  576.03   893.8  827.48  892.34
  900.23  902.98  913.33  907.16  955.07  913.99 1028.51  922.42 1113.54  927.03
#Mann= 4 ,-1,0
  -700.6      .1       0-65.8399     .14       0-20.7299    .045       0
20.95001    .145       0
#XS Ineff= 2 , 0
Permanent Ineff=
       F       F
Bank Sta=-20.73,20.95
XS Rating Curve= 0 ,0
Exp/Cntr=0.3,0.1

Type RM Length L Ch R = 1 ,20666.59,564.6,564.6,564.6
BEGIN DESCRIPTION:
TWE_11X
END DESCRIPTION:
XS GIS Cut Line= 4
   1478404.08793   1111901.40289   1477303.00787   1112023.66371
   1477126.72736   1112046.60039    1476716.8107   1112548.89272
#Sta/Elev= 30
-1106.95  924.42-1060.05  918.57-1009.25  915.09 -899.75  903.54 -797.75  895.17
 -734.95  891.44 -672.55  891.07 -160.65  890.91  -98.05  891.05  -76.55   892.4
  -60.35  888.42  -37.45  887.88  -27.35  883.53  -15.75  879.52   17.15  879.72
   19.05  883.53   20.75  886.98   22.55   890.6   25.85  892.04   34.25   892.5
   87.85  890.59  552.35   887.2  574.45  890.18  629.75  905.83  686.75  916.56
  727.05  922.69  765.85  925.64  776.45   923.4  791.05  927.85  827.05  929.78
#Mann= 5 ,-1,0
-1106.95     .14       0 -672.55     .06       0 -160.65     .14       0
  -27.35     .04       0   20.75    .145       0
#XS Ineff= 2 , 0
Permanent Ineff=
       F       F
Bank Sta=-27.35,19.05
XS Rating Curve= 0 ,0
Exp/Cntr=0.3,0.1

Type RM Length L Ch R = 1 ,20101.98,105.6221,115.8291,169.4414
BEGIN DESCRIPTION:
TWE_10USX
END DESCRIPTION:
XS GIS Cut Line= 4
   1477888.46194   1111433.08596    1477321.6998   1111418.33793
   1477172.48917   1111494.65551     1476193.146    1112032.0456
#Sta/Elev= 30
 -734.65  924.38 -654.75   922.3 -631.25  924.33 -490.65  917.68 -396.15  915.78
 -349.75  911.81 -211.15  907.45 -159.35  901.61 -120.85  900.64 -101.35  895.62
  -75.55   891.9  -40.15  891.71  -28.15  878.78  -22.95  878.47   11.75  878.86
   21.65  881.43   25.55  885.37   28.45  890.95  124.75  888.38  197.35  892.18
  243.65  888.28  345.95  886.98  705.75  886.79  712.15  885.58  840.85  886.81
  871.15  889.35  906.65  889.79  962.15  895.57 1027.25  907.14 1116.95  926.66
#Mann= 4 ,-1,0
 -734.65      .1       0 -120.85     .14       0  -22.95    .035       0
   21.65    .145       0
Bank Sta=-28.15,21.65
XS Rating Curve= 0 ,0
Exp/Cntr=0.3,0.1

Type RM Length L Ch R = 1 ,19986.16,164.8615,199.5731,183.0735
BEGIN DESCRIPTION:
Walhalla Hwy (TWE_10) - US
END DESCRIPTION:
XS GIS Cut Line= 6
    1477849.2818    1111415.8717    1476783.3071    1111391.5659
    1476604.4875    1111370.7326    1476408.3064    1111407.1909
    1476338.8622    1111433.2326    1476213.8619    1111415.8717
#Sta/Elev= 30
 -605.91  927.02 -233.81  908.53 -176.01  903.93 -127.91  897.17  -54.81  891.23
  -41.21  888.02  -34.41  883.36  -14.21  878.57   24.09  878.34   30.49  880.88
   31.89  883.36   34.89  887.08   39.99  889.01  163.39  890.82  176.69  895.15
  195.89  891.53  211.29  896.83  220.39  896.49  236.49  886.95  242.59  885.73
  403.29  886.17  430.79  887.01  448.09  890.81  464.89  885.74  546.99  897.76
  574.19  901.94  660.09   904.9  670.89  907.59  690.99  921.62  742.59  934.64
#Mann= 5 ,-1,0
 -605.91      .1       0 -127.91     .14       0  -34.41    .035       0
   31.89     .14       0  546.99      .1       0
#XS Ineff= 2 , 0
Permanent Ineff=
       F       F
Bank Sta=-34.41,31.89
XS Rating Curve= 0 ,0
Skew Angle= 35
Exp/Cntr=0.3,0.1

Type RM Length L Ch R = 1 ,19771   ,297.5,359.2,349.6
XS GIS Cut Line= 6
    1477797.9587       1111252.6    1477340.1051    1111254.1761
    1477007.1185    1111217.8214    1476697.2407     1111219.325
     1476533.666    1111195.4944    1476304.3001    1111316.0996
#Sta/Elev= 30
 -796.18  940.23 -552.18  928.82 -442.68  920.66 -354.58  912.39 -299.78  905.02
 -285.38  898.82 -246.78  898.71 -182.98  892.02  -35.78  890.99  -29.38  883.92
  -25.38  879.66    8.12  878.83   22.52  880.03   31.22  890.56   39.82  889.08
  219.82  887.47  243.12  890.57  255.12  895.21  298.32  889.91  374.32  887.35
  510.52     887  517.22  883.83  532.42  883.83  540.32  887.59  557.02   888.9
  577.32  900.01  585.22  901.31  618.32  902.45  638.62  899.54  732.12  898.76
#Mann= 6 ,-1,0
 -796.18     .14       0 -285.38     .06       0 -246.78     .08       0
  -29.38    .035       0   31.22     .08       0  255.12      .1       0
#XS Ineff= 2 , 0
Permanent Ineff=
       F       F
Bank Sta=-35.78,31.22
XS Rating Curve= 0 ,0
Exp/Cntr(USF)=0,0
Exp/Cntr=0.3,0.1

Type RM Length L Ch R = 1 ,19421.91,522.9336,465.7054,185.1479
XS GIS Cut Line= 4
   1477377.90814   1110938.60761   1476974.30643   1110885.60925
   1476780.65879   1110857.07185   1476199.35663   1111360.24377
#Sta/Elev= 30
 -405.13  935.83 -286.53  921.94 -227.03  907.64 -198.73  894.53 -176.93  894.89
 -144.73  888.37  -44.73   891.1  -30.53   887.8  -20.13   881.8  -16.33  877.95
   18.67  878.67   20.07  884.68   27.37  884.66   38.27  889.64   68.47  890.77
   80.67  893.92  101.87  890.55  642.47  886.78  692.47  888.39  708.97  883.98
  734.57  888.44  749.47  898.84  755.47  900.92  780.87  902.43  798.87  899.03
  827.47  897.81  928.37  901.09  936.47  905.17  949.77  921.28  966.47  925.97
#Mann= 9 ,-1,0
 -405.13     .14       0 -198.73     .06       0 -176.93     .08       0
  -44.73     .14       0  -16.33    .045       0   20.07     .14       0
  101.87      .1       0  755.47     .06       0  798.87      .1       0
#XS Ineff= 2 , 0
Permanent Ineff=
       F       F
Bank Sta=-20.13,20.07
XS Rating Curve= 0 ,0
Exp/Cntr=0.3,0.1

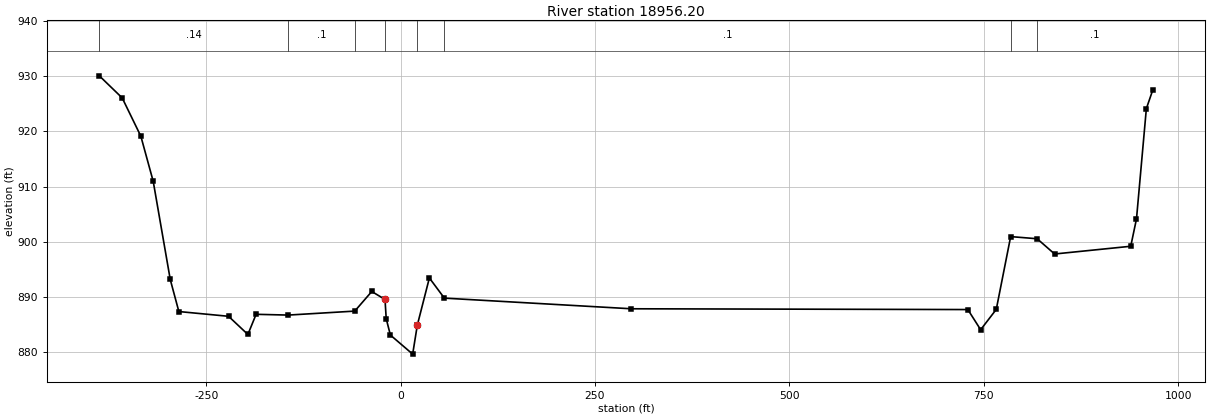
Type RM Length L Ch R = 1 ,18956.20,41.10629,40.11645,40.70418
BEGIN DESCRIPTION:
Unnamed Foot Bridge - US
END DESCRIPTION:
XS GIS Cut Line= 4
   1477022.27493   1110294.26903    1476747.2523   1110536.14403
   1476686.03609   1110595.77953   1476183.73163   1111346.35466
#Sta/Elev= 30
 -387.46  930.08 -358.06  926.08 -334.06  919.14 -318.16  910.97 -296.26  893.21
 -285.19   887.4 -221.27  886.54  -196.4  883.25 -185.84   886.9  -144.5  886.76
  -58.94  887.48  -37.06  891.03  -20.04  889.59  -18.48   886.1  -13.12  883.14
   15.54  879.69   21.53  884.95   37.02  893.48   56.28  889.83  296.97   887.9
  729.58  887.76  746.05  884.11  766.15  887.79  784.65  900.97  818.74  900.58
  841.17  897.82  939.09  899.22   946.5  904.18  959.18  924.14   967.4   927.5
#Mann= 8 ,-1,0
 -387.46     .14       0  -144.5      .1       0  -58.94     .14       0
  -20.04    .045       0   21.53     .14       0   56.28      .1       0
  784.65     .06       0  818.74      .1       0
#XS Ineff= 2 , 0
Permanent Ineff=
       F       F
Bank Sta=-20.04,21.53
XS Rating Curve= 0 ,0
Exp/Cntr=0.3,0.1