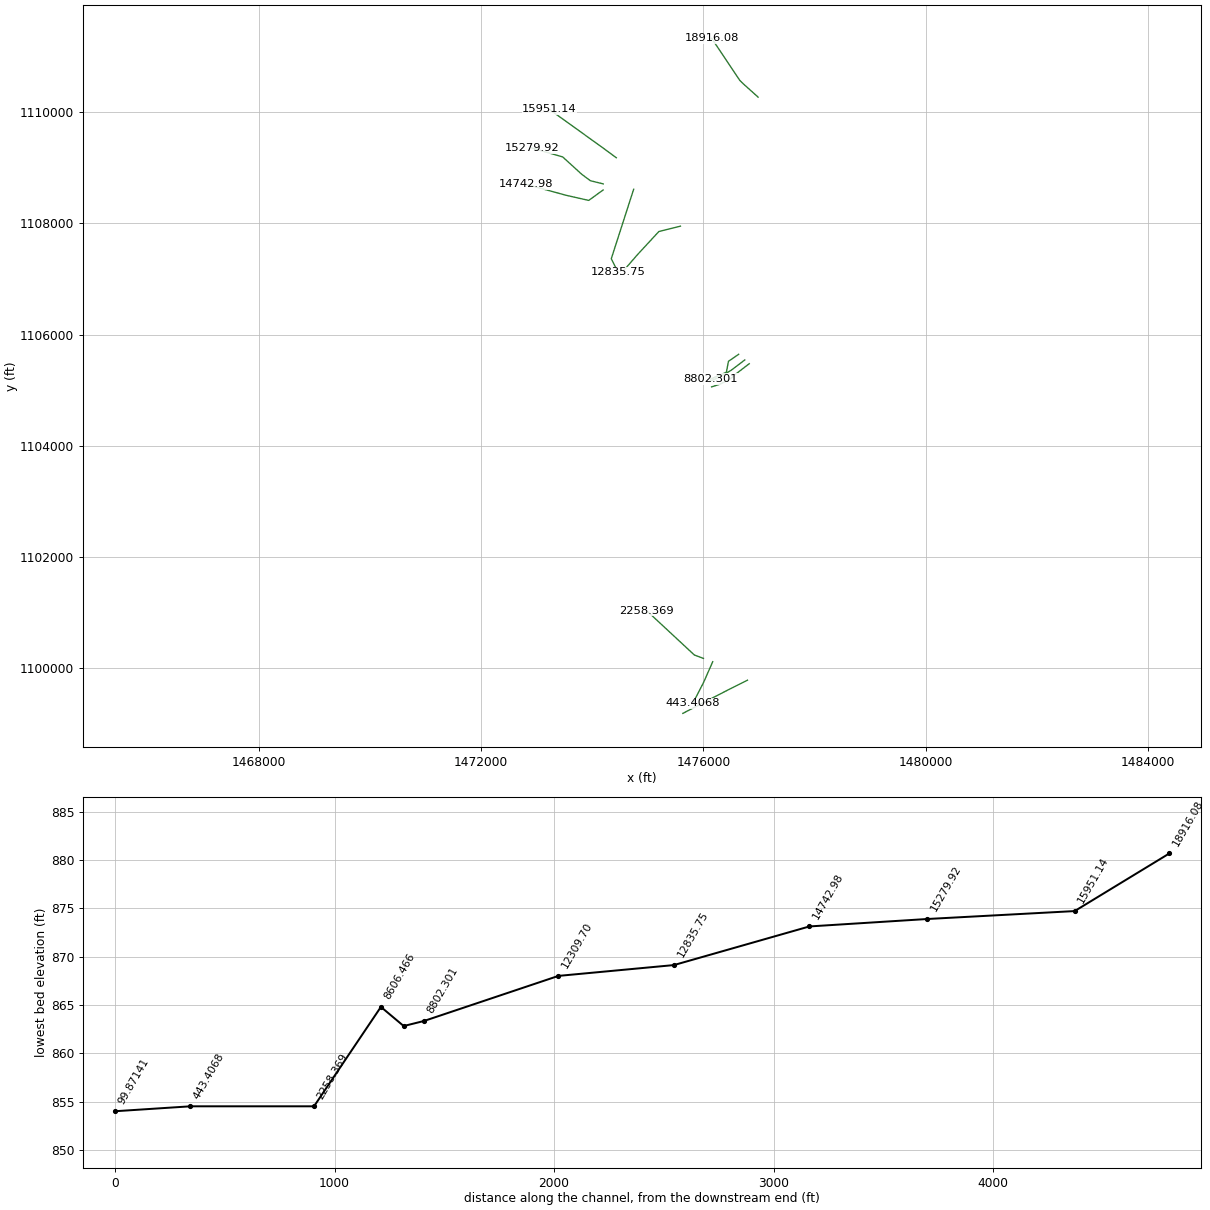
HEC-RAS study 12mile_Combined.prj: 12mile Creek Combined Model

--- 12mile_Combined.g03 (geometry) --- (continued)

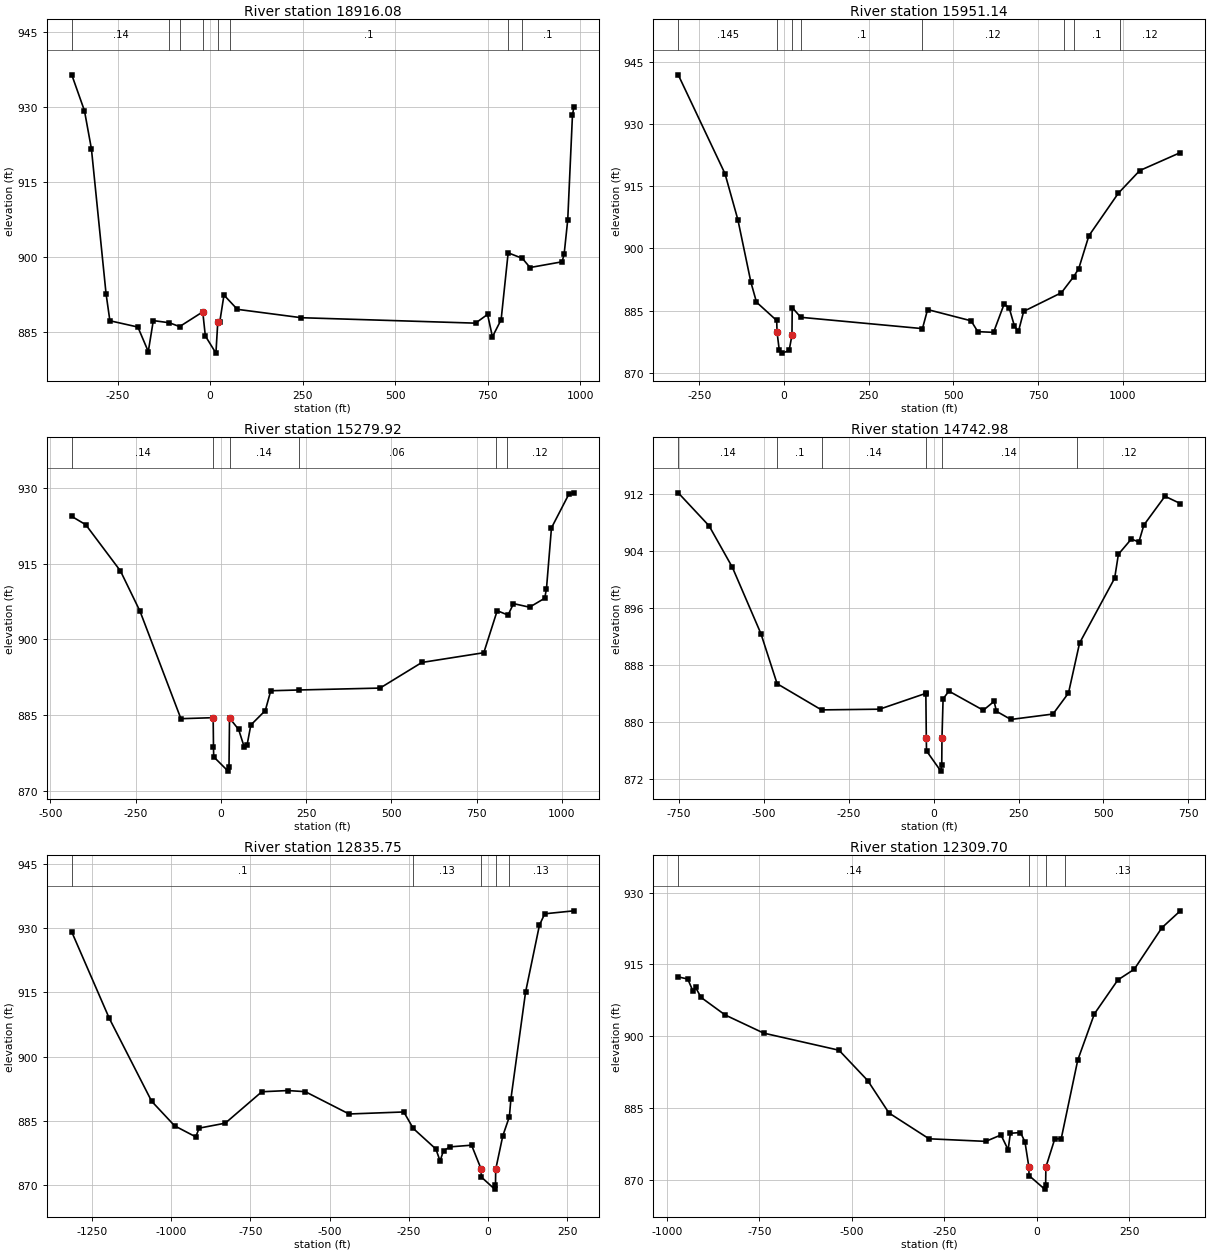
Type RM Length L Ch R = 1 ,18916.08,435.3299,431.5941,310.5046
BEGIN DESCRIPTION:
Unnamed Foot Bridge - DS
END DESCRIPTION:
XS GIS Cut Line= 4
   1476984.08038   1110269.96358   1476720.07054   1110506.78117
   1476655.09383    1110570.0794   1476149.00951   1111327.25755
#Sta/Elev= 30
 -373.84  936.48 -339.56  929.28 -320.74  921.63 -281.28  892.62  -270.9  887.18
 -195.29  885.92 -167.17     881 -153.62  887.21 -110.45  886.78  -82.54  886.01
  -20.05  888.96  -13.12  884.14   15.54  880.69   20.54  886.92   25.82   886.9
   37.25  892.33   73.33  889.47  246.13  887.79  716.64   886.7  749.21  888.45
  762.39  883.96  785.88   887.4  804.84   900.8   843.3  899.68  863.88  897.85
   950.6     899  956.17  900.62  965.77  907.41  978.51  928.36  982.27  930.01
#Mann= 8 ,-1,0
 -373.84     .14       0 -110.45      .1       0  -82.54     .14       0
-20.0499    .035       020.54001     .14       053.10001      .1       0
804.8401     .06       0   843.3      .1       0
#XS Ineff= 2 , 0
Permanent Ineff=
       F       F
Bank Sta=-20.05,20.54
XS Rating Curve= 0 ,0
Exp/Cntr=0.3,0.1

Type RM Length L Ch R = 1 ,15951.14,634.259,671.2197,597.0951
XS GIS Cut Line= 3
   1474433.54528   1109179.72375   1474183.54495   1109363.75197
   1473232.15387   1110047.78084
#Sta/Elev= 30
 -311.99  941.84 -173.96     918 -135.85  906.87  -97.35  891.78  -80.98  887.01
  -21.34  882.59  -20.25  879.76  -13.66   875.4    -4.3  874.72   15.38  875.38
   23.72  879.02   24.53  885.71   49.76  883.36  408.95  880.63  424.13  885.23
  552.48  882.52  572.39   879.9  618.87  879.73  650.14  886.57  664.98  885.63
  680.57  881.25  692.38  879.97  707.81  884.79  819.26  889.29  855.46  893.17
  870.33   895.1  900.27  903.02  987.27  913.29 1050.45  918.75 1170.21  923.08
#Mann= 8 ,-1,0
 -311.99    .145       0  -20.25     .04       0   23.72     .14       0
49.76001      .1       0  408.95     .12       0825.8301     .06       0
  855.46      .1       0992.8301     .12       0
#XS Ineff= 2 , 0
Permanent Ineff=
       F       F
Bank Sta=-20.25,23.72
XS Rating Curve= 0 ,0
Exp/Cntr=0.3,0.1

Type RM Length L Ch R = 1 ,15279.92,420.462,536.9451,576.9656
XS GIS Cut Line= 5
   1474198.43045   1108709.60466   1473967.45801   1108766.40125
   1473812.21424   1108881.88747   1473469.54199   1109194.26804
   1472914.82972    1109355.1916
#Sta/Elev= 30
 -437.52  924.32 -396.52  922.68 -294.79  913.53 -237.25  905.53 -117.42  884.28
   -22.8  884.48  -21.86  878.61  -21.21  876.73   20.95   873.9   23.65  874.78
   25.18  884.41   51.85  882.15   67.87  878.77   76.61  879.06   87.67  883.03
  130.12  885.89  146.08  889.81  227.78  889.96   466.7  890.34  589.28  895.41
  770.98  897.34  810.33  905.66  842.05  904.79  858.09  907.06  905.13  906.35
  949.77  908.13  954.83  910.04  969.44  922.05 1020.32   928.7 1035.09  928.99
#Mann= 6 ,-1,0
 -437.52     .14       0-22.7999     .04       025.17999     .14       0
  227.78     .06       0805.4398     .06       0837.8198     .12       0
#XS Ineff= 2 , 0
Permanent Ineff=
       F       F
Bank Sta=-22.8,25.18
XS Rating Curve= 0 ,0
Exp/Cntr=0.3,0.1

Type RM Length L Ch R = 1 ,14742.98,439.5438,617.3231,671.8304
XS GIS Cut Line= 4
   1474197.43373   1108599.86122    1473937.0164   1108412.36089
   1473523.82119   1108506.11089   1472815.48622    1108700.5561
#Sta/Elev= 30
 -752.65  912.13 -661.71   907.5 -593.17  901.69 -509.03  892.39 -461.38  885.38
 -330.57  881.71 -159.52  881.81  -23.77  884.02  -23.14   883.9  -21.86  877.84
  -21.21  875.96   20.95  873.13   23.65  874.01   24.31  877.73   27.61  883.26
   44.79  884.34  146.11  881.66  177.92  882.91  184.68  881.52  227.26  880.37
  351.37  881.13  397.03  884.07  429.71  891.08  533.09  900.17  544.08  903.52
  582.27  905.66  604.36  905.23  619.06  907.61  681.23  911.65  726.48  910.63
#Mann= 6 ,-1,0
 -752.65     .14       0 -461.38      .1       0 -330.57     .14       0
-21.8599     .04       0   24.31     .14       0420.7001     .12       0
#XS Ineff= 2 , 0
Permanent Ineff=
       F       F
Bank Sta=-21.86,24.31
XS Rating Curve= 0 ,0
Exp/Cntr=0.3,0.1

Type RM Length L Ch R = 1 ,12835.75,550.2411,526.0508,447.1309
XS GIS Cut Line= 3
   1474746.04593   1108613.75033   1474343.26739    1107363.7477
   1474464.79528    1107120.6916
#Sta/Elev= 30
-1314.03  929.05-1195.56  908.92-1061.89  889.61 -989.31  883.88 -922.62  881.31
 -911.92  883.34 -829.43   884.5 -714.09  891.82 -631.73   892.1 -576.79  891.84
 -438.68  886.64 -265.82  887.11 -235.95  883.27 -164.48  878.47 -151.31  875.68
 -140.45   878.1 -119.24  878.98  -51.87  879.37  -21.86  873.84  -21.21  871.96
   20.95  869.13   23.65  870.01   24.31  873.73   46.74  881.55   67.51  886.01
   72.31  890.16  118.53  915.01  162.49  930.67  179.15  933.29  271.01  933.98
#Mann= 5 ,-1,0
-1314.03      .1       0 -235.95     .13       0-21.8598     .04       0
24.31006     .13       064.90002     .13       0
#XS Ineff= 2 , 0
Permanent Ineff=
       F       F
Bank Sta=-21.86,24.31
XS Rating Curve= 0 ,0
Exp/Cntr=0.3,0.1

Type RM Length L Ch R = 1 ,12309.70,680.5234,612.7648,355.1502
XS GIS Cut Line= 4
   1475587.19324    1107949.2523   1475199.17192   1107852.89797
   1474813.75427   1107436.23064    1474558.5456   1107141.95899
#Sta/Elev= 30
  -969.3  912.36 -943.64  911.92 -929.06  909.32 -922.59  910.17 -907.54  908.07
 -842.62  904.41 -738.26  900.61 -534.83  897.04 -457.14  890.69 -399.72  883.92
 -291.47  878.53 -138.17  877.99  -97.03  879.33  -77.77  876.24  -71.65  879.68
   -44.3  879.84  -32.25  877.89  -21.86  872.72  -21.21  870.84   20.95  868.01
   23.65  868.89   24.31  872.61    48.2  878.48   65.78  878.56  110.41  894.97
  155.34  904.63  218.87  911.73  263.11  913.96  337.86  922.64  387.61  926.17
#Mann= 4 ,-1,0
  -969.3     .14       0-21.8599     .04       0   24.31     .14       0
77.28998     .13       0
#XS Ineff= 2 , 0
Permanent Ineff=
       F       F
Bank Sta=-21.86,24.31
XS Rating Curve= 0 ,0
Exp/Cntr=0.3,0.1

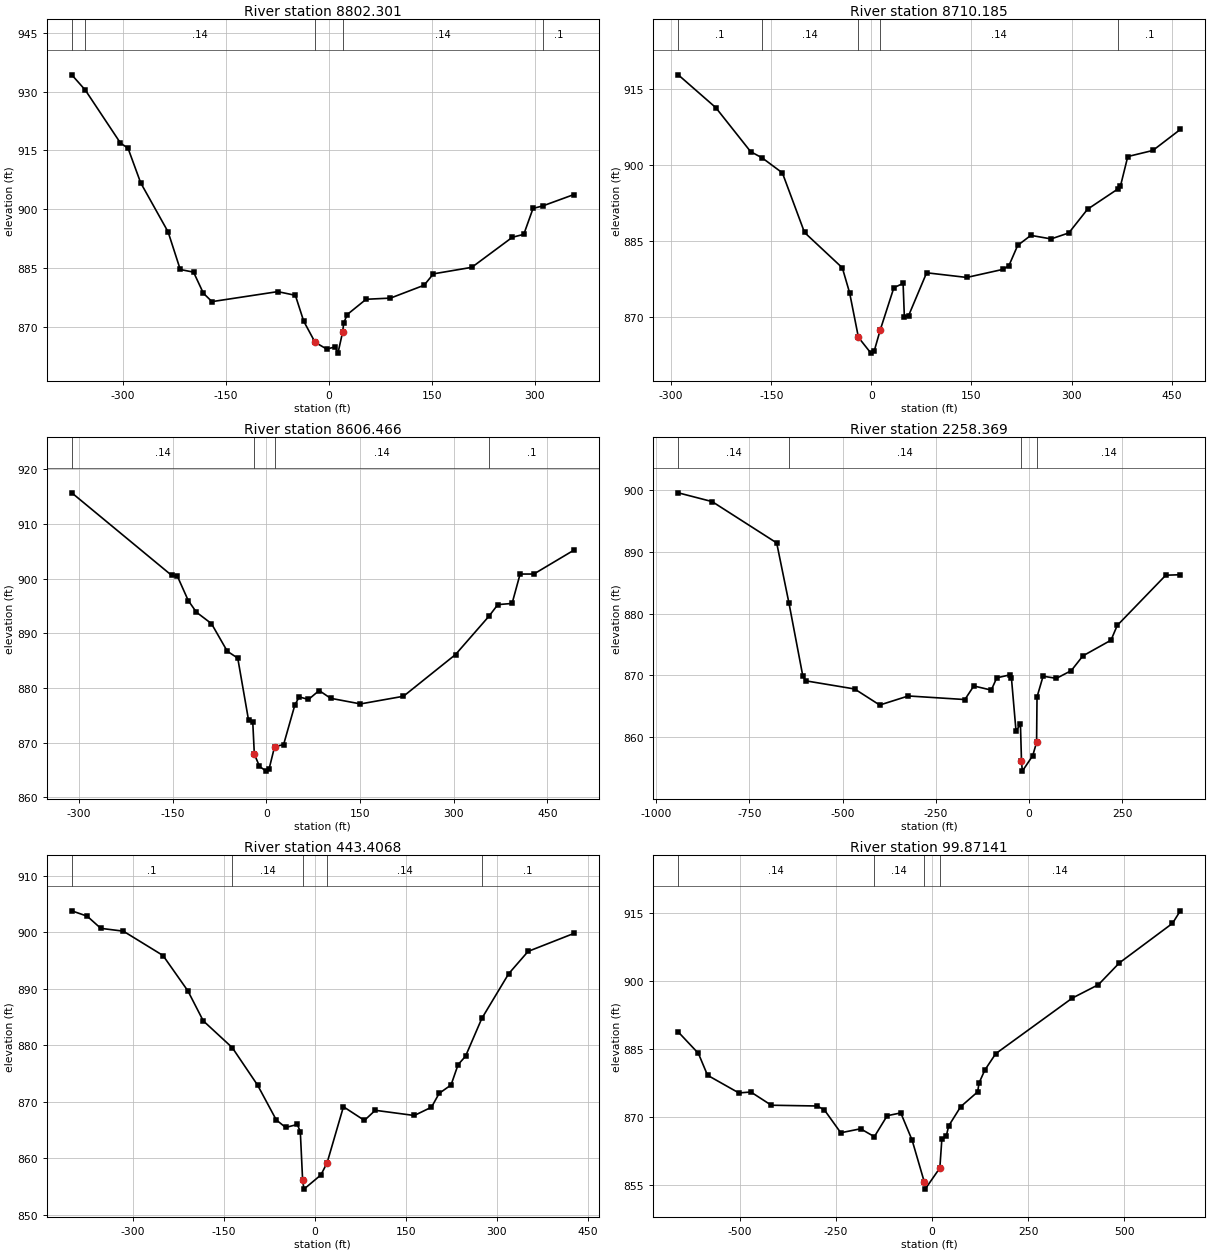
Type RM Length L Ch R = 1 ,8802.301,132.8714,92.11585,37.6268
BEGIN DESCRIPTION:
TWE_05USX
END DESCRIPTION:
XS GIS Cut Line= 5
   1476634.07054   1105644.56037   1476450.24344    1105517.7185
   1476422.40682   1105368.48458   1476413.12828   1105321.31759
   1476129.35171   1105199.14665
#Sta/Elev= 30
 -374.95  934.25 -355.29  930.38 -303.99  916.88 -292.87  915.53 -274.47  906.74
 -234.48  894.23 -216.76  884.65 -197.34  883.97 -182.99  878.59 -170.49  876.46
  -74.54  879.01  -48.88  878.07  -36.72  871.48   -20.2  866.11   -3.21  864.38
    9.21  864.93   13.22  863.34   19.92  868.61   21.69  871.04   26.82  873.18
   54.25  877.06   89.85  877.36  138.87  880.64  152.42  883.54  208.43   885.2
  267.47  892.85  284.23  893.61  297.72  900.21  311.91  900.85  357.23  903.74
#Mann= 5 ,-1,0
 -374.95      .1       0 -355.29     .14       0   -20.2     .04       0
19.92001     .14       0  311.91      .1       0
#XS Ineff= 2 , 0
Permanent Ineff=
       F       F
Bank Sta=-20.2,19.92
XS Rating Curve= 0 ,0
Exp/Cntr=0.3,0.1

Type RM Length L Ch R = 1 ,8710.185,103.9837,103.7191,140.4866
BEGIN DESCRIPTION:
Allgoud Bridge Dr (TWE_05) - US
END DESCRIPTION:
XS GIS Cut Line= 5
   1476744.19521   1105543.17126   1476503.45604   1105360.07382
   1476427.71129   1105314.85466   1476313.57743   1105244.79035
   1476105.04954   1105153.24147
#Sta/Elev= 30
 -289.38  917.72 -233.19  911.26 -180.86  902.56 -163.67  901.34 -133.34  898.38
 -100.14  886.62   -43.5  879.65  -32.56  874.71  -19.38  865.93    -.69  862.82
    4.23  863.21   13.07  867.29   33.71  875.72   47.55  876.58   49.46  869.97
   55.82  870.22   82.83  878.67  142.94  877.75  197.15  879.34  206.04  880.05
  219.26  884.07  238.97  886.05  269.33  885.35  295.87  886.53   323.9   891.2
  369.95  895.25  373.17  895.72  384.22   901.6  421.82   902.8  462.95  906.94
#Mann= 5 ,-1,0
 -289.38      .1       0 -163.67     .14       0  -19.38     .04       0
13.07001     .14       0  369.95      .1       0
#XS Ineff= 2 , 0
Permanent Ineff=
       F       F
Bank Sta=-19.38,13.07
XS Rating Curve= 0 ,0
Exp/Cntr=0.3,0.1

Type RM Length L Ch R = 1 ,8606.466,318.6339,304.7363,258.2462
BEGIN DESCRIPTION:
Allgoud Bridge Dr (TWE_05) - DS
END DESCRIPTION:
XS GIS Cut Line= 6
   1476824.72441   1105475.35728   1476573.81299   1105283.78314
   1476516.17126   1105228.68438   1476452.59547   1105184.60531
   1476302.65978   1105108.77625    1476147.4334   1105058.30184
#Sta/Elev= 30
 -311.75  915.69 -151.84   900.6 -142.69  900.46 -125.24     896 -112.15  893.86
  -88.01  891.77  -62.74  886.73  -45.93  885.46  -28.66  874.13  -21.89  873.77
  -19.38  867.91  -11.13  865.68    -.69   864.8    4.23  865.19   13.07  869.27
   27.49  869.65   45.46  876.87   52.48  878.38   67.32   877.9   84.41  879.54
  102.79  878.12  150.59  877.09  219.44  878.49  302.84  886.12  356.28  893.11
  370.56  895.25  393.39  895.46  406.25  900.84  428.21  900.84  492.32   905.2
#Mann= 4 ,-1,0
 -311.75     .14       0  -19.38     .04       013.07001     .14       0
  356.28      .1       0
#XS Ineff= 2 , 0
Permanent Ineff=
       F       F
Bank Sta=-19.38,13.07
XS Rating Curve= 0 ,0
Exp/Cntr=0.3,0.1

Type RM Length L Ch R = 1 ,2258.369,511.7773,562.8007,577.5682
XS GIS Cut Line= 5
   1476001.42979   1100175.31496   1475837.36713    1100236.5128
   1475276.86581   1100757.43898   1475055.04167   1100963.62238
   1474978.96883   1101032.19423
#Sta/Elev= 30
 -940.29  899.57 -849.44  898.15 -676.45  891.46 -643.46  881.69 -606.41  869.91
  -598.6  869.13 -467.52  867.81 -400.32  865.21 -323.68  866.68 -172.11   866.1
 -148.18   868.3 -101.41  867.63  -86.64  869.61  -49.99  870.12  -47.38  869.63
  -35.09  861.04  -23.14  862.07  -20.35  856.09  -18.12  854.51    9.82  857.02
   20.09  859.18   21.26  866.52   37.53  869.88   73.24  869.53  112.98  870.78
  144.18  873.17  219.51  875.71  236.22   878.1  366.34  886.23  405.27  886.31
#Mann= 4 ,-1,0
 -940.29     .14       0 -643.46     .14       0-20.3499     .04       0
20.09003     .14       0
#XS Ineff= 2 , 0
Permanent Ineff=
       F       F
Bank Sta=-20.35,20.09
XS Rating Curve= 0 ,0
Exp/Cntr=0.3,0.1

Type RM Length L Ch R = 1 ,443.4068,399.3098,343.5354,278.3133
XS GIS Cut Line= 3
   1476167.82185   1100116.18406   1476006.36056   1099749.32415
   1475811.05085   1099368.78806
#Sta/Elev= 30
 -401.31  903.76 -375.83  902.81 -353.44  900.66 -316.18  900.16 -250.72  895.85
 -209.75   889.6 -184.32  884.29 -136.47  879.55   -94.7  872.92   -63.9  866.77
  -48.42  865.42  -29.21  865.95  -24.16  864.69  -20.35  856.09  -18.12  854.51
    9.82  857.02   20.09  859.18   47.01  869.09   81.64  866.67   99.47  868.46
  163.94  867.54  192.32  869.01  204.99  871.46   224.6  872.94  236.19  876.54
  248.45  878.02  275.33  884.71  319.71  892.63  351.74  896.58  427.24  899.76
#Mann= 5 ,-1,0
 -401.31      .1       0 -136.47     .14       0  -20.35     .04       0
   20.09     .14       0  275.33      .1       0
Bank Sta=-20.35,20.09
XS Rating Curve= 0 ,0
Exp/Cntr=0.3,0.1

Type RM Length L Ch R = 1 ,99.87141,68.07822,99.87141,126.4536
BEGIN DESCRIPTION:
Limit of Detailed Study (Just US of SC Hwy 267)
END DESCRIPTION:
XS GIS Cut Line= 4
   1476792.64895   1099783.43012   1476415.20997   1099593.88091
   1476203.08858   1099484.80709    1475630.5397   1099186.64173
#Sta/Elev= 30
 -660.61  888.75 -608.23  884.02 -584.41  879.18 -502.89  875.27 -471.58  875.47
 -418.43  872.55 -299.16  872.38  -280.3  871.51 -237.71  866.46 -186.06  867.34
 -150.34865.5909  -116.9  870.23  -81.53  870.85  -52.07  864.83  -20.35  855.58
  -18.12     854   20.09  858.67    25.3  865.01   36.68  865.71    43.2  867.99
   74.37  872.23  118.48   875.5  121.99  877.44  137.07  880.31  165.54  883.95
   364.6  896.23  432.69   899.2  487.21  904.02  625.42  912.76  645.81  915.53
#Mann= 4 ,-1,0
 -660.61     .14       0 -150.34     .14       0-20.3499     .04       0
20.09003     .14       0
#XS Ineff= 2 , 0
Permanent Ineff=
       F       F
Bank Sta=-20.35,20.09
XS Rating Curve= 0 ,0
Exp/Cntr=0.3,0.1
LCMann Table=0

--- 12mile_Combined.g05 (geometry) ---

Geom Title=Corrected Effective
Program Version=6.10

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
River Reach=Twelvemile Crk  ,Reach1

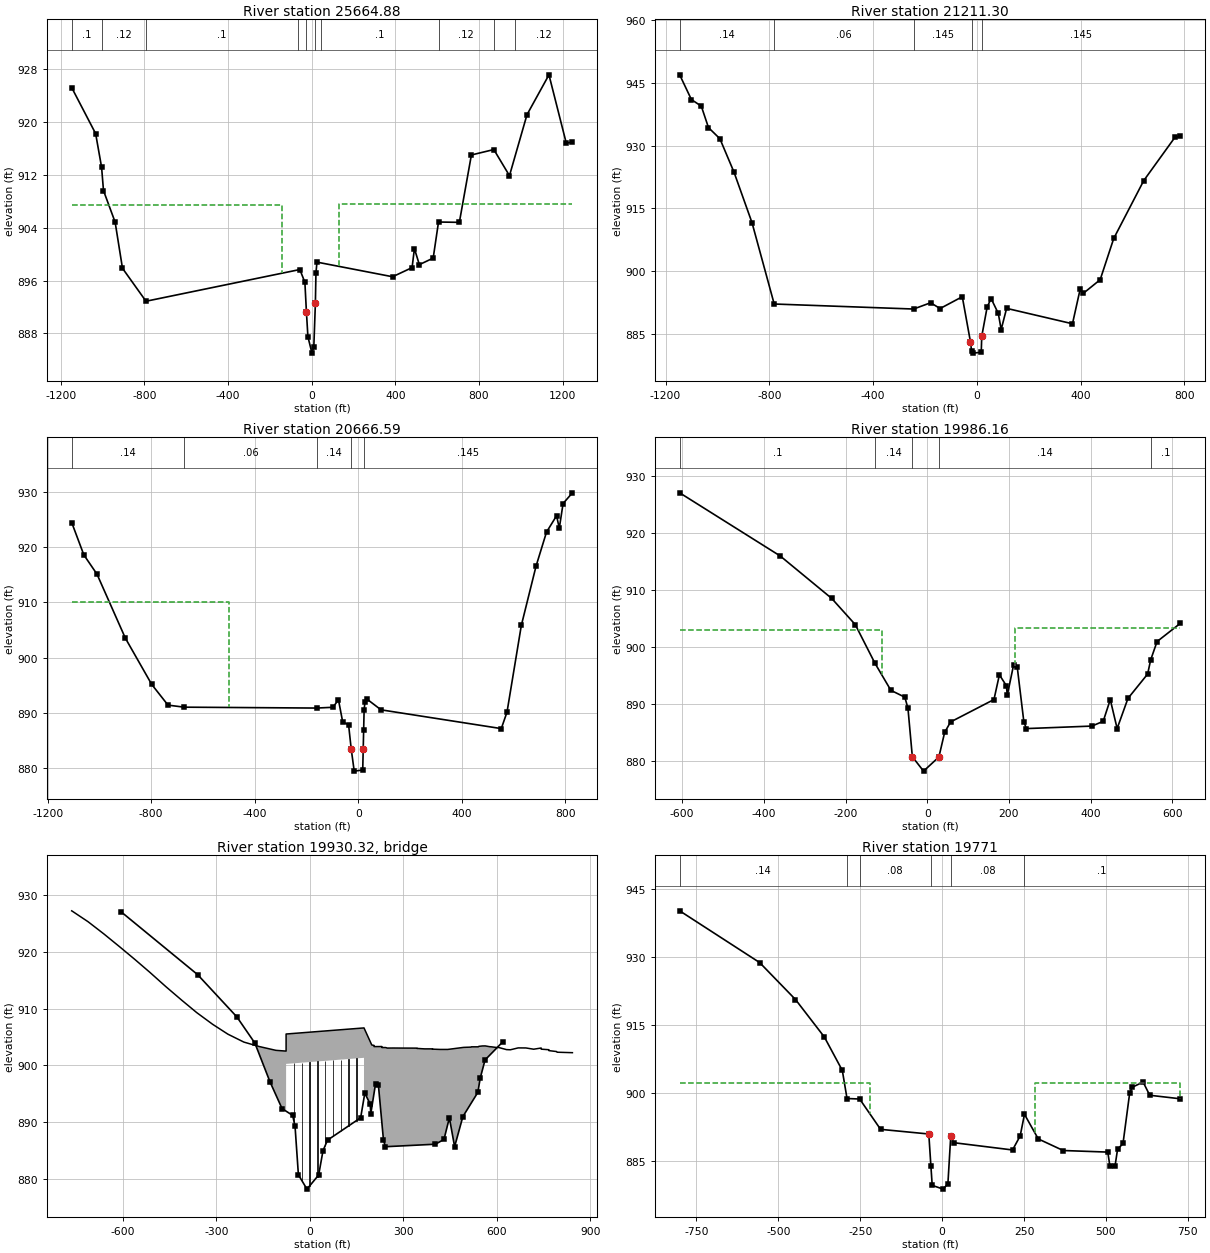
Type RM Length L Ch R = 1 ,25664.88,778.3932,1245.781,1447.994
BEGIN DESCRIPTION:
Shady Grove RD (TWE_14) - DS
END DESCRIPTION:
XS GIS Cut Line= 5
   1476742.02822    1115077.0397    1475546.2792   1115641.27657
   1474856.17388    1115968.9685    1474556.6939   1116103.51739
   1474207.30085   1116127.38878
#Sta/Elev= 30
-1147.51  925.15-1033.05   918.2 -1004.6  913.12-995.505  909.59-939.854  904.82
-904.702  897.85-792.197  892.87 -56.603  897.66 -32.485  895.73 -25.141  891.26
 -18.022  887.52    1.29  885.03  10.262  886.01   17.71  892.54   20.43  897.14
  25.279  898.78 386.871  896.57 480.159  897.95 491.288  900.82 514.869   898.4
 581.042  899.39 606.495  904.84 706.174  904.79 763.713  914.97 870.996  915.79
  945.83  911.841029.635  921.061134.658  927.081217.554  916.741246.747  916.95
#Mann= 10 ,-1,0
-1147.51      .1       0 -1004.6     .12       0-792.197      .1       0
-63.5317     .14       0-25.1407    .045       017.70996     .14       0
46.62695      .1       0 606.495     .12       0 870.996     .06       0
971.6631     .12       0
#XS Ineff= 2 ,-1
-1147.51    -140   907.4     1301246.747   907.5
Permanent Ineff=
       F       F
Bank Sta=-25.141,17.71
XS Rating Curve= 0 ,0
Skew Angle= 30
Exp/Cntr=0.5,0.3

Type RM Length L Ch R = 1 ,21211.30,610.2067,544.715,527.129
XS GIS Cut Line= 3
   1478558.16798    1112492.5502   1477412.33235   1112548.97375
   1476631.08104   1112601.05709
#Sta/Elev= 30
-1145.45  946.94-1100.25  941.03-1062.05  939.45-1034.45  934.33 -990.45  931.67
 -935.85  923.65 -866.45  911.57 -781.05  892.16 -243.75  890.96 -178.05  892.46
 -141.45  891.08  -55.95   893.9  -24.55  883.16  -20.25  881.02  -15.75  880.42
   17.15  880.62   19.05  884.43   40.05  891.47   55.25  893.46   82.95   889.9
   93.95  886.06  114.95  891.12  368.85  887.44  398.25  895.64  410.35   894.7
  475.65  897.97  527.85  907.82  643.65  921.66  763.35  931.96  784.85  932.28
#Mann= 5 ,-1,0
-1145.45     .14       0 -781.05     .06       0 -243.75    .145       0
  -20.25     .04       020.84998    .145       0
Bank Sta=-24.55,19.05
XS Rating Curve= 0 ,0
Exp/Cntr=0.3,0.1

Type RM Length L Ch R = 1 ,20666.59,564.6,564.6,564.6
BEGIN DESCRIPTION:
TWE_11X
END DESCRIPTION:
XS GIS Cut Line= 4
   1478404.08793   1111901.40289   1477303.00787   1112023.66371
   1477126.72736   1112046.60039    1476716.8107   1112548.89272
#Sta/Elev= 30
-1106.95  924.42-1060.05  918.57-1009.25  915.09 -899.75  903.54 -797.75  895.17
 -734.95  891.44 -672.55  891.07 -160.65  890.91  -98.05  891.05  -76.55   892.4
  -60.35  888.42  -37.45  887.88  -27.35  883.53  -15.75  879.52   17.15  879.72
   19.05  883.53   20.75  886.98   22.55   890.6   25.85  892.04   34.25   892.5
   87.85  890.59  552.35   887.2  574.45  890.18  629.75  905.83  686.75  916.56
  727.05  922.69  765.85  925.64  776.45   923.4  791.05  927.85  827.05  929.78
#Mann= 5 ,-1,0
-1106.95     .14       0 -672.55     .06       0 -160.65     .14       0
-27.3499     .04       0   20.75    .145       0
#XS Ineff= 2 , 0
         -499.96     910
Permanent Ineff=
       F       F
Bank Sta=-27.35,19.05
XS Rating Curve= 0 ,0
Exp/Cntr=0.3,0.1

Type RM Length L Ch R = 1 ,19986.16,164.8615,199.5731,183.0735
BEGIN DESCRIPTION:
Walhalla Hwy (TWE_10) - US
END DESCRIPTION:
XS GIS Cut Line= 6
    1477849.2818    1111415.8717    1476783.3071    1111391.5659
    1476604.4875    1111370.7326    1476408.3064    1111407.1909
    1476338.8622    1111433.2326 1476335.59345811111432.77861468
#Sta/Elev= 30
 -605.91  927.02 -359.81  915.96 -233.81  908.53 -176.01  903.93 -127.91  897.17
  -88.91  892.43  -54.81  891.23  -47.16   889.3  -36.41   880.8   -8.96  878.28
   28.61  880.76   42.61  885.05   57.12  886.89  163.39  890.82  176.69  895.15
  193.99  893.21  195.89  891.53  211.29  896.83  220.39  896.49  236.49  886.95
  242.59  885.73  403.29  886.17  430.79  887.01  448.09  890.81  464.89  885.74
  491.39  891.02  539.49  895.28  546.99  897.76  562.59  900.97  619.69  904.17
#Mann= 5 ,-1,0
 -605.91      .1       0 -127.91     .14       0  -36.41    .035       0
   28.61     .14       0  546.99      .1       0
#XS Ineff= 2 , 0
         -111.61     903  216.09          903.33
Permanent Ineff=
       F       F
Bank Sta=-36.41,28.61
XS Rating Curve= 0 ,0
Skew Angle= 35
Exp/Cntr=0.5,0.3

Type RM Length L Ch R = 3 ,19930.32,,,
BEGIN DESCRIPTION:
Walhalla Hwy (TWE_10) - TOR
Skew = 35 Degrees
END DESCRIPTION:
Bridge Culvert--1,0,-1,-1, 0
Deck Dist Width WeirC Skew NumUp NumDn MinLoCord MaxHiCord MaxSubmerge Is_Ogee
36,39.5,2.6,35, 130, 130, 901.51, , 0.95, 0, 0,0,,
 -763.91 -762.01 -761.81 -761.61 -736.81 -736.61 -711.81 -711.61 -711.51 -700.11
 -686.61 -686.51 -661.61 -661.11 -636.41 -636.11 -635.71 -611.11 -610.81 -610.41
 -585.81 -585.31 -562.11 -537.71 -537.11 -513.51 -513.01 -488.41 -488.01 -463.41
 -463.01 -461.91 -437.21 -437.01 -412.21 -412.01 -410.91 -410.81 -385.91 -372.81
 -362.81 -362.71 -337.81 -312.81 -311.51 -286.71 -286.51 -286.41 -262.81 -262.61
 -237.71 -237.71 -237.61 -232.31 -212.91 -212.71 -212.61 -211.61 -211.41 -186.71
 -186.41 -162.01 -137.71 -137.01 -113.01 -112.01 -111.91 -109.61 -108.51  -84.61
  -84.01  -75.91  -75.91  174.09  199.09  204.49  204.99  206.09  206.29  206.39
  206.39  230.99  231.09  231.29  231.39  231.49  243.39  243.59  243.59  243.69
  243.99  248.79  268.59  293.59  343.79  343.89  343.89  368.89  393.89  393.89
  418.89  442.69  492.69  493.69  517.49  518.69  540.59  542.69  553.59  563.09
  577.79  581.49  598.99  606.39  631.39  643.89  668.89  693.59  718.59  742.69
  742.69  767.39  767.69  792.09  792.79  794.29  794.39  818.99  819.29  842.89
  927.17  927.11   927.1  927.09  926.19  926.18  925.27  925.26  925.26  924.78
  924.21  924.21  923.16  923.13  922.03  922.02     922   920.9  920.89  920.87
  919.75  919.72  918.67  917.52  917.49  916.38  916.36  915.16  915.14  913.93
  913.91  913.86   912.7  912.69  911.53  911.52  911.47  911.47  910.34  909.75
  909.29  909.29  908.29  907.28  907.23  906.35  906.34  906.34  905.51   905.5
  904.83  904.82  904.82  904.68  904.15  904.14  904.14  904.11  904.11  903.72
  903.72  903.33  903.02  903.01   902.7  902.69  902.69  902.66  902.66  902.56
  902.56  902.53  905.53   906.6   903.6  903.55  903.53  903.53  903.49  903.34
  903.32  903.32  903.33  903.33  903.16  903.16  903.15  903.15  903.14  903.14
  903.15  903.06  903.07  903.06  903.06  903.05     903  902.92  902.92  902.87
  902.82  902.82  903.18  903.18  903.23  903.28  903.28  903.36  903.43  903.44
   903.3  903.29  903.17  903.16  902.79  902.76  903.09  903.08  902.86  903.07
  902.87  902.77  902.61  902.45  902.39  902.33  902.33  902.29  902.29  902.25
                                                                                
                                                                                
                                                                                
                                                                                
                                                                                
                                                                                
                                                                                
          900.28  900.28  901.35
                                                                                
                                                                                
                                                                                
                                                                                
                                                                                
 -763.91 -762.01 -761.81 -761.61 -736.81 -736.61 -711.81 -711.61 -711.51 -700.11
 -686.61 -686.51 -661.61 -661.11 -636.41 -636.11 -635.71 -611.11 -610.81 -610.41
 -585.81 -585.31 -562.11 -537.71 -537.11 -513.51 -513.01 -488.41 -488.01 -463.41
 -463.01 -461.91 -437.21 -437.01 -412.21 -412.01 -410.91 -410.81 -385.91 -372.81
 -362.81 -362.71 -337.81 -312.81 -311.51 -286.71 -286.51 -286.41 -262.81 -262.61
 -237.71 -237.71 -237.61 -232.31 -212.91 -212.71 -212.61 -211.61 -211.41 -186.71
 -186.41 -162.01 -137.71 -137.01 -113.01 -112.01 -111.91 -109.61 -108.51  -84.61
  -84.01  -75.91  -75.91  174.09  199.09  204.49  204.99  206.09  206.29  206.39
  206.39  230.99  231.09  231.29  231.39  231.49  243.39  243.59  243.59  243.69
  243.99  248.79  268.59  293.59  343.79  343.89  343.89  368.89  393.89  393.89
  418.89  442.69  492.69  493.69  517.49  518.69  540.59  542.69  553.59  563.09
  577.79  581.49  598.99  606.39  631.39  643.89  668.89  693.59  718.59  742.69
  742.69  767.39  767.69  792.09  792.79  794.29  794.39  818.99  819.29  842.89
  927.17  927.11   927.1  927.09  926.19  926.18  925.27  925.26  925.26  924.78
  924.21  924.21  923.16  923.13  922.03  922.02     922   920.9  920.89  920.87
  919.75  919.72  918.67  917.52  917.49  916.38  916.36  915.16  915.14  913.93
  913.91  913.86   912.7  912.69  911.53  911.52  911.47  911.47  910.34  909.75
  909.29  909.29  908.29  907.28  907.23  906.35  906.34  906.34  905.51   905.5
  904.83  904.82  904.82  904.68  904.15  904.14  904.14  904.11  904.11  903.72
  903.72  903.33  903.02  903.01   902.7  902.69  902.69  902.66  902.66  902.56
  902.56  902.53  905.53   906.6   903.6  903.55  903.53  903.53  903.49  903.34
  903.32  903.32  903.33  903.33  903.16  903.16  903.15  903.15  903.14  903.14
  903.15  903.06  903.07  903.06  903.06  903.05     903  902.92  902.92  902.87
  902.82  902.82  903.18  903.18  903.23  903.28  903.28  903.36  903.43  903.44
   903.3  903.29  903.17  903.16  902.79  902.76  903.09  903.08  902.86  903.07
  902.87  902.77  902.61  902.45  902.39  902.33  902.33  902.29  902.29  902.25
                                                                                
                                                                                
                                                                                
                                                                                
                                                                                
                                                                                
                                                                                
          900.28  900.28  901.35
                                                                                
                                                                                
                                                                                
                                                                                
                                                                                
Pier Skew, UpSta & Num, DnSta & Num=  ,-50.36, 2 ,-50.36, 2 , 0 , 0 , 0 ,,
       1       1
  878.34  901.35
       1       1
  878.34  901.35
Pier Skew, UpSta & Num, DnSta & Num=  ,-25.36, 2 ,-25.36, 2 , 0 , 0 , 0 ,,
       1       1
  878.34  901.35
       1       1
  878.34  901.35
Pier Skew, UpSta & Num, DnSta & Num=  ,-0.36, 2 ,-0.36, 2 , 0 , 0 , 0 ,,
       1       1
  878.34  901.35
       1       1
  878.34  901.35
Pier Skew, UpSta & Num, DnSta & Num=  ,24.64, 2 ,24.64, 2 , 0 , 0 , 0 ,,
       1       1
  878.34  901.35
       1       1
  878.34  901.35
Pier Skew, UpSta & Num, DnSta & Num=  ,49.64, 2 ,49.64, 2 , 0 , 0 , 0 ,,
       1       1
  878.34  901.35
       1       1
  878.34  901.35
Pier Skew, UpSta & Num, DnSta & Num=  ,74.64, 2 ,74.64, 2 , 0 , 0 , 0 ,,
       1       1
  878.34  901.35
       1       1
  878.34  901.35
Pier Skew, UpSta & Num, DnSta & Num=  ,99.64, 2 ,99.64, 2 , 0 , 0 , 0 ,,
       1       1
  878.34  901.35
       1       1
  878.34  901.35
Pier Skew, UpSta & Num, DnSta & Num=  ,124.64, 2 ,124.64, 2 , 0 , 0 , 0 ,,
       1       1
  878.34  901.35
       1       1
  878.34  901.35
Pier Skew, UpSta & Num, DnSta & Num=  ,149.64, 2 ,149.64, 2 , 0 , 0 , 0 ,,
       1       1
  878.34  901.35
       1       1
  878.34  901.35
Abutment Skew #Up #Dn= , 2 , 2
  -75.91  -55.91
  899.28  890.28
  -75.91  -55.91
  899.28  890.28
Abutment Skew #Up #Dn= , 2 , 2
  144.18  174.18
  886.35  900.35
  144.18  174.18
  886.35  900.35
BR Coef=-1 ,-1 , 0 ,, 0 ,,,0.8,0,1.2,0,
WSPro=,,,, 1 ,,,, 0 ,,,, 0 ,,,,-1 ,-1 ,-1 , 0 , 0 , 0 , 0 , 0
BC Design=,, 0 ,, 0 ,,,,,,
BC Use User HTab Curves=0
BC User HTab FreeFlow(D)= 0

Type RM Length L Ch R = 1 ,19771   ,297.5,359.2,349.6
XS GIS Cut Line= 6
    1477797.9587       1111252.6    1477340.1051    1111254.1761
    1477007.1185    1111217.8214    1476697.2407     1111219.325
     1476533.666    1111195.4944    1476304.3001    1111316.0996
#Sta/Elev= 30
 -801.18  940.23 -557.18  928.82 -447.68  920.66 -359.58  912.39 -304.78  905.02
 -290.38  898.82 -251.78  898.71 -187.98  892.02  -40.78  890.99  -34.38  883.92
  -30.38  879.66    3.12  878.83   17.52  880.03   26.22  890.56   34.82  889.08
  214.82  887.47  238.12  890.57  251.22  895.34  293.32  889.91  369.32  887.35
  505.52     887  512.22  883.83  527.42  883.83  535.32  887.59  552.02   888.9
  572.32  900.01  580.22  901.31  613.32  902.45  633.62  899.54  727.12  898.76
#Mann= 6 ,-1,0
 -801.18     .14       0 -290.38     .06       0 -251.78     .08       0
  -34.38    .035       026.21997     .08       0250.1201      .1       0
#XS Ineff= 2 , 0
         -220.66  902.33  283.19          902.33
Permanent Ineff=
       F       F
Bank Sta=-40.78,26.22
XS Rating Curve= 0 ,0
Exp/Cntr(USF)=0,0
Exp/Cntr=0.5,0.3

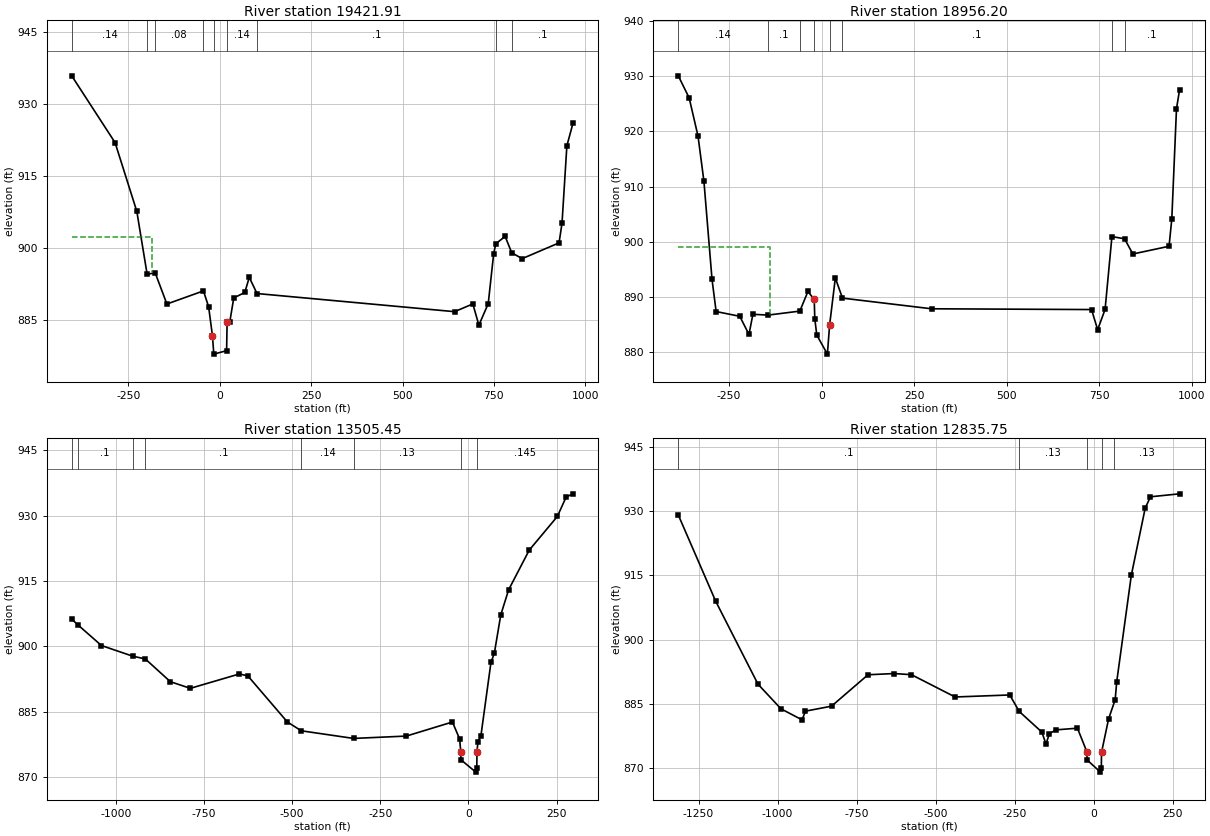
Type RM Length L Ch R = 1 ,19421.91,522.9336,465.7054,185.1479
XS GIS Cut Line= 4
   1477377.90814   1110938.60761   1476974.30643   1110885.60925
   1476780.65879   1110857.07185   1476199.35663   1111360.24377
#Sta/Elev= 30
 -405.13  935.83 -286.53  921.94 -227.03  907.64 -198.73  894.53 -176.93  894.89
 -144.73  888.37  -44.73   891.1  -30.53   887.8  -20.13   881.8  -16.33  877.95
   18.67  878.67   20.07  884.68   27.37  884.66   38.27  889.64   68.47  890.77
   80.67  893.92  101.87  890.55  642.47  886.78  692.47  888.39  708.97  883.98
  734.57  888.44  749.47  898.84  755.47  900.92  780.87  902.43  798.87  899.03
  827.47  897.81  928.37  901.09  936.47  905.17  949.77  921.28  966.47  925.97
#Mann= 9 ,-1,0
 -405.13     .14       0 -198.73     .06       0 -176.93     .08       0
  -44.73     .14       0-16.3299    .045       020.07001     .14       0
  101.87      .1       0  755.47     .06       0  798.87      .1       0
#XS Ineff= 2 , 0
         -186.75  902.26
Permanent Ineff=
       F       F
Bank Sta=-20.13,20.07
XS Rating Curve= 0 ,0
Exp/Cntr=0.5,0.3

Type RM Length L Ch R = 1 ,18956.20,41.10629,40.11645,40.70418
BEGIN DESCRIPTION:
Unnamed Foot Bridge - US
END DESCRIPTION:
XS GIS Cut Line= 4
   1477022.27493   1110294.26903    1476747.2523   1110536.14403
   1476686.03609   1110595.77953   1476183.73163   1111346.35466
#Sta/Elev= 30
 -387.46  930.08 -358.06  926.08 -334.06  919.14 -318.16  910.97 -296.26  893.21
 -285.19   887.4 -221.27  886.54  -196.4  883.25 -185.84   886.9  -144.5  886.76
  -58.94  887.48  -37.06  891.03  -20.04  889.59  -18.48   886.1  -13.12  883.14
   15.54  879.69   21.53  884.95   37.02  893.48   56.28  889.83  296.97   887.9
  729.58  887.76  746.05  884.11  766.15  887.79  784.65  900.97  818.74  900.58
  841.17  897.82  939.09  899.22   946.5  904.18  959.18  924.14   967.4   927.5
#Mann= 8 ,-1,0
 -387.46     .14       0  -144.5      .1       0  -58.94     .14       0
  -20.04    .045       0   21.53     .14       0   56.28      .1       0
  784.65     .06       0  818.74      .1       0
#XS Ineff= 2 , 0
            -140  899.01      40             890
Permanent Ineff=
       F       F
Bank Sta=-20.04,21.53
XS Rating Curve= 0 ,0
Exp/Cntr=0.5,0.3

Type RM Length L Ch R = 1 ,13505.45,593.0652,669.6997,674.7907
XS GIS Cut Line= 4
   1474176.62631   1108541.52953   1473978.17192   1108077.24508
   1473752.98819   1107513.05348    1473631.4603   1107228.33104
#Sta/Elev= 30
-1125.39  906.28-1108.38  904.98-1041.04   900.2 -952.89  897.77 -916.62  897.12
 -845.65   891.9 -789.02  890.37 -649.54  893.68 -625.53  893.21 -513.71  882.65
 -474.13  880.62 -325.87  878.87 -176.06  879.41  -45.41  882.64  -24.94  878.73
  -21.86  875.84  -21.21  873.96   20.95  871.13   23.65  872.01   24.31  875.73
   26.92  878.14   35.25  879.38   63.87  896.32   73.48  898.43   91.78  907.25
     114     913  172.46  922.11  252.23  929.84  277.18  934.31  296.57  935.04
#Mann= 8 ,-1,0
-1125.39     .14       0-1108.38      .1       0 -952.89     .14       0
 -916.62      .1       0 -474.13     .14       0 -325.87     .13       0
-21.8597     .04       024.31006    .145       0
Bank Sta=-21.86,24.31
XS Rating Curve= 0 ,0
Exp/Cntr=0.3,0.1

Type RM Length L Ch R = 1 ,12835.75,550.2411,526.0508,447.1309
XS GIS Cut Line= 3
   1474746.04593   1108613.75033   1474343.26739    1107363.7477
   1474464.79528    1107120.6916
#Sta/Elev= 30
-1314.03  929.05-1195.56  908.92-1061.89  889.61 -989.31  883.88 -922.62  881.31
 -911.92  883.34 -829.43   884.5 -714.09  891.82 -631.73   892.1 -576.79  891.84
 -438.68  886.64 -265.82  887.11 -235.95  883.27 -164.48  878.47 -151.31  875.68
 -140.45   878.1 -119.24  878.98  -51.87  879.37  -21.86  873.84  -21.21  871.96
   20.95  869.13   23.65  870.01   24.31  873.73   46.74  881.55   67.51  886.01
   72.31  890.16  118.53  915.01  162.49  930.67  179.15  933.29  271.01  933.98
#Mann= 5 ,-1,0
-1314.03      .1       0 -235.95     .13       0-21.8597     .04       0
24.31006     .13       064.90002     .13       0
#XS Ineff= 1 ,-1
-1127.15 -703.94  889.96
Permanent Ineff=
       F
Bank Sta=-21.86,24.31
XS Rating Curve= 0 ,0
Exp/Cntr=0.3,0.1